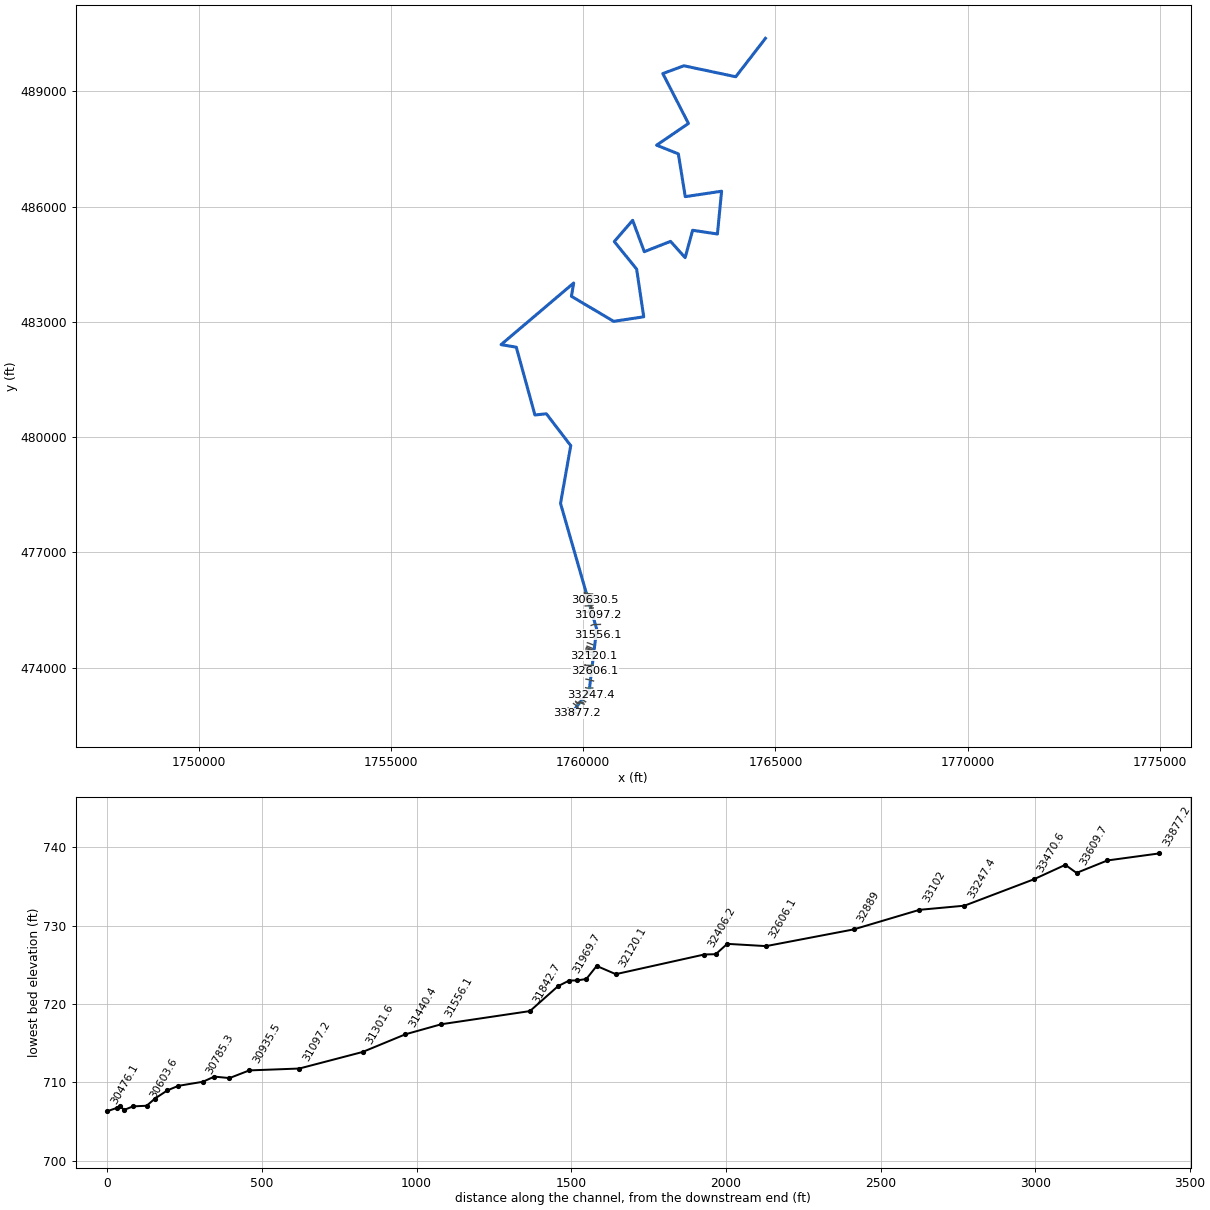
--- TRACEFORK.prj (project) ---

Proj Title=TRACEFORK
Current Plan=p01
Default Exp/Contr=0,0
English Units
Geom File=g01
Flow File=f01
Plan File=p01
BEGIN DESCRIPTION:
END DESCRIPTION:
DSS Export Rating Curves= 0
DSS Export Rating Curve Sorted= 0
DSS Export Volume Flow Curves= 0
DXF OffsetX= 0
DXF OffsetY= 0
DXF ScaleX= 0
DXF ScaleY= 0

--- TRACEFORK.p01 (plan) ---

Plan Title=Floodplain
Program Version=4.00
Geom File=g01
Flow File=f01
K Sum by GR=0
Std Step Tol=0.01
Critical Tol=0.01
Num of Std Step Trials=20
Max Error Tol=0.3
Flow Tol Ratio=0.001
Split Flow NTrial=30
Split Flow Tol=0.02
Split Flow Ratio=0.02
Log Output Level=0
Friction Slope Method=1
Unsteady Friction Slope Method=2
Unsteady Bridges Friction Slope Method=1
Global Log Level=0
CheckData=False
Run HTab=0
Run UNet=0
Run PostProcess=0
UNET Theta=0
UNET Theta Warmup=0
UNET ZTol=0
UNET ZSATol=0
UNET MxIter=0
UNET MaxInSteps=0
UNET DtIC=0
UNET DtMin=0
UNET MaxCRTS=0
UNET WFStab=0
UNET SFStab=0
UNET WFX=0
UNET SFX=0
UNET DSS MLevel=0
UNET DZMax Abort=0
UNET Convert EG Bridges=0
UNET Use Existing IB Tables=0
UNET Froude Limit=0
UNET Froude Power=0
Write IC File=0
Echo Input=False
Echo Output=False
Write Detailed=0

--- TRACEFORK.f01 (steady flow) ---

Flow Title=NFF Regression Equation
Program Version=4.10
Number of Profiles= 1
Profile Names=P100yr
River Rch & RM=TRACEFORK,Main            ,33877.2
904.5888
River Rch & RM=TRACEFORK,Main            ,30603.6
1084.514
River Rch & RM=TRACEFORK,Main            ,28904.5
1121.915
River Rch & RM=TRACEFORK,Main            ,28166.1
1486.007
River Rch & RM=TRACEFORK,Main            ,25008.5
 1608.11
River Rch & RM=TRACEFORK,Main            ,22410.4
1785.625
River Rch & RM=TRACEFORK,Main            ,21894.1
2147.619
River Rch & RM=TRACEFORK,Main            ,18480.8
2207.124
River Rch & RM=TRACEFORK,Main            ,2692.6
2432.741
Boundary for River Rch & Prof#=TRACEFORK,Main            , 1
Up Type= 0
Dn Type= 3
Dn Slope=0.002
DSS Import GetInterval= 0
DSS Import GetPeak= 0
DSS Import FillOption= 0

--- TRACEFORK.g01 (geometry) ---

Geom Title=USGS 10m DEM
Program Version=4.10

River Reach=TRACEFORK       ,Main
Reach XY= 30
     1759721.806      472848.449     1760155.834        473411.6
     1760350.061      475003.397     1759409.306      478274.881
     1759675.148      479778.788     1759040.382      480606.696
     1758743.073      480576.314     1758258.047      482339.552
     1757862.125      482406.421     1759751.448      484009.286
     1759692.855      483664.234     1760791.684      483012.295
     1761574.019      483130.567     1761389.558      484370.802
      1760807.96      485088.032     1761285.391      485640.333
      1761589.21      484824.361     1762271.719      485093.458
     1762651.493      484669.196       1762846.5      485381.682
     1763491.337       485284.43     1763599.844      486397.711
     1762654.749      486256.652     1762474.627      487369.933
     1761909.306      487595.628     1762737.681      488160.274
     1762070.981      489458.692     1762618.941        489661.6
     1763968.768      489376.227     1764741.337      490375.576

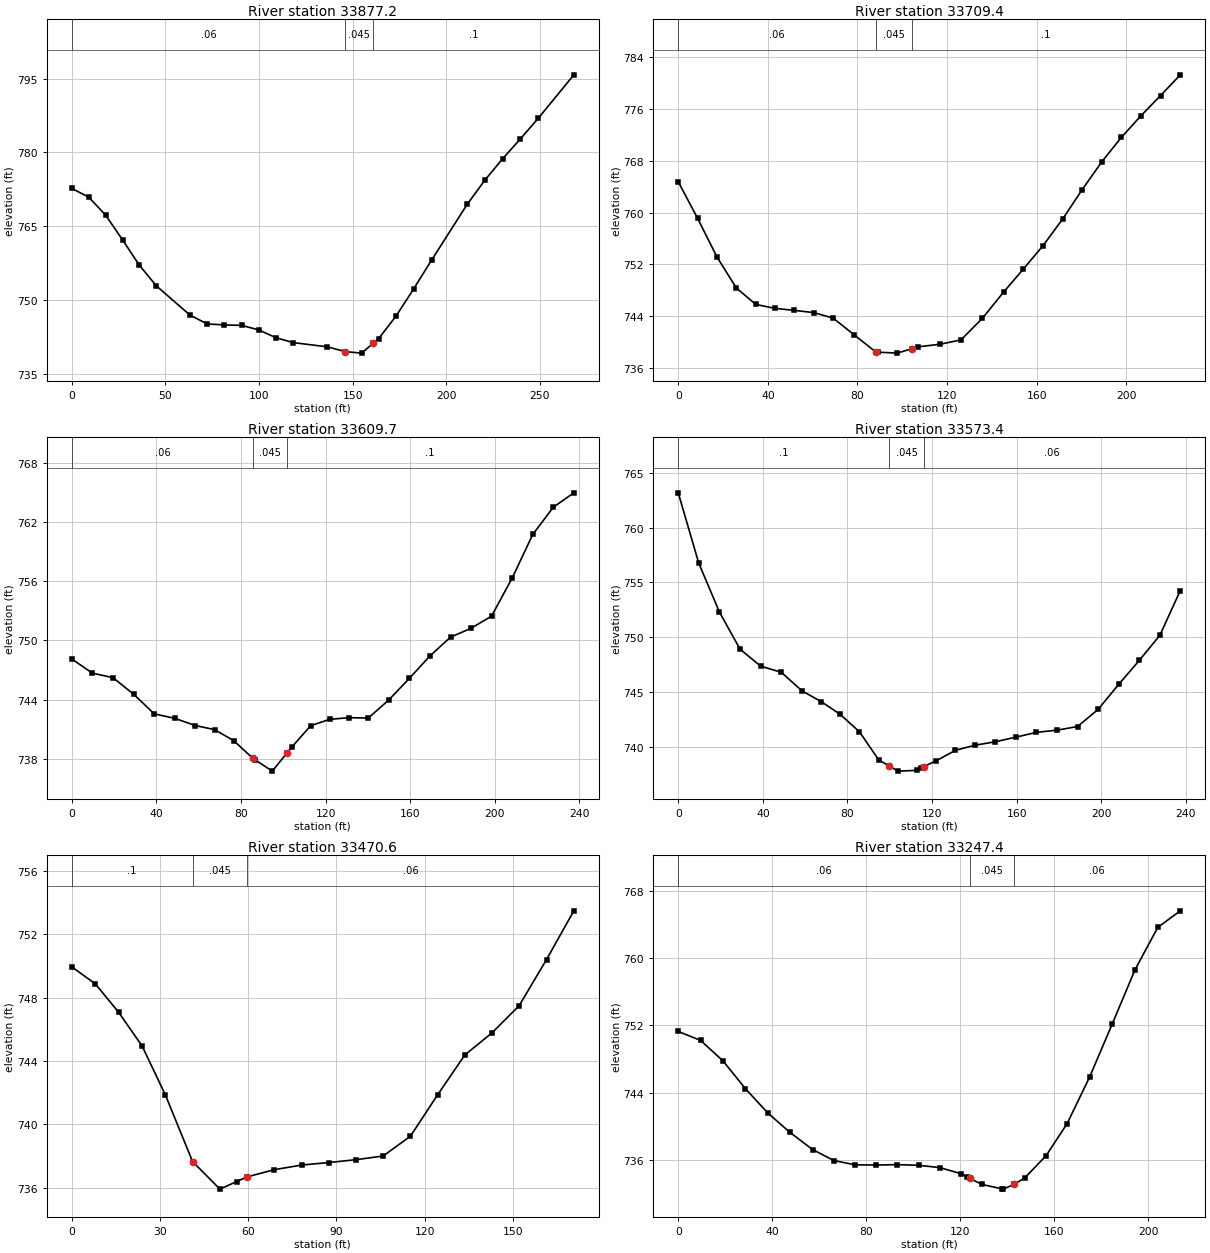
Type RM Length L Ch R = 1 ,33877.2 ,176.2,167.8,160
XS GIS Cut Line= 4
     1759607.237      472953.701     1759651.508      472908.562
     1759750.466      472860.819     1759832.063      472812.208
#Sta/Elev= 27
       0  772.69       9  770.94    18.1  767.25    27.1  762.25    36.1  757.08
    45.2  752.88    63.2  746.92    72.4  745.15    81.5  744.95    90.7  744.86
    99.8  743.94     109  742.36   118.2  741.36   136.5   740.5     146  739.53
   154.8  739.22     161  741.24   163.9  742.19   173.1  746.72   182.6   752.3
   192.1  758.11   211.1  769.43   220.6  774.38   230.1  778.74   239.6  782.78
   249.1  786.95   268.1  795.78
#Mann= 3 , 0 , 0
       0     .06       0     146    .045       0     161      .1       0
Bank Sta=146,161
XS Rating Curve= 0 ,0
Exp/Cntr=0.3,0.1

Type RM Length L Ch R = 1 ,33709.4 ,70.1,99.7,127.2
XS GIS Cut Line= 4
     1759746.126      473068.284      1759802.55      473028.354
     1759854.633      472972.798     1759901.508       472909.43
#Sta/Elev= 28
       0  764.75     8.6  759.14    17.3  753.14    25.9  748.38    34.6  745.83
    43.2  745.22    51.8  744.91    60.5  744.57    69.1  743.73    78.6  741.12
    88.2  738.49    89.2  738.47    97.7  738.32   104.2  738.99   107.2   739.3
   116.7  739.68   126.2  740.36   135.8   743.7   145.3  747.77     154  751.27
   162.8  754.88   171.6  759.01   180.3  763.54   189.1  767.84   197.8   771.6
   206.6  774.95   215.3  778.05   224.1  781.24
#Mann= 3 , 0 , 0
       0     .06       0    88.2    .045       0   104.2      .1       0
Bank Sta=88.2,104.2
XS Rating Curve= 0 ,0
Exp/Cntr=0.3,0.1

Type RM Length L Ch R = 1 ,33609.7 ,38,36.3,42.6
XS GIS Cut Line= 4
     1759812.966      473095.194     1759857.237      473056.999
     1759932.758      473088.249     1760022.168      473050.055
#Sta/Elev= 28
       0  748.12     9.7  746.69    19.5  746.22    29.2  744.55      39  742.55
    48.7  742.09    58.5  741.36    67.6  740.94    76.6  739.82    85.7  738.02
    86.6  737.89    94.8  736.73   101.6  738.53   103.9  739.14     113  741.35
     122  741.99   131.1  742.16   140.2  742.12   149.9  743.96   159.6  746.15
   169.4  748.44   179.1  750.34   188.8  751.24   198.5  752.48   208.3  756.37
     218  760.78   227.7  763.54   237.4     765
#Mann= 3 , 0 , 0
       0     .06       0    85.7    .045       0   101.6      .1       0
Bank Sta=85.7,101.6
XS Rating Curve= 0 ,0
Exp/Cntr=0.3,0.1

Type RM Length L Ch R = 1 ,33573.4 ,124.6,102.8,73.1
XS GIS Cut Line= 4
     1759801.682      473126.444     1759845.952      473088.249
     1759921.473      473119.499     1760010.883      473081.305
#Sta/Elev= 29
       0  763.17     9.7  756.75    19.5  752.28    29.2   748.9      39  747.34
    48.7  746.79    58.5  745.09    67.6  744.11    76.6  742.94    85.7  741.35
    94.8  738.78    99.8  738.22   103.9  737.76     113  737.83   114.8  738.01
  116.25  738.18     122  738.71   131.1  739.66   140.2  740.12   149.9  740.44
   159.6  740.86   169.4   741.3   179.1   741.5   188.8  741.83   198.5  743.39
   208.3  745.69     218  747.87   227.7  750.15   237.4  754.25
#Mann= 3 , 0 , 0
       0      .1       0    99.8    .045       0  116.25     .06       0
Bank Sta=99.8,116.25
XS Rating Curve= 0 ,0
Exp/Cntr=0.3,0.1

Type RM Length L Ch R = 1 ,33470.6 ,221.9,223.2,225.6
XS GIS Cut Line= 3
     1759917.133      473200.229     1759947.515       473190.68
     1760062.966      473113.423
#Sta/Elev= 21
       0  749.94       8  748.87    15.9  747.08    23.9  744.95    31.8  741.87
    41.1  737.64    50.4   735.9    56.1  736.38    59.6  736.67    68.9  737.13
    78.2  737.42    87.4  737.58    96.7  737.76   105.9  737.99   115.2  739.24
   124.5  741.87   133.7  744.37     143  745.78   152.2  747.49   161.5   750.4
   170.8  753.48
#Mann= 3 , 0 , 0
       0      .1       0    41.1    .045       0    59.6     .06       0
Bank Sta=41.1,59.6
XS Rating Curve= 0 ,0
Exp/Cntr=0.3,0.1

Type RM Length L Ch R = 1 ,33247.4 ,134.3,145.5,156.3
XS GIS Cut Line= 4
     1760015.223      473405.958     1760057.758      473367.763
     1760154.112      473318.284     1760195.779      473293.979
#Sta/Elev= 28
       0  751.28     9.5  750.22    19.1  747.77    28.6  744.48    38.1   741.6
    47.6  739.28    57.2  737.25    66.2  735.95    75.2  735.44    84.2  735.41
    93.3  735.46   102.3  735.38   111.3  735.11   120.4  734.38     123  734.01
     124  733.83   129.4   733.1     138  732.57   138.4  732.55  142.83  733.11
   147.4  733.86   156.5   736.5   165.5  740.32   175.1  745.87   184.8  752.22
   194.4   758.6   204.1  763.64   213.7  765.61
#Mann= 3 , 0 , 0
       0     .06       0     124    .045       0  142.83     .06       0
Bank Sta=124,142.83
XS Rating Curve= 0 ,0
Exp/Cntr=0.3,0.1

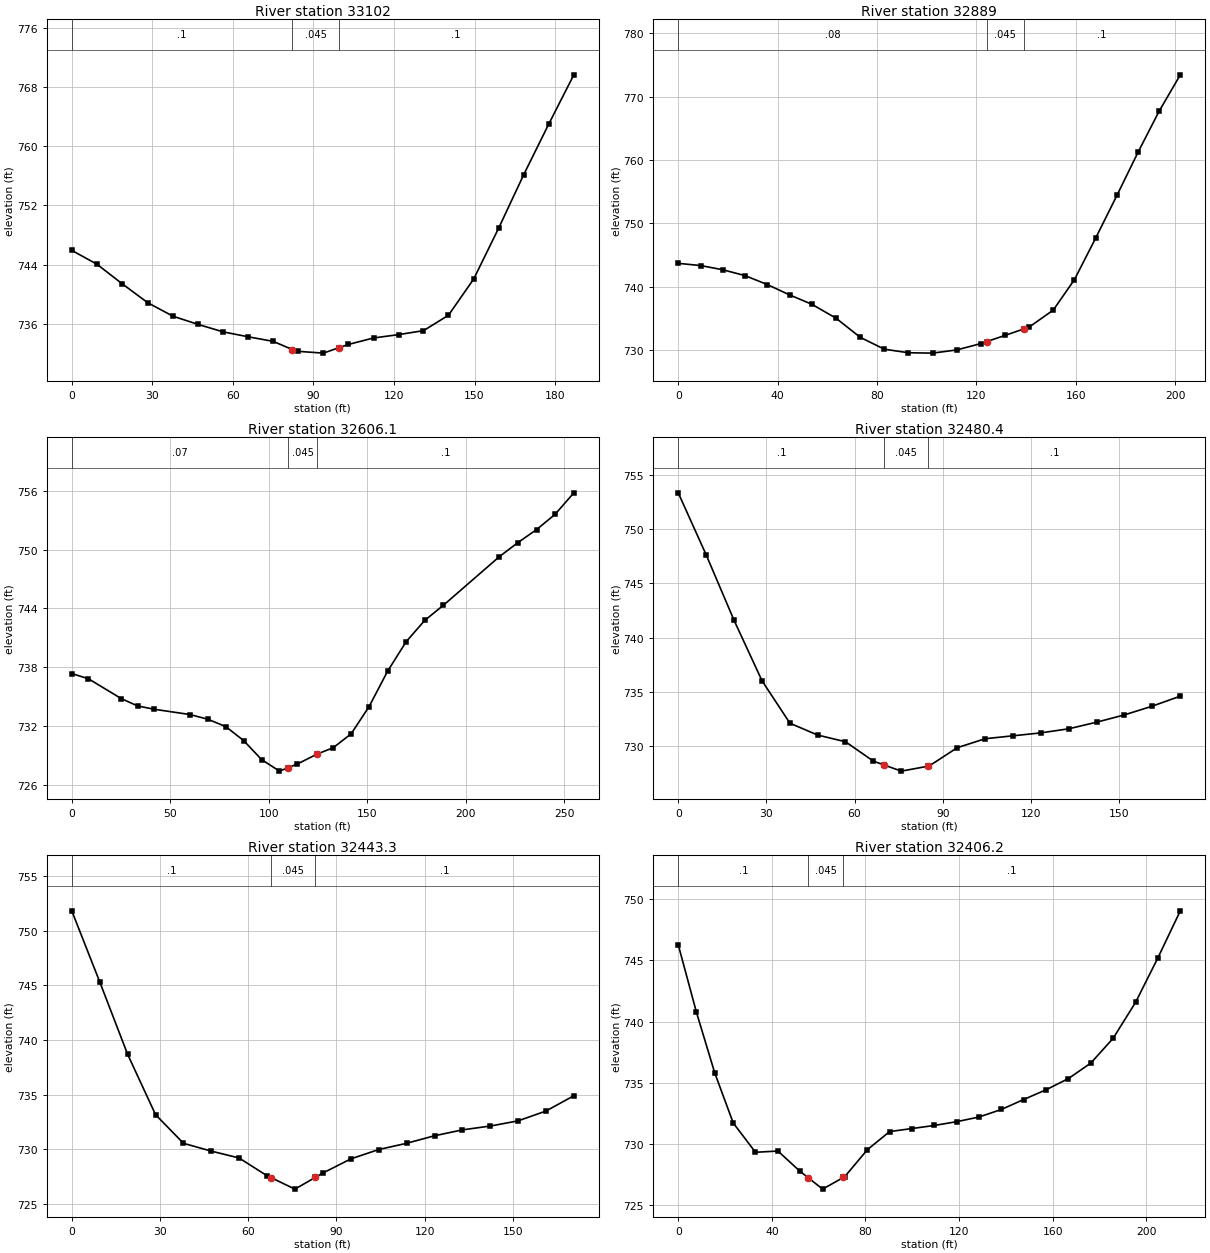
Type RM Length L Ch R = 1 ,33102   ,219.1,213,206.8
XS GIS Cut Line= 3
     1760062.098      473480.611     1760098.557      473471.062
     1760247.862      473472.798
#Sta/Elev= 23
       0  745.91     9.4  744.03    18.8  741.39    28.3  738.83    37.7  737.01
      47  735.91    56.4  734.89    65.7  734.23      75  733.61    82.2   732.5
    84.4  732.26    93.7  732.02    99.4  732.74     103  733.19   112.4  734.07
   121.7  734.52     131  735.06   140.3  737.14   149.7  742.04     159  748.92
   168.3  756.12   177.7  763.02     187  769.64
#Mann= 3 , 0 , 0
       0      .1       0    82.2    .045       0    99.4      .1       0
Bank Sta=82.2,99.4
XS Rating Curve= 0 ,0
Exp/Cntr=0.3,0.1

Type RM Length L Ch R = 1 ,32889   ,264.6,282.8,300.4
XS GIS Cut Line= 4
     1760071.647      473702.833     1760124.598      473693.284
     1760218.348      473668.111     1760267.827       473655.09
#Sta/Elev= 25
       0  743.69       9  743.34    17.9  742.68    26.9  741.75    35.9  740.33
    44.8  738.71    53.8  737.22    63.5  735.03    73.2  732.02    82.9  730.14
    92.6  729.58   102.3  729.52     112  730.02   121.8  731.03   124.1  731.34
   131.5  732.32   139.1  733.35   141.2  733.63   150.9  736.32   159.4  741.12
   167.9  747.64   176.5  754.41     185  761.23   193.5  767.72     202  773.44
#Mann= 3 , 0 , 0
       0     .08       0   124.1    .045       0   139.1      .1       0
Bank Sta=124.1,139.1
XS Rating Curve= 0 ,0
Exp/Cntr=0.3,0.1

Type RM Length L Ch R = 1 ,32606.1 ,150.6,125.7,100.5
XS GIS Cut Line= 5
     1760071.647      473830.437     1760102.897      473858.215
     1760198.383      473911.166     1760234.841      473920.715
     1760299.077      473904.222
#Sta/Elev= 26
       0  737.35     8.4  736.83    25.1   734.8    33.4  734.05    41.8  733.71
      60  733.17    69.1  732.69    78.2  731.94    87.3  730.51    96.4  728.57
   105.5  727.39   109.8  727.73   114.6  728.12   124.8  729.15   132.8  729.78
   141.9   731.2     151  733.98   160.4  737.59   169.8   740.6   179.3  742.79
   188.7  744.32   217.1  749.28   226.6  750.73   236.1  752.06   245.5  753.62
     255  755.81
#Mann= 3 , 0 , 0
       0     .07       0   109.8    .045       0   124.8      .1       0
Bank Sta=109.8,124.8
XS Rating Curve= 0 ,0
Exp/Cntr=0.3,0.1

Type RM Length L Ch R = 1 ,32480.4 ,37.4,37.1,36.6
XS GIS Cut Line= 2
     1760037.048      474029.277     1760183.533      473941.387
#Sta/Elev= 21
       0  753.36     9.5  747.64      19  741.59    28.5  736.02      38   732.1
    47.4  731.01    56.9  730.39    66.4   728.6    70.1  728.24    75.9  727.68
    85.1  728.14    85.4  728.16    94.9  729.84   104.4  730.67   113.9  730.94
   123.4  731.21   132.9  731.59   142.4   732.2   151.8  732.87   161.3  733.68
   170.8   734.6
#Mann= 3 , 0 , 0
       0      .1       0    70.1    .045       0    85.1      .1       0
Bank Sta=70.1,85.1
XS Rating Curve= 0 ,0
Exp/Cntr=0.3,0.1

Type RM Length L Ch R = 1 ,32443.3 ,24.6,37.1,49.9
XS GIS Cut Line= 2
     1760042.474      474065.085     1760188.958      473977.194
#Sta/Elev= 21
       0  751.81     9.5  745.32      19  738.69    28.5  733.17      38  730.55
    47.4  729.84    56.9  729.21    66.4  727.59    67.9   727.4    75.9  726.36
    82.9  727.44    85.4  727.83    94.9  729.12   104.4  729.98   113.9  730.55
   123.4  731.24   132.9  731.78   142.4  732.13   151.8   732.6   161.3   733.5
   170.8   734.9
#Mann= 3 , 0 , 0
       0      .1       0    67.9    .045       0    82.9      .1       0
Bank Sta=67.9,82.9
XS Rating Curve= 0 ,0
Exp/Cntr=0.3,0.1

Type RM Length L Ch R = 1 ,32406.2 ,289.2,286.1,282.3
XS GIS Cut Line= 3
     1760050.069       474077.02       1760069.6         474064.
     1760260.573      474060.744
#Sta/Elev= 26
       0  746.28     7.8  740.75    15.6  735.81    23.5  731.72      33  729.33
    42.6  729.43    52.1  727.76    55.6  727.24    61.7  726.32    70.6  727.28
    71.2  727.35    80.8  729.54    90.3  731.02    99.9  731.27   109.4  731.52
     119  731.83   128.5  732.21   138.1  732.83   147.6  733.64   157.2  734.44
   166.7  735.35   176.3  736.62   185.8  738.64   195.4  741.58   204.9   745.2
   214.5  749.05
#Mann= 3 , 0 , 0
       0      .1       0    55.6    .045       0    70.6      .1       0
Bank Sta=55.6,70.6
XS Rating Curve= 0 ,0
Exp/Cntr=0.3,0.1

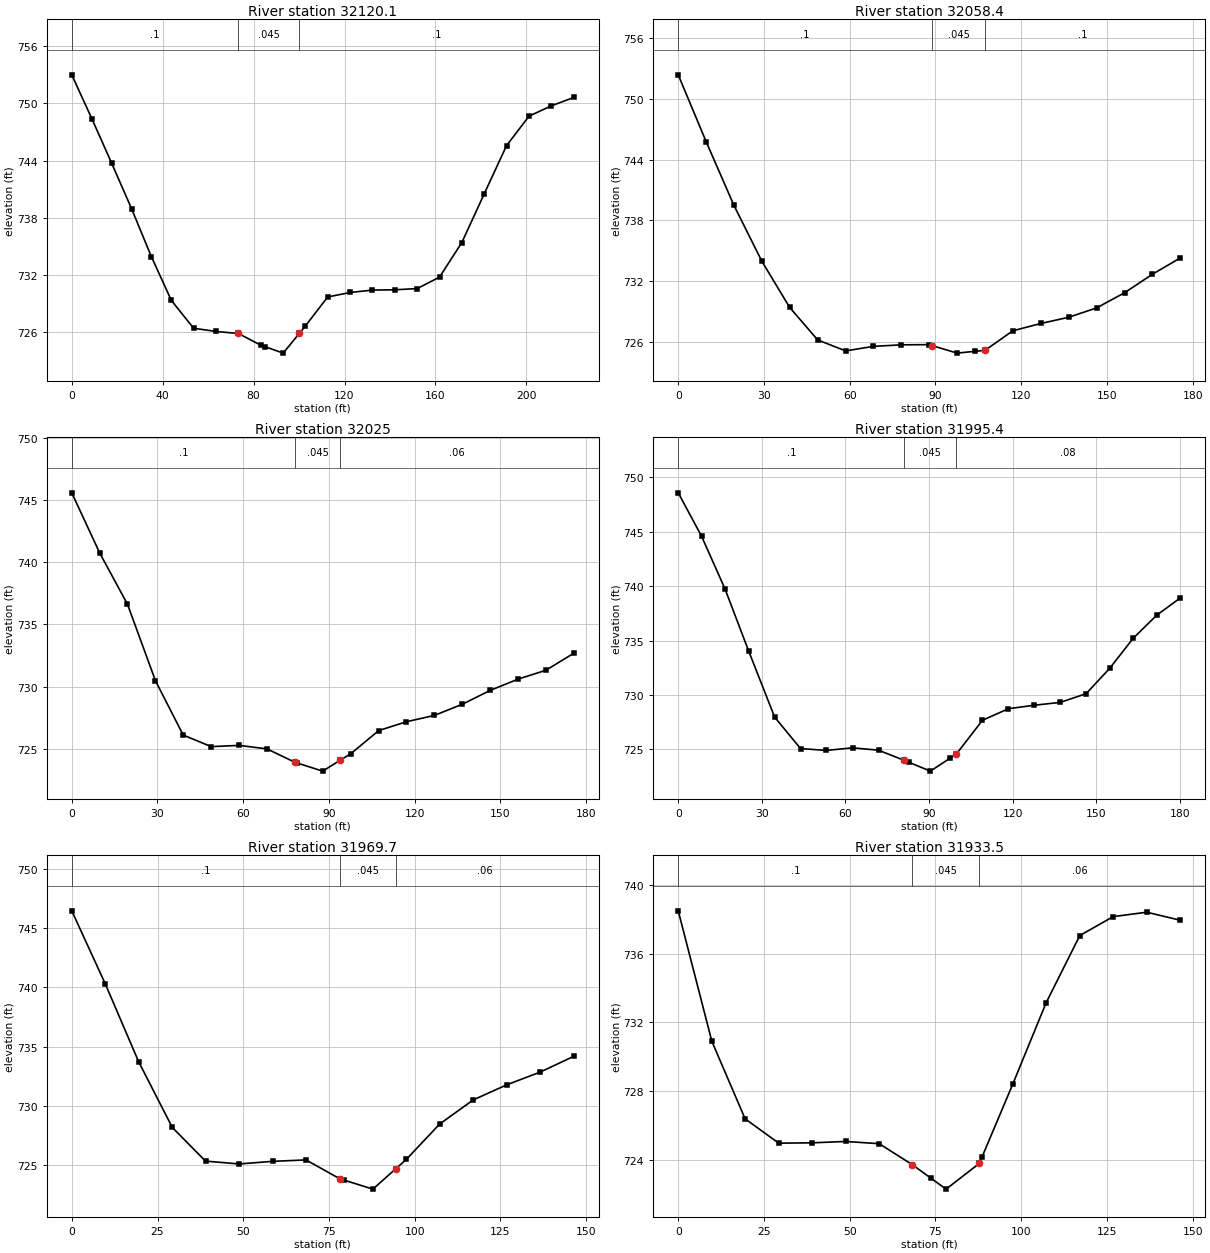
Type RM Length L Ch R = 1 ,32120.1 ,62,61.7,61.4
XS GIS Cut Line= 4
     1760048.209      474366.027     1760090.744      474355.611
     1760207.063      474335.645     1760260.883       474311.34
#Sta/Elev= 26
       0  752.99     8.8  748.41    17.5  743.75    26.3  738.96      35  733.94
    43.8  729.34    53.6  726.42    63.5  726.08    73.3  725.87    83.1  724.65
    85.1  724.48      93  723.81   100.1  725.87   102.8  726.66   112.6   729.7
   122.5  730.17   132.3  730.42   142.1  730.45     152  730.58   161.8  731.78
   171.6   735.4   181.5  740.53   191.3  745.57   201.2  748.66     211  749.74
   220.9  750.62
#Mann= 3 , 0 , 0
       0      .1       0    73.3    .045       0   100.1      .1       0
Bank Sta=73.3,100.1
XS Rating Curve= 0 ,0
Exp/Cntr=0.3,0.1

Type RM Length L Ch R = 1 ,32058.4 ,33.4,33.4,33.4
XS GIS Cut Line= 2
     1760053.418      474425.923     1760226.161      474393.805
#Sta/Elev= 21
       0  752.37     9.8  745.74    19.5  739.46    29.3  733.92      39  729.38
    48.8  726.16    58.6  725.08    68.3  725.53    78.1  725.68    87.8   725.7
    88.8  725.61    97.6  724.86   103.8  725.04   107.4  725.14   117.1  727.07
   126.9  727.79   136.7  728.41   146.4  729.33   156.2  730.83   165.9  732.65
   175.7  734.27
#Mann= 3 , 0 , 0
       0      .1       0    88.8    .045       0   107.4      .1       0
Bank Sta=88.8,107.4
XS Rating Curve= 0 ,0
Exp/Cntr=0.3,0.1

Type RM Length L Ch R = 1 ,32025   ,31.8,29.6,27.3
XS GIS Cut Line= 2
     1760068.175      474457.173     1760240.918      474425.055
#Sta/Elev= 21
       0  745.58     9.8  740.73    19.5  736.62    29.3  730.46      39   726.1
    48.8  725.17    58.6  725.27    68.3  724.99    78.1  723.91    78.9  723.85
    87.8   723.2    93.9  724.07    97.6  724.59   107.4  726.46   117.1  727.17
   126.9  727.68   136.7  728.58   146.4  729.69   156.2   730.6   165.9  731.31
   175.7  732.68
#Mann= 3 , 0 , 0
       0      .1       0    78.1    .045       0    93.9     .06       0
Bank Sta=78.1,93.9
XS Rating Curve= 0 ,0
Exp/Cntr=0.3,0.1

Type RM Length L Ch R = 1 ,31995.4 ,28.2,25.8,23.3
XS GIS Cut Line= 4
     1760072.515      474495.368      1760096.82      474488.423
      1760213.14      474454.569     1760245.258      474464.986
#Sta/Elev= 23
       0  748.56     8.4  744.56    16.8  739.73    25.3  734.02    34.6  727.97
    43.9  725.08    53.2  724.91    62.6  725.15    71.9  724.93    81.2  723.99
    82.7  723.83    90.5  723.01    97.7  724.22    99.8  724.57   109.2  727.68
   118.5  728.74   127.8  729.06   137.1  729.32   146.4  730.12   154.9  732.46
   163.3  735.21   171.8  737.34   180.2  738.91
#Mann= 3 , 0 , 0
       0      .1       0    81.2    .045       0    99.8     .08       0
Bank Sta=81.2,99.8
XS Rating Curve= 0 ,0
Exp/Cntr=0.3,0.1

Type RM Length L Ch R = 1 ,31969.7 ,36.2,36.2,36.2
XS GIS Cut Line= 2
     1760084.668      474528.354     1760220.084      474472.798
#Sta/Elev= 18
       0  746.44     9.8  740.27    19.5  733.73    29.3   728.2      39  725.36
    48.8  725.12    58.6  725.34    68.3  725.46    78.1  723.88    79.5  723.75
    87.8     723    94.5  724.72    97.6  725.52   107.3  728.49   117.1  730.52
   126.8  731.78   136.6  732.86   146.4  734.19
#Mann= 3 , 0 , 0
       0      .1       0    78.1    .045       0    94.5     .06       0
Bank Sta=78.1,94.5
XS Rating Curve= 0 ,0
Exp/Cntr=0.3,0.1

Type RM Length L Ch R = 1 ,31933.5 ,90.2,90.8,91.3
XS GIS Cut Line= 2
     1760098.557       474561.34     1760233.973      474505.784
#Sta/Elev= 18
       0  738.51     9.8   730.9    19.5  726.38    29.3  724.96      39  724.98
    48.8  725.06    58.6  724.93    68.3   723.7    73.6  722.93    78.1  722.28
    87.8  723.78    88.6  724.16    97.6  728.43   107.3  733.16   117.1  737.07
   126.8  738.17   136.6  738.43   146.4  737.96
#Mann= 3 , 0 , 0
       0      .1       0    68.3    .045       0    87.8     .06       0
Bank Sta=68.3,87.8
XS Rating Curve= 0 ,0
Exp/Cntr=0.3,0.1

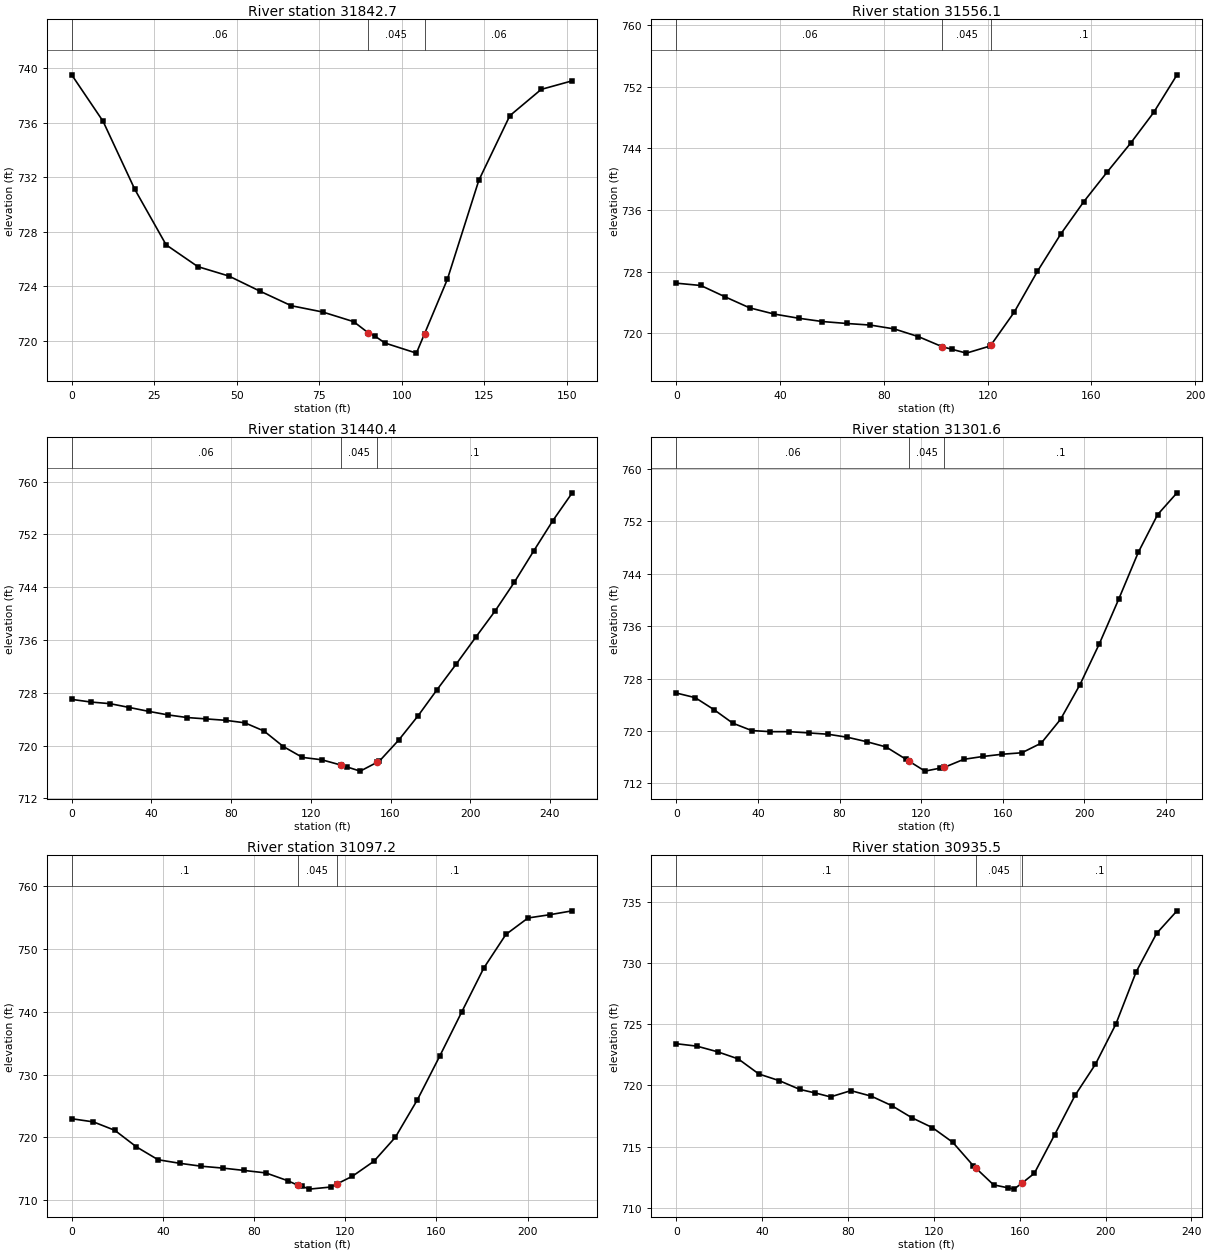
Type RM Length L Ch R = 1 ,31842.7 ,285.5,286.7,288.1
XS GIS Cut Line= 3
     1760108.105      474649.881     1760144.563      474638.597
     1760250.466      474597.798
#Sta/Elev= 20
       0  739.53     9.5  736.12    19.1  731.13    28.6  727.05    38.2  725.45
    47.6  724.76    57.1  723.64    66.5  722.58      76  722.12    85.4  721.41
   89.71  720.61    91.9  720.34    94.9  719.84   104.4   719.1   106.9  720.54
   113.8  724.53   123.3  731.78   132.7  736.53   142.2  738.46   151.6  739.09
#Mann= 3 , 0 , 0
       0     .06       0   89.71    .045       0   106.9     .06       0
Bank Sta=89.71,106.9
XS Rating Curve= 0 ,0
Exp/Cntr=0.3,0.1

Type RM Length L Ch R = 1 ,31556.1 ,108.4,115.7,119.9
XS GIS Cut Line= 4
     1760196.647      474906.826     1760243.522      474902.486
     1760322.515      474876.444     1760383.279      474860.819
#Sta/Elev= 24
       0   726.5     9.4   726.2    18.8  724.72    28.2   723.3    37.7  722.49
    47.1  721.95    56.3  721.52    65.6  721.27    74.8  721.06      84  720.56
    93.3  719.56   102.5  718.25   106.2  717.92   111.8  717.42     121  718.35
   121.2  718.44   130.2  722.72   139.2  728.05   148.2  732.89   157.1   737.1
   166.1  740.94   175.1  744.67     184  748.66     193  753.55
#Mann= 3 , 0 , 0
       0     .06       0   102.5    .045       0   121.2      .1       0
Bank Sta=102.5,121.2
XS Rating Curve= 0 ,0
Exp/Cntr=0.3,0.1

Type RM Length L Ch R = 1 ,31440.4 ,137.9,138.7,141.9
XS GIS Cut Line= 3
     1760200.987      474987.555      1760365.05      474989.291
      1760440.57      474945.888
#Sta/Elev= 29
       0  727.01     9.6  726.61    19.3  726.36      29  725.78    38.6   725.2
    48.3  724.66    57.9  724.26    67.6  724.05    77.2  723.84    86.9  723.46
    96.5  722.22   106.2  719.87   115.8  718.22   125.5  717.86   135.1  717.06
   138.3  716.76   144.8  716.14   153.3  717.48   154.4  717.65   164.1  720.84
   173.8  724.51   183.4   728.5   193.1  732.41   202.8  736.44   212.5  740.41
   222.1  744.74   231.8  749.47   241.5  754.11   251.2  758.31
#Mann= 3 , 0 , 0
       0     .06       0   135.1    .045       0   153.3      .1       0
Bank Sta=135.1,153.3
XS Rating Curve= 0 ,0
Exp/Cntr=0.3,0.1

Type RM Length L Ch R = 1 ,31301.6 ,204.4,204.5,204.5
XS GIS Cut Line= 3
     1760206.195      475100.402     1760257.411      475121.236
     1760447.515      475127.312
#Sta/Elev= 29
       0  725.79     9.2  725.09    18.4  723.26    27.6   721.2    36.9  720.07
    46.1   719.9    55.3   719.9    64.8  719.71    74.3  719.51    83.8  719.05
    93.3  718.37   102.8  717.57   112.4  715.72   114.2  715.37   121.9  713.88
   129.2  714.33   131.4  714.46   140.9  715.68   150.4  716.12   159.9  716.46
   169.4  716.68   178.9  718.15   188.4  721.79   197.9  727.07   207.4   733.3
     217  740.18   226.5  747.25     236  753.02   245.5  756.34
#Mann= 3 , 0 , 0
       0     .06       0   114.2    .045       0   131.4      .1       0
Bank Sta=114.2,131.4
XS Rating Curve= 0 ,0
Exp/Cntr=0.3,0.1

Type RM Length L Ch R = 1 ,31097.2 ,118.7,161.7,204
XS GIS Cut Line= 3
     1760188.719      475321.641     1760330.646      475326.849
     1760389.239       475377.63
#Sta/Elev= 27
       0  722.98     9.5  722.48    18.9  721.14    28.4   718.5    37.9  716.45
    47.3  715.89    56.8  715.42    66.3  715.12    75.8  714.74    85.2  714.35
    94.7  713.12   99.42  712.36   101.2   712.2   104.2  711.77   113.6   712.1
   116.2  712.57   123.1  713.81   132.6  716.21     142  720.03   151.7  726.02
   161.4   732.9   171.1  739.97   180.8  746.98   190.5  752.33   200.2  754.95
   209.9  755.48   219.6  756.09
#Mann= 3 , 0 , 0
       0      .1       0   99.42    .045       0   116.2      .1       0
Bank Sta=99.42,116.2
XS Rating Curve= 0 ,0
Exp/Cntr=0.3,0.1

Type RM Length L Ch R = 1 ,30935.5 ,65.6,64.2,65.6
XS GIS Cut Line= 4
      1760190.57      475343.458     1760222.688      475391.201
     1760231.369      475402.486     1760255.675      475562.208
#Sta/Elev= 29
       0   723.4     9.6   723.2    19.2  722.74    28.8  722.16    38.4  720.93
      48  720.38    57.5  719.67    64.7  719.38    71.8  719.06    81.3  719.57
    90.8  719.12   100.3  718.35   109.8  717.35   119.3  716.55   128.8  715.35
   138.3  713.45   139.7  713.22   147.8  711.88   154.7  711.63   157.3  711.53
   161.2  712.04   166.8  712.82   176.3  715.98   185.8  719.19   195.3  721.73
   204.8     725   214.3  729.28   223.8  732.41   233.3  734.25
#Mann= 3 , 0 , 0
       0      .1       0   139.7    .045       0   161.2      .1       0
Bank Sta=139.7,161.2
XS Rating Curve= 0 ,0
Exp/Cntr=0.3,0.1

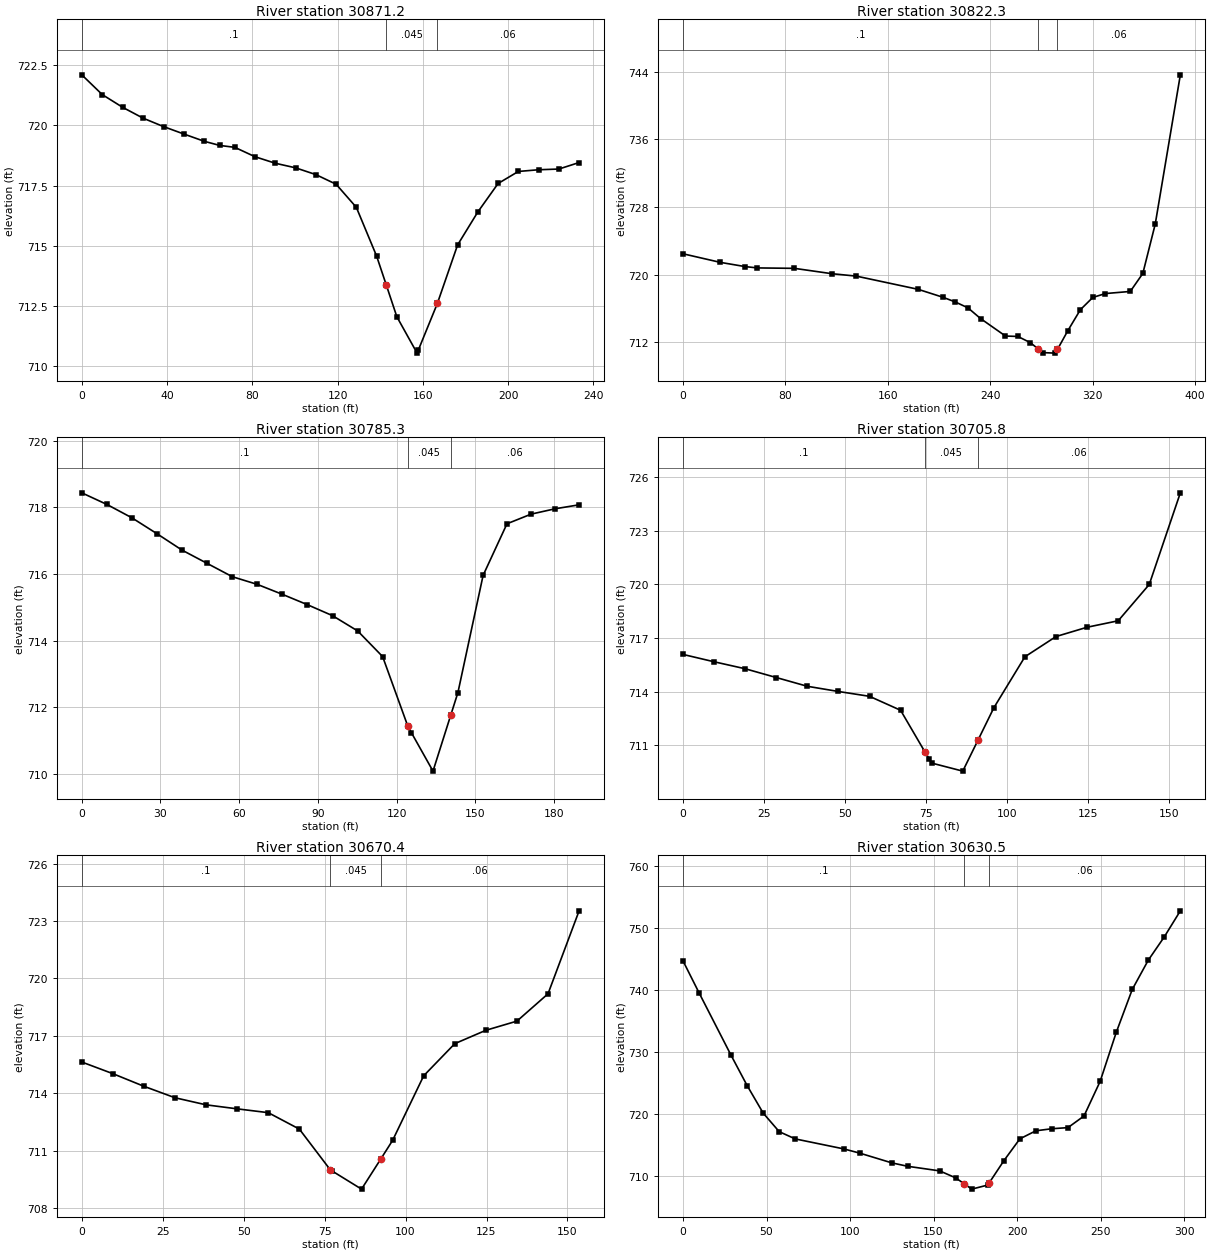
Type RM Length L Ch R = 1 ,30871.2 ,63.9,48.9,32.4
XS GIS Cut Line= 4
     1760161.925      475398.145     1760194.043      475445.888
     1760202.723      475457.173     1760227.029      475616.895
#Sta/Elev= 28
       0   722.1     9.6  721.28    19.2  720.75    28.8   720.3    38.4  719.95
      48  719.64    57.5  719.34    64.7  719.17    71.8  719.09    81.3   718.7
    90.8  718.43   100.3  718.24   109.8  717.96   119.3  717.56   128.8   716.6
   138.3  714.58   142.8  713.39   147.8  712.06   157.3  710.55   157.8  710.66
   166.8  712.61   176.3  715.04   185.8  716.41   195.3  717.59   204.8  718.09
   214.3  718.16   223.8  718.19   233.3  718.46
#Mann= 3 , 0 , 0
       0      .1       0   142.8    .045       0   166.8     .06       0
Bank Sta=142.8,166.8
XS Rating Curve= 0 ,0
Exp/Cntr=0.3,0.1

Type RM Length L Ch R = 1 ,30822.3 ,63.4,37,13.2
XS GIS Cut Line= 5
     1759989.182      475445.888     1760124.588      475446.762
     1760153.244      475497.104     1760222.688      475636.861
     1760261.751      475635.993
#Sta/Elev= 27
       0  722.48      29  721.47    48.4  720.97      58  720.81      87  720.76
   116.1  720.13   135.4  719.84   183.7  718.28   203.1  717.34   212.8  716.78
   222.6  716.09   232.4  714.83   251.9  712.76   261.6  712.71   271.4  711.97
   277.5  711.23   281.1   710.8   290.9  710.74   292.5  711.18   300.6  713.39
   310.4  715.87   320.1  717.32   329.9  717.78   349.4  718.03   359.2  720.16
   368.9     726   388.5  743.63
#Mann= 3 , 0 , 0
       0      .1       0   277.5    .045       0   292.5     .06       0
Bank Sta=277.5,292.5
XS Rating Curve= 0 ,0
Exp/Cntr=0.3,0.1

Type RM Length L Ch R = 1 ,30785.3 ,84.8,79.4,71
XS GIS Cut Line= 3
     1760049.945      475607.347     1760202.723      475615.159
     1760224.425      475644.673
#Sta/Elev= 23
       0  718.44     9.6  718.09    19.1  717.69    28.7  717.21    38.2  716.72
    47.8  716.32    57.4  715.92    66.9  715.69    76.5  715.39      86  715.08
    95.6  714.75   105.2  714.29   114.7  713.52   124.3  711.43   125.7  711.23
   133.9  710.08   140.7  711.77   143.4  712.44     153  715.96   162.1  717.51
   171.3   717.8   180.4  717.96   189.6  718.08
#Mann= 3 , 0 , 0
       0      .1       0   124.3    .045       0   140.7     .06       0
Bank Sta=124.3,140.7
XS Rating Curve= 0 ,0
Exp/Cntr=0.3,0.1

Type RM Length L Ch R = 1 ,30705.8 ,35.4,35.4,35.4
XS GIS Cut Line= 2
     1760090.744      475708.041     1760241.786      475680.263
#Sta/Elev= 20
       0  716.08     9.6  715.67    19.2  715.28    28.8  714.79    38.4   714.3
      48  714.01    57.6  713.74    67.2  712.96   74.69  710.64    76.1  710.23
    76.8  710.01    86.4  709.56    91.1  711.29      96   713.1   105.6  715.95
   115.2  717.08   124.8   717.6   134.4  717.96     144  719.99   153.6  725.11
#Mann= 3 , 0 , 0
       0      .1       0   74.69    .045       0    91.1     .06       0
Bank Sta=74.69,91.1
XS Rating Curve= 0 ,0
Exp/Cntr=0.3,0.1

Type RM Length L Ch R = 1 ,30670.4 ,35.3,40,44.3
XS GIS Cut Line= 2
      1760088.14      475743.631     1760239.182      475715.854
#Sta/Elev= 19
       0  715.63     9.6  715.02    19.2  714.36    28.8  713.76    38.4  713.39
      48  713.18    57.6  712.98    67.2  712.12    76.8  709.98    77.4  709.92
    86.4  708.98    92.4  710.57      96  711.53   105.6  714.91   115.2  716.59
   124.8  717.29   134.4  717.77     144   719.2   153.6  723.54
#Mann= 3 , 0 , 0
       0      .1       0    76.8    .045       0    92.4     .06       0
Bank Sta=76.8,92.4
XS Rating Curve= 0 ,0
Exp/Cntr=0.3,0.1

Type RM Length L Ch R = 1 ,30630.5 ,26.9,26.8,26.8
XS GIS Cut Line= 2
     1759990.918      475765.333     1760288.661      475769.673
#Sta/Elev= 29
       0  744.71     9.6  739.57    28.8  729.49    38.4  724.62      48  720.19
    57.6   717.2    67.2  716.03    96.1  714.43   105.7  713.75   124.9  712.18
   134.5  711.62   153.7  710.88   163.3  709.75   168.4  708.79   172.9  707.94
   182.5   708.6   183.4  708.97   192.1  712.51   201.7  716.04   211.3  717.34
   220.9  717.67   230.5  717.85   240.1  719.72   249.8  725.32   259.4  733.18
     269  740.11   278.6  744.83   288.2  748.59   297.8  752.78
#Mann= 3 , 0 , 0
       0      .1       0   168.4    .045       0   183.4     .06       0
Bank Sta=168.4,183.4
XS Rating Curve= 0 ,0
Exp/Cntr=0.3,0.1

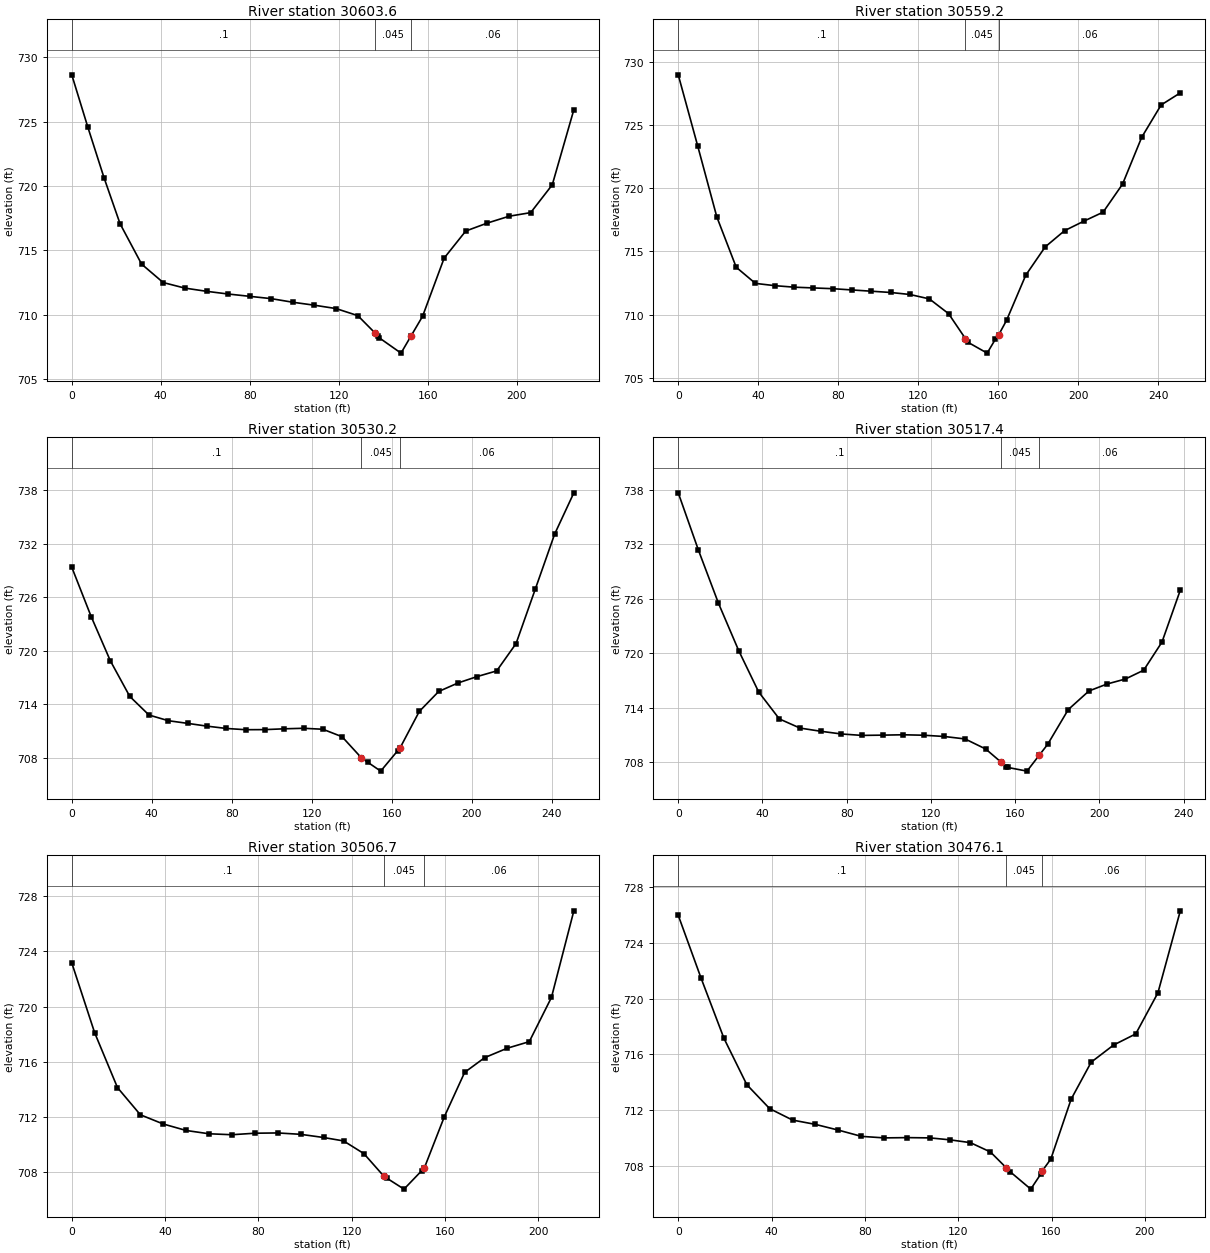
Type RM Length L Ch R = 1 ,30603.6 ,43.7,44.4,45.2
XS GIS Cut Line= 3
       1760021.3      475787.034     1760042.133      475793.111
     1760246.126      475795.715
#Sta/Elev= 28
       0  728.63     7.2  724.58    14.5  720.64    21.7  717.07    31.4  713.93
    41.1   712.5    50.8  712.07    60.6  711.82    70.3  711.61      80  711.43
    89.7  711.25    99.4  710.97   109.1  710.74   118.8  710.48   128.6  709.93
   136.4  708.57   137.5  708.34   138.3   708.2     148  707.02   152.5  708.35
   157.7  709.88   167.4   714.4   177.1   716.5   186.8  717.12   196.6  717.65
   206.3  717.93     216  720.09   225.7  725.92
#Mann= 3 , 0 , 0
       0      .1       0   136.4    .045       0   152.5     .06       0
Bank Sta=136.4,152.5
XS Rating Curve= 0 ,0
Exp/Cntr=0.3,0.1

Type RM Length L Ch R = 1 ,30559.2 ,29,29,29
XS GIS Cut Line= 2
     1760016.091      475832.173     1760266.959      475843.458
#Sta/Elev= 30
       0  729.01     9.7  723.39    19.3  717.74      29  713.75    38.6  712.47
    48.3  712.29      58  712.17    67.6  712.11    77.3  712.05    86.9  711.95
    96.6  711.85   106.2  711.75   115.9  711.59   125.6  711.24   135.2  710.07
   143.6   708.1   144.9   707.8   154.5  706.94   158.6  708.04  160.23  708.38
   164.2  709.54   173.8  713.12   183.5  715.36   193.2  716.65   202.8   717.4
   212.5  718.12   222.2  720.34   231.8  724.06   241.5  726.62   251.1  727.58
#Mann= 3 , 0 , 0
       0      .1       0   143.6    .045       0  160.23     .06       0
Bank Sta=143.6,160.23
XS Rating Curve= 0 ,0
Exp/Cntr=0.3,0.1

Type RM Length L Ch R = 1 ,30530.2 ,15.6,12.8,10.1
XS GIS Cut Line= 2
     1760014.355      475860.819     1760265.223      475872.104
#Sta/Elev= 29
       0  729.37     9.7  723.83    19.3  718.86      29  714.87    38.6  712.78
    48.3  712.14      58  711.84    67.6  711.53    77.3  711.27    86.9  711.13
    96.6  711.14   106.2  711.23   115.9  711.29   125.6  711.18   135.2  710.34
   144.9  707.96     148  707.48   154.5  706.48     163  708.77   164.2  709.09
   173.8  713.18   183.5  715.42   193.2  716.38   202.8   717.1   212.5  717.73
   222.2   720.8   231.8   726.9   241.5  733.09   251.1  737.72
#Mann= 3 , 0 , 0
       0      .1       0   144.9    .045       0   164.2     .06       0
Bank Sta=144.9,164.2
XS Rating Curve= 0 ,0
Exp/Cntr=0.3,0.1

Type RM Length L Ch R = 1 ,30517.4 ,11.7,10.7,9.6
XS GIS Cut Line= 4
     1760007.411      475892.069     1760045.605      475890.333
     1760201.855       475878.18     1760245.258       475878.18
#Sta/Elev= 29
       0  737.69     9.6  731.36    19.1  725.51    28.7  720.29    38.2  715.72
      48  712.75    57.8  711.74    67.6  711.39    77.4  711.09    87.2  710.93
      97  710.96   106.8     711   116.6  710.95   126.4  710.81   136.2  710.54
     146  709.43  153.45  707.95   155.8  707.43   156.4   707.4   165.6  706.99
   171.4  708.74   175.4  709.94   185.2  713.78     195  715.83   203.6   716.6
   212.3  717.15     221  718.12   229.7  721.23   238.4  726.96
#Mann= 3 , 0 , 0
       0      .1       0  153.45    .045       0   171.4     .06       0
Bank Sta=153.45,171.4
XS Rating Curve= 0 ,0
Exp/Cntr=0.3,0.1

Type RM Length L Ch R = 1 ,30506.7 ,30.7,30.7,30.7
XS GIS Cut Line= 4
     1760035.188      475929.395     1760137.619      475895.541
     1760206.195      475886.861      1760244.39      475886.861
#Sta/Elev= 26
       0  723.17     9.8   718.1    19.6  714.11    29.4  712.14    39.2  711.47
      49     711    58.8  710.76    68.6  710.69    78.5   710.8    88.3  710.82
    98.1  710.72   107.9  710.49   116.5  710.24   125.2  709.32   133.8  707.67
     135  707.54   142.4  706.74     150  708.08   151.1  708.27   159.7     712
   168.4  715.22     177  716.29   186.6  716.97   196.1  717.45   205.6  720.66
   215.2  726.95
#Mann= 3 , 0 , 0
       0      .1       0   133.8    .045       0   151.1     .06       0
Bank Sta=133.8,151.1
XS Rating Curve= 0 ,0
Exp/Cntr=0.3,0.1

Type RM Length L Ch R = 1 ,30476.1 ,73,77.2,81.2
XS GIS Cut Line= 4
     1760032.584      475960.645     1760135.015      475926.791
     1760203.591      475918.111     1760241.786      475918.111
#Sta/Elev= 27
       0  725.99     9.8  721.47    19.6  717.15    29.4  713.82    39.2   712.1
      49  711.28    58.8  710.97    68.6  710.56    78.5  710.11    88.3     710
    98.1  710.02   107.9     710   116.5  709.86   125.2  709.66   133.8  708.99
   140.5  707.87   142.4  707.55   151.1  706.32   155.5  707.43  156.11  707.65
   159.7  708.48   168.4  712.78     177  715.44   186.6  716.67   196.1  717.47
   205.6  720.42   215.2  726.31
#Mann= 3 , 0 , 0
       0      .1       0   140.5    .045       0  156.11     .06       0
Bank Sta=140.5,156.11
XS Rating Curve= 0 ,0
Exp/Cntr=0.3,0.1