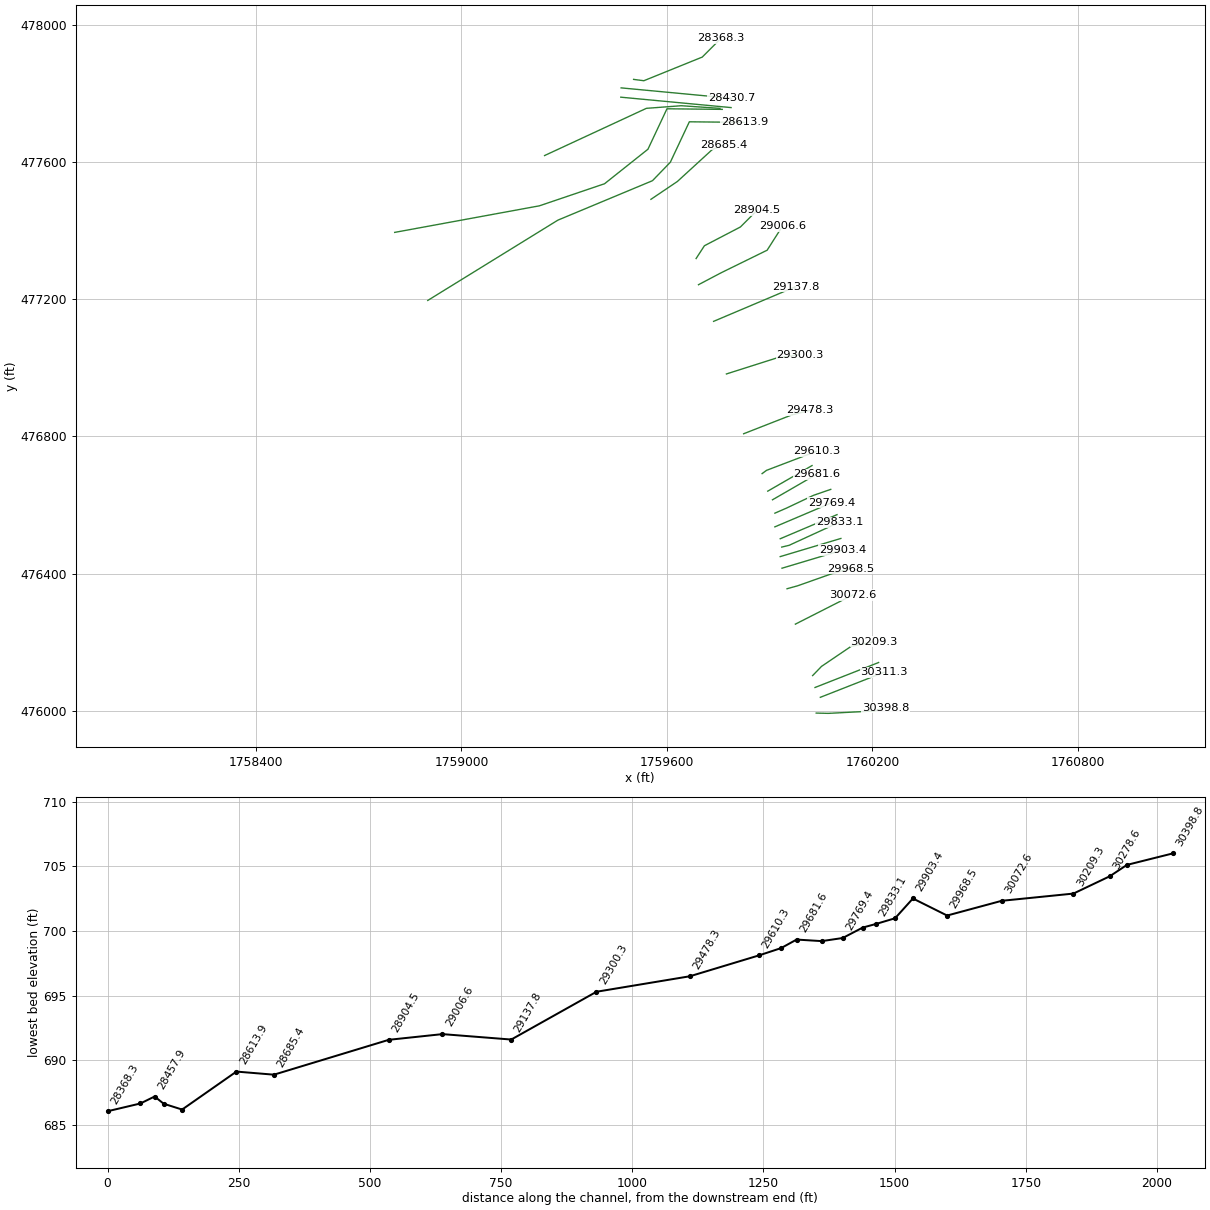
HEC-RAS study TRACEFORK.prj: TRACEFORK

--- TRACEFORK.g01 (geometry) --- (continued)

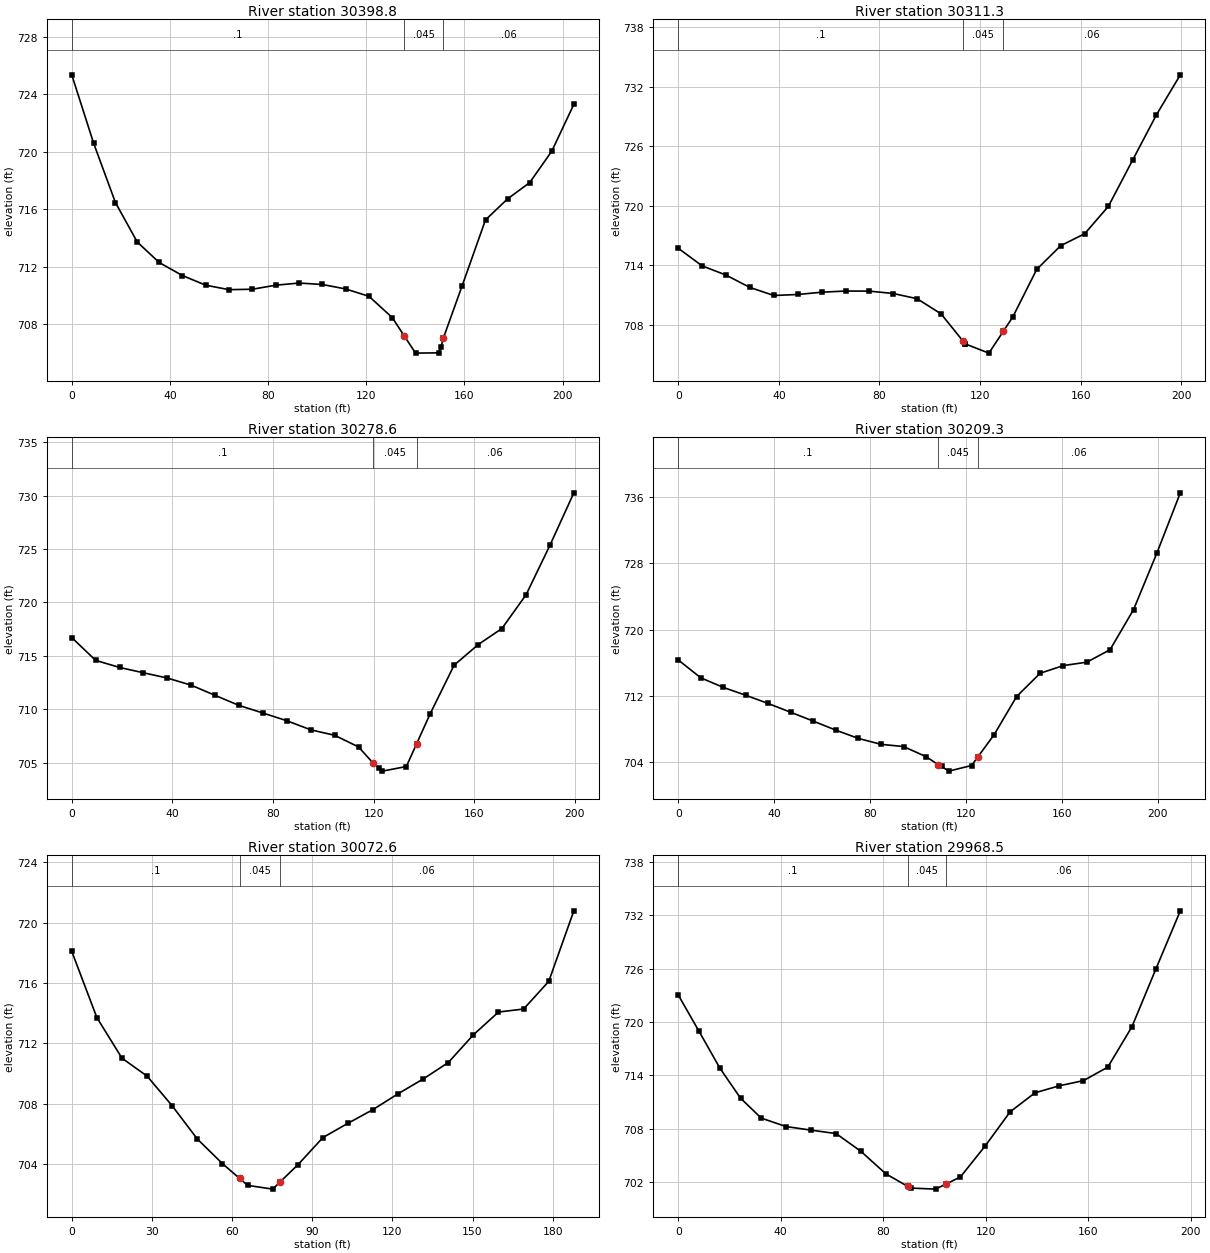
Type RM Length L Ch R = 1 ,30398.8 ,80.2,87.5,94.8
XS GIS Cut Line= 4
     1760036.057      475992.763     1760071.647      475991.895
     1760204.459       475998.84     1760239.182      476008.388
#Sta/Elev= 26
       0  725.35     8.9   720.6    17.8  716.47    26.7  713.73    35.6  712.31
    45.1   711.4    54.6  710.73    64.1  710.42    73.6  710.45    83.1  710.73
    92.6  710.88   102.1  710.78   111.6  710.47   121.1  709.96   130.6  708.48
   135.4  707.23   140.1  706.01   149.6  706.03   150.4  706.42  151.46  707.07
   159.1   710.7   168.6  715.27   177.6  716.73   186.6  717.86   195.6  720.04
   204.6   723.3
#Mann= 3 , 0 , 0
       0      .1       0   135.4    .045       0  151.46     .06       0
Bank Sta=135.4,151.46
XS Rating Curve= 0 ,0
Exp/Cntr=0.3,0.1

Type RM Length L Ch R = 1 ,30311.3 ,32.6,32.7,32.6
XS GIS Cut Line= 2
     1760048.209       476038.77     1760233.973      476111.687
#Sta/Elev= 25
       0  715.71     9.5  713.93      19     713    28.5  711.75      38  710.94
    47.5  711.04      57  711.27    66.5  711.39      76  711.38    85.5  711.14
      95  710.61   104.5  709.08   113.2  706.34     114  706.06   114.2  706.04
   123.5  705.12   129.2  707.31     133  708.77   142.5  713.57     152  715.96
   161.6  717.18     171  719.94   180.6  724.59   190.1  729.18   199.6  733.22
#Mann= 3 , 0 , 0
       0      .1       0   113.2    .045       0   129.2     .06       0
Bank Sta=113.2,129.2
XS Rating Curve= 0 ,0
Exp/Cntr=0.3,0.1

Type RM Length L Ch R = 1 ,30278.6 ,64.4,69.3,74.4
XS GIS Cut Line= 2
     1760032.584      476067.416     1760218.348      476140.333
#Sta/Elev= 25
       0  716.72     9.5  714.59      19  713.93    28.5  713.43      38  712.94
    47.5  712.27      57  711.32    66.5  710.38      76  709.67    85.5  708.95
      95   708.1   104.5  707.59     114   706.5  119.93  704.96   122.1  704.57
   123.5  704.24     133  704.67   137.1   706.8   142.5  709.61     152  714.14
   161.6  716.07     171  717.57   180.6  720.72   190.1  725.35   199.6  730.25
#Mann= 3 , 0 , 0
       0      .1       0  119.93    .045       0   137.1     .06       0
Bank Sta=119.93,137.1
XS Rating Curve= 0 ,0
Exp/Cntr=0.3,0.1

Type RM Length L Ch R = 1 ,30209.3 ,139.5,136.7,133.8
XS GIS Cut Line= 4
      1760025.64      476102.138     1760051.682      476129.048
     1760137.619      476187.208     1760204.459      476201.097
#Sta/Elev= 26
       0  716.34     9.4  714.18    18.7  713.03    28.1  712.08    37.4  711.09
    46.9  710.02    56.3  708.95    65.8  707.85    75.2  706.85    84.6  706.14
      94  705.87   103.5  704.64   108.5  703.67   109.9  703.46   112.9   702.9
   122.4  703.58   124.9  704.57   131.8   707.3   141.2  711.92     151  714.73
   160.7  715.66   170.5  716.07   180.2  717.58     190  722.43   199.7  729.24
   209.5  736.54
#Mann= 3 , 0 , 0
       0      .1       0   108.5    .045       0   124.9     .06       0
Bank Sta=108.5,124.9
XS Rating Curve= 0 ,0
Exp/Cntr=0.3,0.1

Type RM Length L Ch R = 1 ,30072.6 ,104.7,104,101.7
XS GIS Cut Line= 2
     1759975.293      476252.312     1760142.827      476337.381
#Sta/Elev= 23
       0   718.1     9.4  713.71    18.8  711.02    28.2  709.83    37.6  707.86
      47  705.66    56.4  704.03    62.8  703.05    65.8  702.59    75.2  702.34
    77.8  702.79    84.6  703.95      94  705.76   103.3   706.7   112.7  707.61
   122.1  708.66   131.5  709.64   140.9  710.73   150.3  712.57   159.7  714.08
   169.1  714.28   178.5  716.11   187.9  720.79
#Mann= 3 , 0 , 0
       0      .1       0    62.8    .045       0    77.8     .06       0
Bank Sta=62.8,77.8
XS Rating Curve= 0 ,0
Exp/Cntr=0.3,0.1

Type RM Length L Ch R = 1 ,29968.5 ,68.6,65.2,63.2
XS GIS Cut Line= 4
     1759950.987      476355.611     1759982.237      476364.291
     1760082.932      476399.881     1760137.619      476414.638
#Sta/Elev= 24
       0  723.05     8.1  718.97    16.2  714.84    24.3  711.44    32.4  709.19
    42.1  708.24    51.8  707.84    61.6  707.45    71.3  705.45      81  702.92
    89.6   701.5    90.7  701.32   100.4   701.2   104.6  701.79   110.1  702.57
   119.8  706.07   129.5   709.9   139.2  712.04   148.7  712.83   158.1  713.41
   167.6  714.93     177  719.46   186.4     726   195.9  732.52
#Mann= 3 , 0 , 0
       0      .1       0    89.6    .045       0   104.6     .06       0
Bank Sta=89.6,104.6
XS Rating Curve= 0 ,0
Exp/Cntr=0.3,0.1

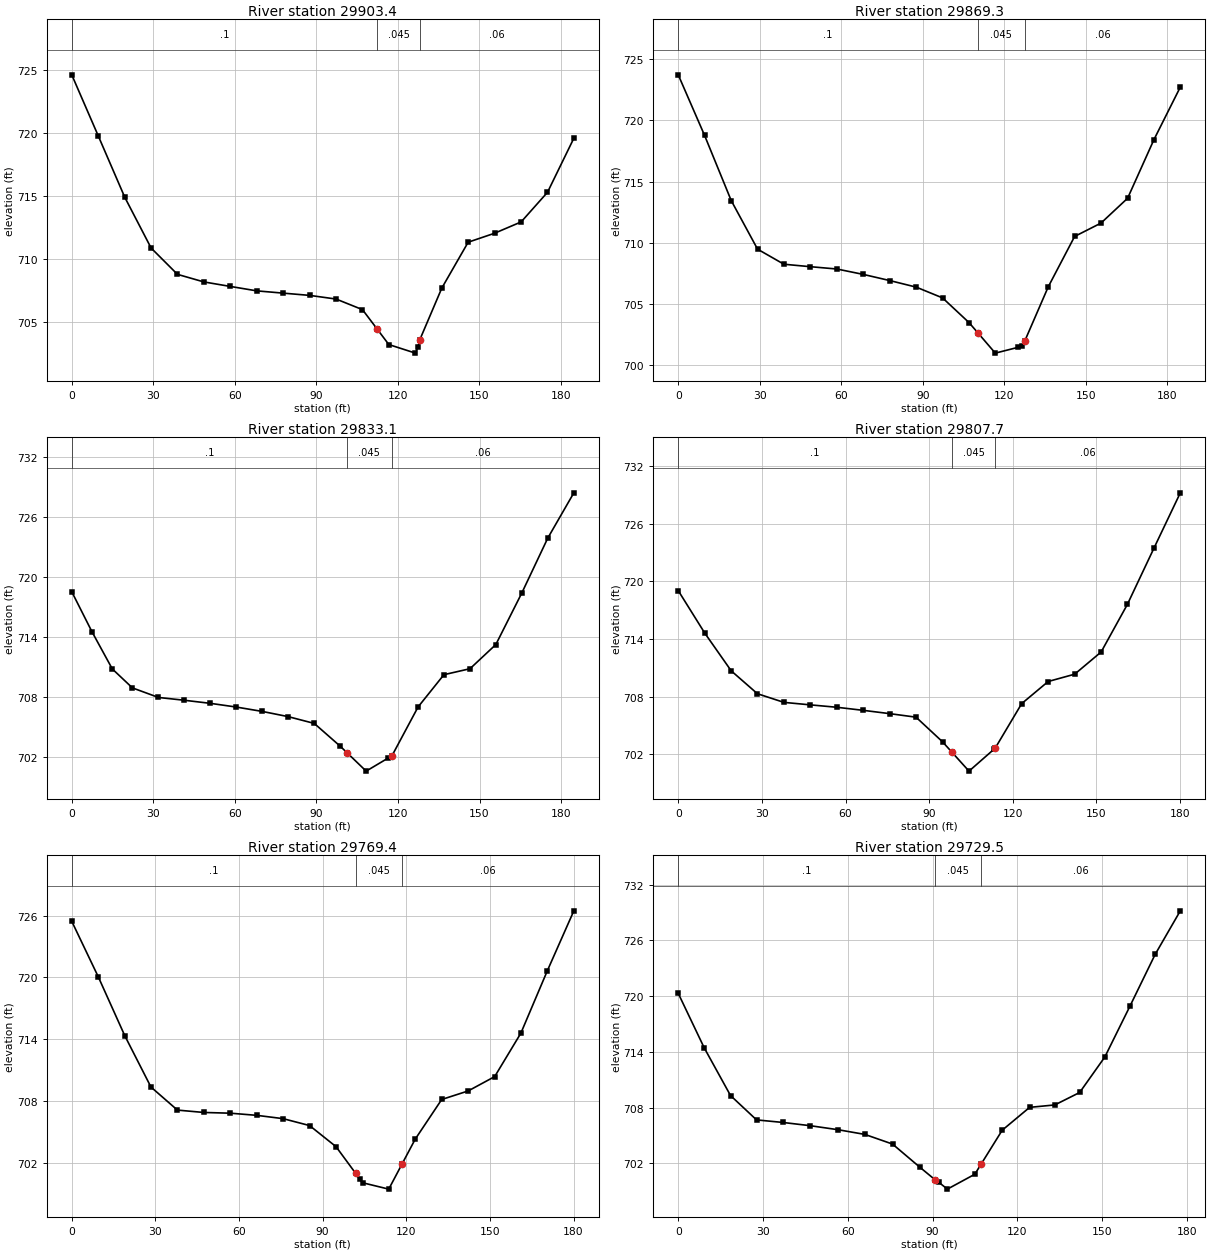
Type RM Length L Ch R = 1 ,29903.4 ,34,34,34
XS GIS Cut Line= 2
      1759936.23      476415.506     1760113.313      476468.458
#Sta/Elev= 23
       0   724.6     9.7  719.78    19.5  714.89    29.2  710.86    38.9  708.77
    48.6  708.17    58.4  707.81    68.1  707.46    77.8  707.28    87.6   707.1
    97.3  706.81     107  705.97   112.4  704.43   116.7   703.2   126.5  702.52
   127.4     703  128.08  703.57   136.2  707.68   145.9  711.32   155.6  712.03
   165.4  712.93   175.1  715.28   184.8  719.57
#Mann= 3 , 0 , 0
       0      .1       0   112.4    .045       0  128.08     .06       0
Bank Sta=112.4,128.08
XS Rating Curve= 0 ,0
Exp/Cntr=0.3,0.1

Type RM Length L Ch R = 1 ,29869.3 ,33.1,36.2,39.4
XS GIS Cut Line= 2
     1759931.022      476449.361     1760108.105      476502.312
#Sta/Elev= 23
       0  723.72     9.7  718.77    19.5  713.45    29.2  709.48    38.9  708.25
    48.6  708.05    58.4  707.86    68.1  707.42    77.8  706.92    87.6  706.38
    97.3   705.5     107  703.49   110.2  702.67   116.7  700.99   125.2  701.47
   126.5  701.54  127.55  701.98   136.2  706.41   145.9  710.52   155.6  711.61
   165.4  713.64   175.1  718.43   184.8  722.72
#Mann= 3 , 0 , 0
       0      .1       0   110.2    .045       0  127.55     .06       0
Bank Sta=110.2,127.55
XS Rating Curve= 0 ,0
Exp/Cntr=0.3,0.1

Type RM Length L Ch R = 1 ,29833.1 ,26.1,25.4,24.7
XS GIS Cut Line= 3
     1759935.362      476477.138     1759957.063      476482.347
     1760104.633      476550.055
#Sta/Elev= 23
       0  718.52     7.4  714.53    14.9  710.79    22.3  708.89    31.9  707.93
    41.4  707.65      51  707.34    60.5  706.97    70.1  706.53    79.6  706.01
    89.2  705.33    98.7  703.06   101.2  702.41   108.3  700.55   116.2  701.83
   117.8  702.09   127.4  706.98   136.9  710.21   146.5  710.81     156  713.23
   165.6  718.42   175.1  723.89   184.7  728.43
#Mann= 3 , 0 , 0
       0      .1       0   101.2    .045       0   117.8     .06       0
Bank Sta=101.2,117.8
XS Rating Curve= 0 ,0
Exp/Cntr=0.3,0.1

Type RM Length L Ch R = 1 ,29807.7 ,38.3,38.3,38.3
XS GIS Cut Line= 2
     1759931.022      476501.444      1760096.82      476571.756
#Sta/Elev= 22
       0  719.04     9.5  714.63      19   710.7    28.4  708.32    37.9  707.42
    47.4  707.16    56.9  706.91    66.4  706.59    75.8  706.25    85.3  705.88
    94.8  703.32    98.2  702.23   104.3  700.27   113.2  702.53   113.7  702.66
   123.2  707.29   132.7  709.59   142.2  710.35   151.7  712.66   161.1   717.6
   170.6  723.43   180.1  729.21
#Mann= 3 , 0 , 0
       0      .1       0    98.2    .045       0   113.7     .06       0
Bank Sta=98.2,113.7
XS Rating Curve= 0 ,0
Exp/Cntr=0.3,0.1

Type RM Length L Ch R = 1 ,29769.4 ,39,39.9,40.8
XS GIS Cut Line= 2
     1759915.397      476536.166     1760081.195      476606.479
#Sta/Elev= 23
       0  725.45     9.5  720.07      19  714.36    28.4  709.37    37.9  707.13
    47.4   706.9    56.9  706.83    66.4  706.62    75.8   706.3    85.3  705.63
    94.8  703.58  101.86  700.98   103.4  700.41   104.3  700.08   113.7  699.46
   118.4  701.86   123.2  704.31   132.7  708.16   142.2  708.99   151.7  710.38
   161.1   714.6   170.6  720.66   180.1  726.47
#Mann= 3 , 0 , 0
       0      .1       0  101.86    .045       0   118.4     .06       0
Bank Sta=101.86,118.4
XS Rating Curve= 0 ,0
Exp/Cntr=0.3,0.1

Type RM Length L Ch R = 1 ,29729.5 ,45.9,47.9,49.8
XS GIS Cut Line= 4
     1759915.397      476576.097     1759949.251      476590.854
     1760028.244       476628.18     1760078.591      476645.541
#Sta/Elev= 23
       0  720.29     9.2  714.42    18.5  709.29    27.7  706.67    36.9   706.4
    46.6  706.05    56.4  705.62      66  705.11    75.8  704.07    85.5  701.57
   90.88  700.22    92.2  699.95    95.2  699.22   104.9  700.82   107.2  701.94
   114.6  705.56   124.3  708.02   133.2  708.28     142  709.62   150.9  713.44
   159.8  718.92   168.7  724.48   177.6  729.17
#Mann= 3 , 0 , 0
       0      .1       0   90.88    .045       0   107.2     .06       0
Bank Sta=90.88,107.2
XS Rating Curve= 0 ,0
Exp/Cntr=0.3,0.1

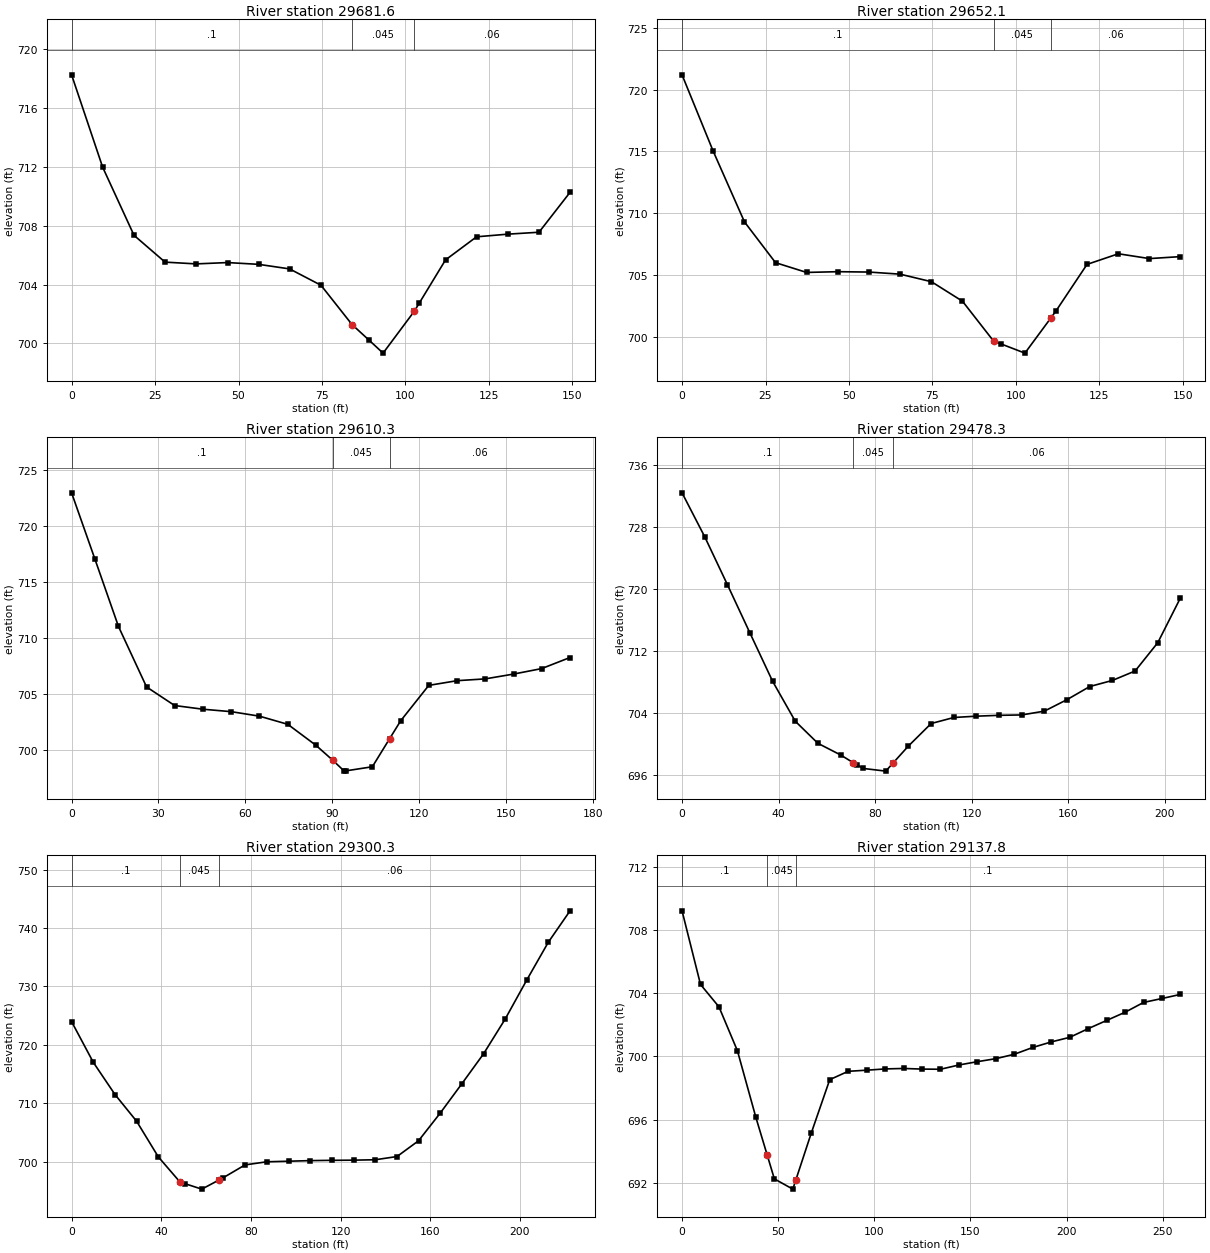
Type RM Length L Ch R = 1 ,29681.6 ,29.5,29.5,29.5
XS GIS Cut Line= 2
     1759908.452      476615.159     1760037.793      476689.812
#Sta/Elev= 19
       0  718.24     9.3  711.97    18.7  707.34      28  705.52    37.3   705.4
    46.7  705.49      56  705.37    65.3  705.06    74.7  703.95      84  701.28
    89.2   700.2    93.3  699.34   102.7   702.2   104.2  702.76     112  705.67
   121.3  707.24   130.7  707.42     140  707.55   149.3  710.26
#Mann= 3 , 0 , 0
       0      .1       0      84    .045       0   102.7     .06       0
Bank Sta=84,102.7
XS Rating Curve= 0 ,0
Exp/Cntr=0.3,0.1

Type RM Length L Ch R = 1 ,29652.1 ,45.5,41.8,38.1
XS GIS Cut Line= 2
     1759894.563      476640.333     1760023.904      476714.986
#Sta/Elev= 19
       0   721.2     9.3  715.04    18.7   709.3      28     706    37.3  705.21
    46.7  705.27      56  705.24    65.3  705.07    74.7  704.46      84  702.88
    93.3  699.66    95.4  699.44   102.7  698.68   110.4   701.5     112  702.09
   121.3  705.86   130.7  706.72     140  706.33   149.3  706.49
#Mann= 3 , 0 , 0
       0      .1       0    93.3    .045       0   110.4     .06       0
Bank Sta=93.3,110.4
XS Rating Curve= 0 ,0
Exp/Cntr=0.3,0.1

Type RM Length L Ch R = 1 ,29610.3 ,131.7,132,131.6
XS GIS Cut Line= 3
      1759878.07      476691.548     1759891.091      476701.097
     1760036.925      476756.652
#Sta/Elev= 22
       0  722.98     8.1  717.03    16.2  711.04    25.9  705.64    35.6  703.98
    45.4  703.65    55.2  703.43    64.9  703.03    74.7   702.3    84.4  700.43
   90.24  699.09    94.2  698.12    94.9  698.15   103.9  698.51   109.9  701.03
   113.7  702.62   123.4  705.78   133.2   706.2   142.9  706.36   152.7  706.79
   162.4  707.28   172.2  708.27
#Mann= 3 , 0 , 0
       0      .1       0   90.24    .045       0   109.9     .06       0
Bank Sta=90.24,109.9
XS Rating Curve= 0 ,0
Exp/Cntr=0.3,0.1

Type RM Length L Ch R = 1 ,29478.3 ,179.4,178.1,177.3
XS GIS Cut Line= 3
     1759824.251      476807.868     1759964.008      476862.555
     1760018.695      476876.444
#Sta/Elev= 26
       0  732.46     9.4  726.78    18.8  720.59    28.1  714.37    37.5  708.12
    46.9  702.95    56.3  700.09    65.7  698.59   70.86   697.6    72.6   697.3
      75  696.85    84.4   696.5    87.6  697.61    93.8  699.75   103.2  702.65
   112.6  703.43   121.9   703.6   131.3  703.71   140.7  703.76   150.1  704.25
   159.5  705.74   168.9  707.43   178.3  708.22   187.7  709.44   197.1   713.1
   206.5   718.9
#Mann= 3 , 0 , 0
       0      .1       0   70.86    .045       0    87.6     .06       0
Bank Sta=70.86,87.6
XS Rating Curve= 0 ,0
Exp/Cntr=0.3,0.1

Type RM Length L Ch R = 1 ,29300.3 ,160.6,162.5,164.8
XS GIS Cut Line= 3
     1759773.904      476982.347     1759921.473      477029.222
     1759988.313       477038.77
#Sta/Elev= 26
       0  723.98     9.7     717    19.4  711.48      29  706.93    38.7  700.82
    48.4   696.5    50.6  696.23    58.1   695.3    65.6  696.83    67.7  697.26
    77.4  699.45    87.1  699.98    96.8  700.08   106.4  700.18   116.1  700.23
   125.8  700.26   135.5  700.33   145.2  700.88   154.8  703.58   164.5  708.33
   174.1  713.33   183.8  718.46   193.4  724.38   203.1  731.11   212.7  737.57
   222.4  742.95
#Mann= 3 , 0 , 0
       0      .1       0    48.4    .045       0    65.6     .06       0
Bank Sta=48.4,65.6
XS Rating Curve= 0 ,0
Exp/Cntr=0.3,0.1

Type RM Length L Ch R = 1 ,29137.8 ,128.2,131.1,133
XS GIS Cut Line= 2
     1759736.484      477135.831     1759975.199      477236.743
#Sta/Elev= 30
       0  709.22     9.6  704.56    19.2  703.14    28.8  700.36    38.4  696.14
    44.2  693.79      48  692.25    57.6   691.6    59.2  692.19    67.2  695.15
    76.8  698.53    86.4  699.06      96  699.13   105.6  699.21   115.2  699.24
   124.8   699.2   134.4  699.19     144  699.46   153.6  699.67   163.2  699.86
   172.8  700.14   182.4  700.57     192  700.92   201.6  701.21   211.2  701.76
   220.8  702.28   230.4   702.8     240  703.42   249.6  703.67   259.2  703.93
#Mann= 3 , 0 , 0
       0      .1       0    44.2    .045       0    59.2      .1       0
Bank Sta=44.2,59.2
XS Rating Curve= 0 ,0
Exp/Cntr=0.3,0.1

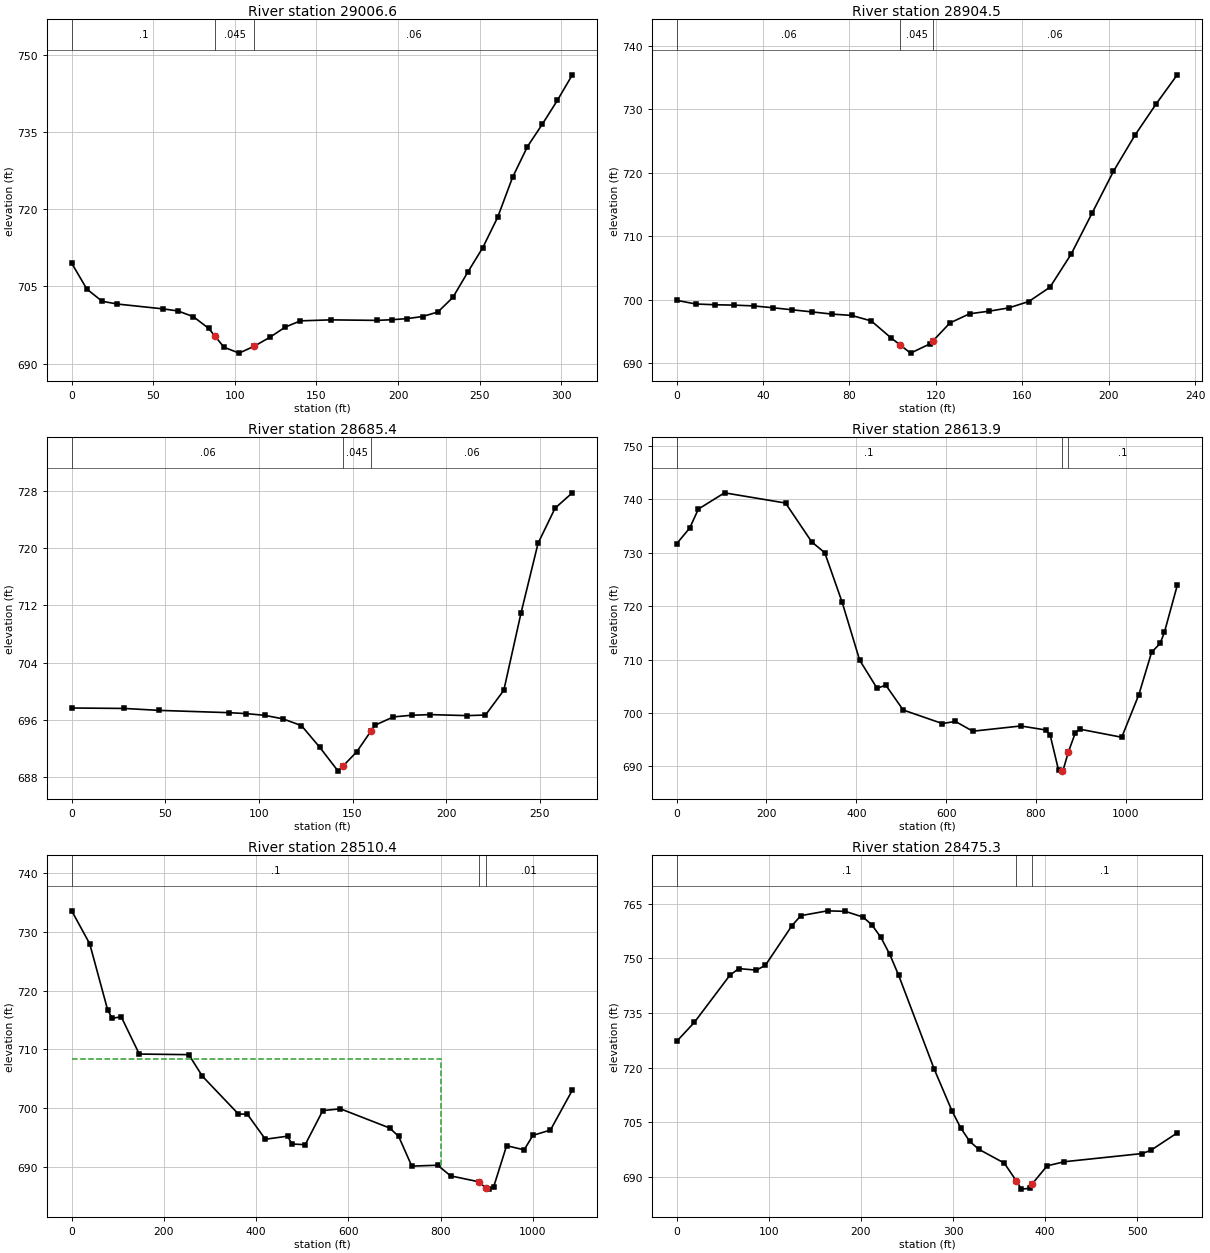
Type RM Length L Ch R = 1 ,29006.6 ,102.7,102.2,101.8
XS GIS Cut Line= 4
     1759692.307      477242.763     1759758.279      477277.486
     1759892.827      477343.458     1759937.098      477412.902
#Sta/Elev= 30
       0   709.5     9.3  704.48    18.6  702.11      28  701.57    55.9  700.63
    65.2  700.22    74.6   699.1    83.9  696.84   87.73  695.36    93.3  693.17
   102.6  692.02     112  693.39   121.4  695.09   130.8  697.07   140.1   698.3
   158.8  698.49   186.9  698.39   196.3  698.52   205.7  698.74     215  699.14
   224.4  700.02   233.6  702.86   242.7  707.76   251.9  712.53     261  718.42
   270.2  726.24   279.3   732.2   288.5   736.6   297.6  741.18   306.8  746.16
#Mann= 3 , 0 , 0
       0      .1       0   87.73    .045       0     112     .06       0
Bank Sta=87.73,112
XS Rating Curve= 0 ,0
Exp/Cntr=0.3,0.1

Type RM Length L Ch R = 1 ,28904.5 ,213.4,219,224.9
XS GIS Cut Line= 4
     1759685.362      477319.152     1759709.668      477356.479
     1759814.702      477411.166     1759863.313      477459.777
#Sta/Elev= 28
       0   699.9     8.9  699.32    17.8   699.2    26.7  699.14    35.6  699.02
    44.5  698.73    53.6   698.4    62.8  698.07    71.9  697.73      81  697.52
    90.1  696.65    99.2     694   103.6  692.83   108.3  691.58   117.4  693.06
   118.6  693.49   126.5  696.33   135.6  697.78   144.7  698.19   153.8  698.71
     163  699.71   172.8  701.96   182.6  707.17   192.4   713.7   202.2  720.23
   212.1  725.89   221.9  730.81   231.7  735.42
#Mann= 3 , 0 , 0
       0     .06       0   103.6    .045       0   118.6     .06       0
Bank Sta=103.6,118.6
XS Rating Curve= 0 ,0
Exp/Cntr=0.3,0.1

Type RM Length L Ch R = 1 ,28685.4 ,62,71.5,80.8
XS GIS Cut Line= 4
     1759553.418      477491.895     1759630.675      477543.979
     1759732.237      477636.861     1759766.091      477650.749
#Sta/Elev= 24
       0  697.68      28  697.62    46.6  697.35    83.9  697.03    93.2   696.9
     103  696.66   112.8  696.17   122.7  695.23   132.5   692.2   142.3  688.88
     145  689.61   152.2  691.56     160  694.52     162  695.28   171.8  696.44
   181.6  696.67   191.5  696.76   211.1  696.62     221   696.7   230.8  700.15
     240  710.93   249.1  720.65   258.2  725.55   267.4  727.68
#Mann= 3 , 0 , 0
       0     .06       0     145    .045       0     160     .06       0
Bank Sta=145,160
XS Rating Curve= 0 ,0
Exp/Cntr=0.3,0.1

Type RM Length L Ch R = 1 ,28613.9 ,84.6,103.5,107.2
XS GIS Cut Line= 6
     1758901.754      477196.858     1759281.582      477431.073
     1759557.975      477546.279     1759610.058      477600.098
     1759665.614      477718.154     1759827.072      477716.418
#Sta/Elev= 30
       0  731.66    29.1  734.59    48.5  738.16   106.7   741.2   242.5  739.29
   300.7  732.02   329.8  729.99   368.6  720.69   407.4  709.89   446.2  704.62
   465.6  705.21   504.3  700.56   591.5  698.02   620.5  698.42   659.2  696.59
   766.1  697.57   822.3  696.81   831.6  695.79   850.2  689.26   857.1  689.16
   859.6  689.12   872.1  692.74   887.5   696.3   896.8  696.98   990.7  695.46
  1028.7   703.4  1057.2  711.37  1076.2  713.02  1085.7  715.11  1114.2  723.86
#Mann= 3 , 0 , 0
       0      .1       0   857.1    .045       0   872.1      .1       0
Bank Sta=857.1,872.1
XS Rating Curve= 0 ,0
Exp/Cntr=0.3,0.1

Type RM Length L Ch R = 1 ,28510.4 ,78.7,35.1,6.9
XS GIS Cut Line= 6
     1758805.183      477395.425     1759227.838      477472.971
     1759418.001      477537.381     1759544.737      477638.076
     1759600.293      477756.131     1759761.751      477754.395
#Sta/Elev= 30
       0  733.59    39.1  727.97    78.1  716.67    87.9  715.28   107.4  715.54
   146.5  709.19   253.9  709.09   283.2  705.43   361.4  698.98   380.9  698.94
   419.9  694.68     468   695.2   477.5  693.87   506.2  693.75   544.4  699.56
   582.7  699.86   689.2   696.6   708.8  695.18   737.4   690.1   793.5  690.25
   821.5  688.44   883.3  687.42   898.3  686.32   905.4  686.18   914.7  686.52
     943  693.58     981  692.87    1000  695.34    1038  696.24  1085.5  703.04
#Mann= 3 , 0 , 0
       0      .1       0   883.3    .045       0   898.3     .01       0
#XS Ineff= 2 , 0
          801.42  708.32
Permanent Ineff=
       F       F
Bank Sta=883.3,898.3
XS Rating Curve= 0 ,0
Exp/Cntr=0.3,0.1

Type RM Length L Ch R = 1 ,28475.3 ,21.3,17.3,13.4
XS GIS Cut Line= 4
     1759242.871       477619.63      1759540.18      477757.433
     1759642.176      477765.029     1759755.241      477757.347
#Sta/Elev= 30
       0  727.18    19.3  732.43    57.8  745.36    67.5   747.2    86.7  746.77
    96.4  748.11   125.3  759.03   134.9  761.74   163.8  763.06   183.1  762.91
   202.4  761.34     212  759.18   221.7  755.77   231.3  751.13     241  745.35
   279.5  719.64   298.8  708.15   308.4  703.42     318  699.79   327.7  697.61
   355.6  693.78   368.7   688.9   374.2  686.63   383.5  686.85  385.83  688.04
   402.1  693.02   420.7  694.15   505.5  696.41     515  697.34   543.3  702.07
#Mann= 3 , 0 , 0
       0      .1       0   368.7    .045       0  385.83      .1       0
Bank Sta=368.7,385.83
XS Rating Curve= 0 ,0
Exp/Cntr=0.3,0.1

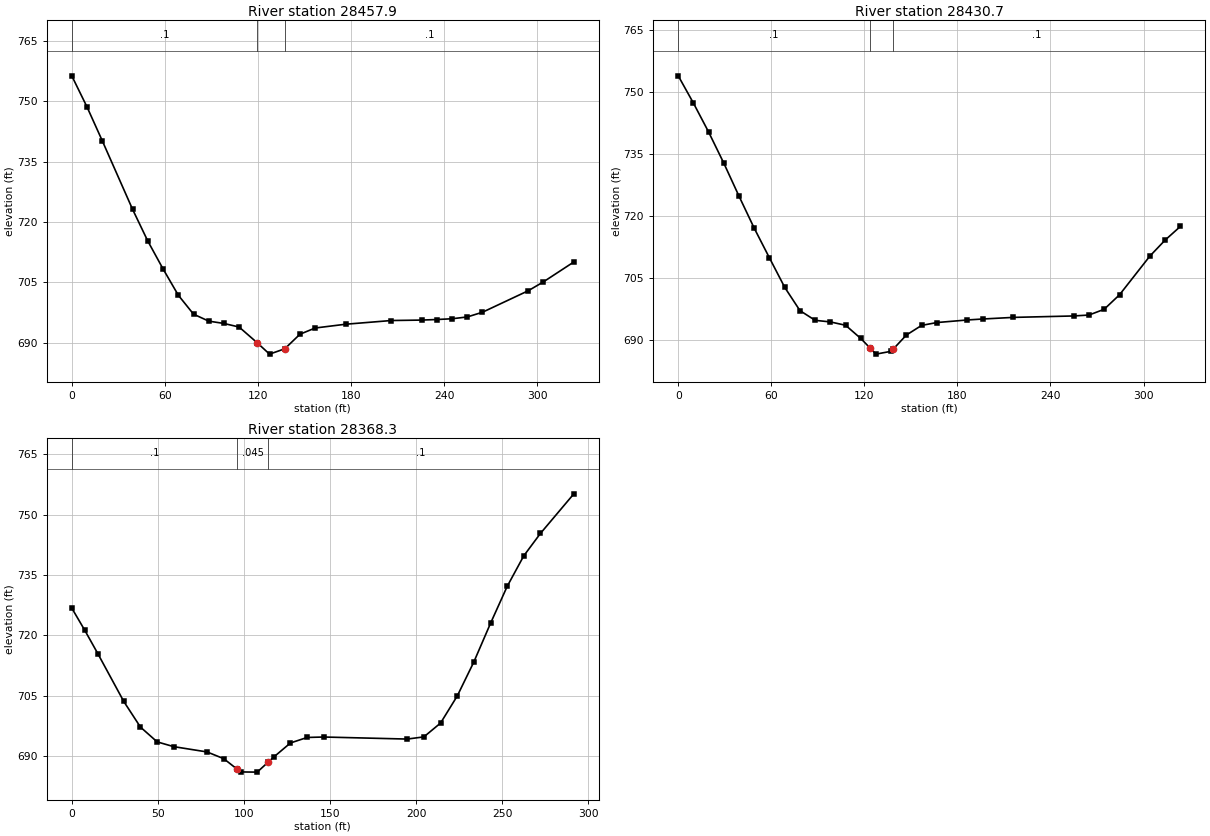
Type RM Length L Ch R = 1 ,28457.9 ,27.2,27.2,27.2
XS GIS Cut Line= 2
      1759465.31      477789.986     1759787.576      477759.604
#Sta/Elev= 26
       0  756.34     9.8  748.63    19.6  740.26    39.2  723.17      49   715.3
    58.8   708.4    68.7  701.82    78.5  697.12    88.3  695.39    98.1  694.81
   107.9  693.92   119.5  690.03   127.5  687.19   137.3  688.51   147.1  692.13
   156.9  693.68   176.6  694.62     206  695.54   225.6  695.65   235.4  695.79
   245.2  695.98     255  696.43   264.8   697.6   294.3  702.94   304.1  705.15
   323.7  710.09
#Mann= 3 , 0 , 0
       0      .1       0   119.5    .045       0   137.3      .1       0
Bank Sta=119.5,137.3
XS Rating Curve= 0 ,0
Exp/Cntr=0.3,0.1

Type RM Length L Ch R = 1 ,28430.7 ,51.2,62.4,73.7
XS GIS Cut Line= 2
     1759466.395      477817.112     1759788.661       477786.73
#Sta/Elev= 30
       0  753.87     9.8  747.28    19.6  740.29    29.4  732.76    39.2  724.79
      49  717.06    58.8   709.9    68.7  702.75    78.5  697.15    88.3  694.81
    98.1  694.43   107.9  693.62   117.7  690.43   123.4  688.23   127.5  686.65
   137.3  687.34   138.4  687.78   147.1  691.26   156.9  693.59   166.8  694.28
   186.4   694.9   196.2  695.13   215.8  695.52     255  695.87   264.8  696.09
   274.6  697.48   284.5  700.98   304.1  710.34   313.9  714.19   323.7  717.48
#Mann= 3 , 0 , 0
       0      .1       0   123.4    .045       0   138.4      .1       0
Bank Sta=123.4,138.4
XS Rating Curve= 0 ,0
Exp/Cntr=0.3,0.1

Type RM Length L Ch R = 1 ,28368.3 ,201.3,202.2,202.1
XS GIS Cut Line= 4
      1759502.81      477841.895     1759532.758      477837.989
     1759703.331      477906.999     1759758.018      477961.687
#Sta/Elev= 27
       0  726.79     7.6  721.24    15.1   715.5    30.2   703.6    39.9  697.23
    49.6  693.56    59.2  692.38    78.6  691.06    88.3  689.38   96.19  686.73
      98   686.1   107.7  686.05     114  688.51   117.4  689.83     127  693.29
   136.7  694.66   146.4  694.77   194.8  694.26   204.5   694.8   214.2  698.24
   223.9  704.97   233.5  713.39   243.2     723   252.9  732.19   262.5  739.75
   272.2  745.33   291.6  755.16
#Mann= 3 , 0 , 0
       0      .1       0   96.19    .045       0     114      .1       0
Bank Sta=96.19,114
XS Rating Curve= 0 ,0
Exp/Cntr=0.3,0.1