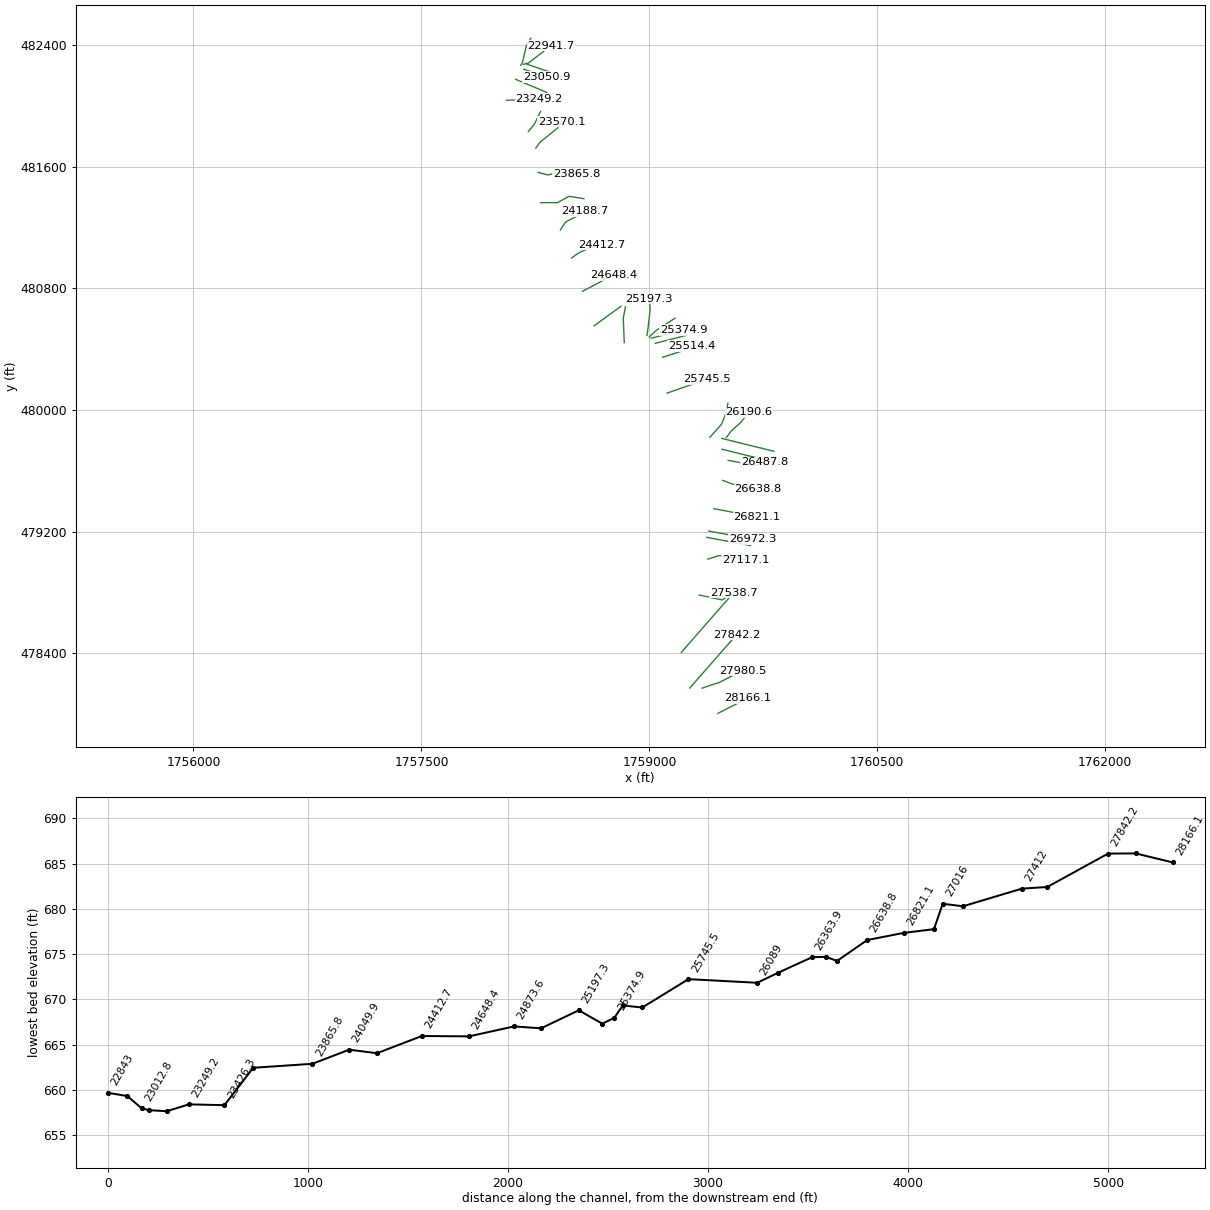
HEC-RAS study TRACEFORK.prj: TRACEFORK

--- TRACEFORK.g01 (geometry) --- (continued)

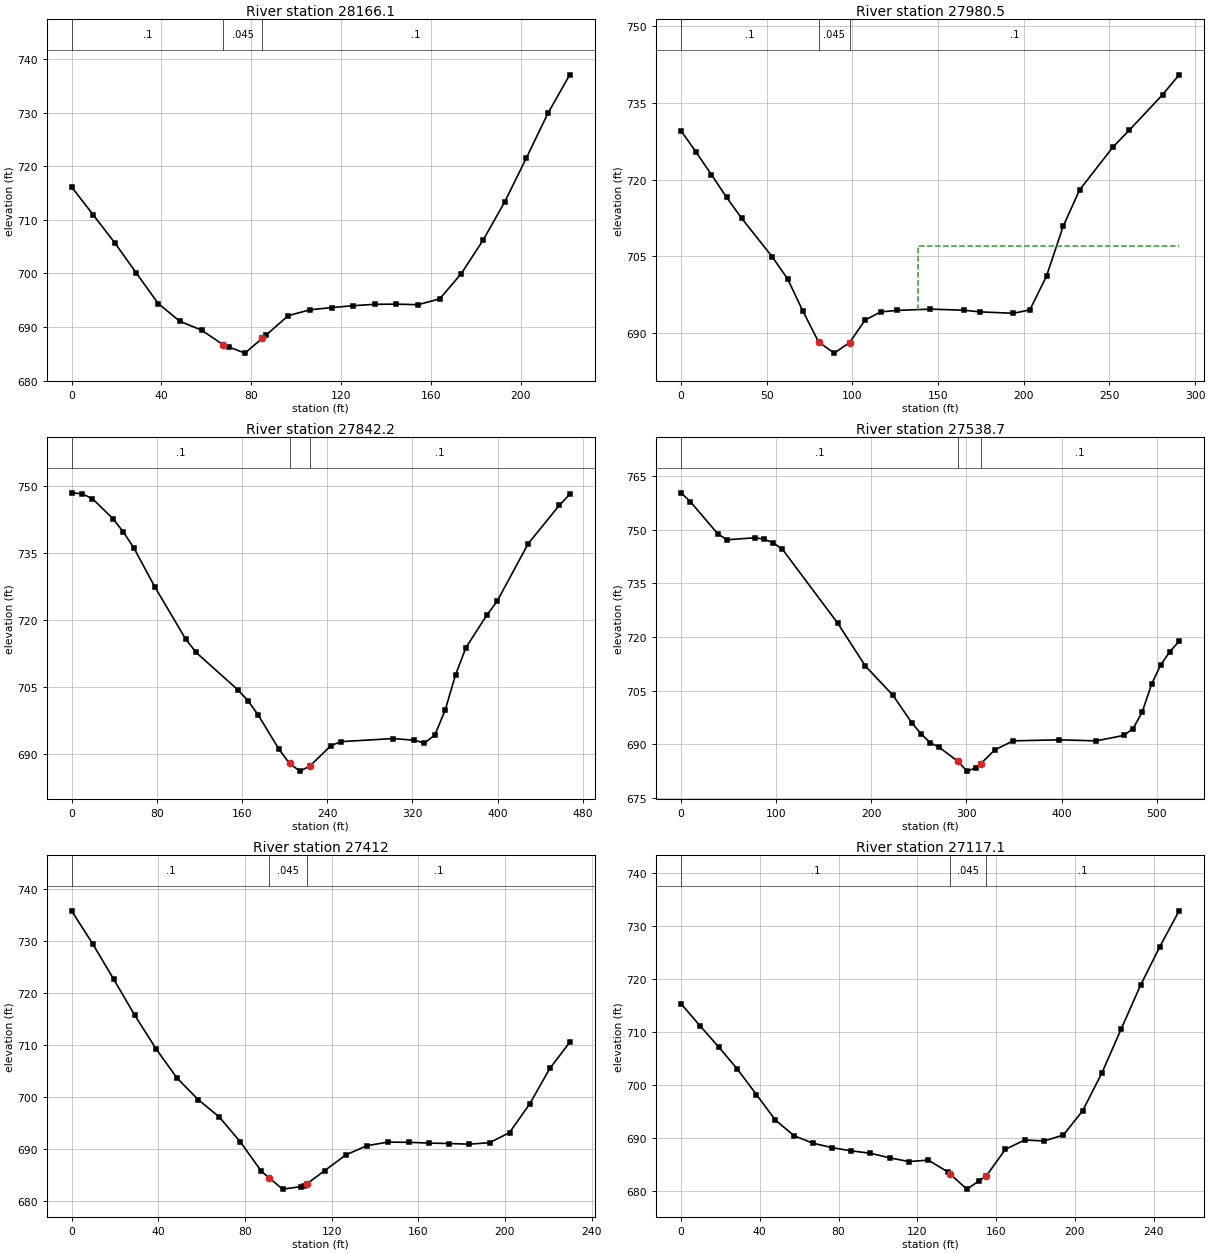
Type RM Length L Ch R = 1 ,28166.1 ,188.5,185.6,182.6
XS GIS Cut Line= 2
     1759450.727      478004.656     1759648.643      478104.916
#Sta/Elev= 26
       0  716.14     9.6  710.96    19.3  705.68    28.9  700.04    38.6  694.39
    48.2  691.08    57.9  689.42    67.5  686.69    69.9   686.3    77.2  685.13
    84.9  687.88    86.8  688.56    96.5  692.12   106.1  693.21   115.8  693.63
   125.4  693.98     135  694.24   144.7  694.27   154.3  694.17     164  695.26
   173.6  699.98   183.3  706.21   192.9  713.33   202.6  721.57   212.2  729.91
   221.9  737.07
#Mann= 3 , 0 , 0
       0      .1       0    67.5    .045       0    84.9      .1       0
Bank Sta=67.5,84.9
XS Rating Curve= 0 ,0
Exp/Cntr=0.3,0.1

Type RM Length L Ch R = 1 ,27980.5 ,119.6,138.3,156.8
XS GIS Cut Line= 4
      1759346.56       478170.02     1759405.154      478190.854
     1759457.237      478206.479     1759612.185      478285.906
#Sta/Elev= 26
       0  729.56     8.9  725.33    17.8  720.97    26.6  716.54    35.5  712.42
    53.3  704.91    62.2  700.64    71.2   694.3    80.3  688.31    89.4  686.13
    98.4   688.2   107.5  692.61   116.6  694.18   126.2  694.47   145.6  694.72
   164.9  694.51   174.6  694.18     194  693.91   203.6  694.57   213.3  701.17
     223  710.86   232.6  717.99     252  726.33   261.7  729.69     281  736.57
   290.7  740.46
#Mann= 3 , 0 , 0
       0      .1       0    80.3    .045       0    98.4      .1       0
#XS Ineff= 2 , 0
                          138.44          707.05
Permanent Ineff=
       F       F
Bank Sta=80.3,98.4
XS Rating Curve= 0 ,0
Exp/Cntr=0.3,0.1

Type RM Length L Ch R = 1 ,27842.2 ,302.3,303.5,304.6
XS GIS Cut Line= 2
     1759265.831      478171.322     1759574.425      478522.885
#Sta/Elev= 30
       0  748.37     9.8  748.16    19.5  747.08      39  742.55    48.7  739.58
    58.5  736.04      78   727.4   107.2  715.63     117  712.65   155.9  704.35
   165.7  701.86   175.4   698.6   194.9  690.95   204.7  687.82   214.4  686.11
   223.7  687.23   243.6  691.84   253.4  692.71   302.1   693.4   321.6  693.02
   331.4  692.41   341.1  694.18   350.8  699.75   360.6  707.68   370.3  713.72
   389.8  720.98   399.6  724.12   428.8     737     458  745.58   467.8  748.06
#Mann= 3 , 0 , 0
       0      .1       0   204.7    .045       0   223.7      .1       0
Bank Sta=204.7,223.7
XS Rating Curve= 0 ,0
Exp/Cntr=0.3,0.1

Type RM Length L Ch R = 1 ,27538.7 ,157.8,126.7,95.6
XS GIS Cut Line= 2
     1759209.841      478405.697     1759554.966      478799.505
#Sta/Elev= 30
       0  760.39     9.7  757.96    38.8  748.87    48.5  747.24    77.6   747.8
    87.3  747.42      97  746.37   106.7  744.55   164.8  723.84   193.9  711.84
     223  703.61   242.4  696.02   252.1  692.94   261.8  690.43   271.5  689.07
   290.9  685.21   300.6  682.42   310.3  683.36   314.9  684.45   329.7  688.34
   349.1   690.9   397.6  691.19   436.4   690.9   465.4  692.42   475.2  694.35
   484.8  698.99   494.6  706.76   504.2  712.18   513.9  715.91   523.6  718.82
#Mann= 3 , 0 , 0
       0      .1       0   290.9    .045       0   314.9      .1       0
Bank Sta=290.9,314.9
XS Rating Curve= 0 ,0
Exp/Cntr=0.3,0.1

Type RM Length L Ch R = 1 ,27412   ,293.1,294.9,296
XS GIS Cut Line= 3
     1759328.331      478783.302     1759480.675      478750.749
      1759540.86       478794.08
#Sta/Elev= 28
       0  735.81     9.7  729.49    19.5   722.6    29.2  715.68      39  709.23
    48.7   703.6    58.4  699.48    68.2  696.11    77.9  691.32    87.6  685.67
    91.1  684.44    97.4  682.24   106.1  682.73   107.1  682.79  108.72  683.29
   116.8   685.8   126.6  688.83   136.3   690.6     146  691.29   155.8  691.25
     165   691.1   174.3  691.02   183.6  690.89   192.9  691.18   202.1  693.12
   211.4  698.63   220.7  705.46   229.9   710.5
#Mann= 3 , 0 , 0
       0      .1       0    91.1    .045       0  108.72      .1       0
Bank Sta=91.1,108.72
XS Rating Curve= 0 ,0
Exp/Cntr=0.3,0.1

Type RM Length L Ch R = 1 ,27117.1 ,101.8,101.1,100.2
XS GIS Cut Line= 3
      1759384.32      479018.979     1759457.237      479042.416
     1759631.716      479016.374
#Sta/Elev= 29
       0  715.33     9.6  711.18    19.2  707.14    28.7  702.94    38.3  698.17
    47.9  693.36    57.4  690.39      67  688.97    76.6  688.14    86.4  687.52
    96.2  687.07     106   686.2   115.8   685.5   125.6  685.77   135.4  683.57
   136.6  683.17   145.2  680.29   151.6   681.9     155  682.75   164.8  687.83
   174.6  689.57   184.4  689.39   194.2  690.51     204   695.1   213.8  702.27
   223.6  710.58   233.4  718.82   243.2  726.12     253  732.88
#Mann= 3 , 0 , 0
       0      .1       0   136.6    .045       0     155      .1       0
Bank Sta=136.6,155
XS Rating Curve= 0 ,0
Exp/Cntr=0.3,0.1

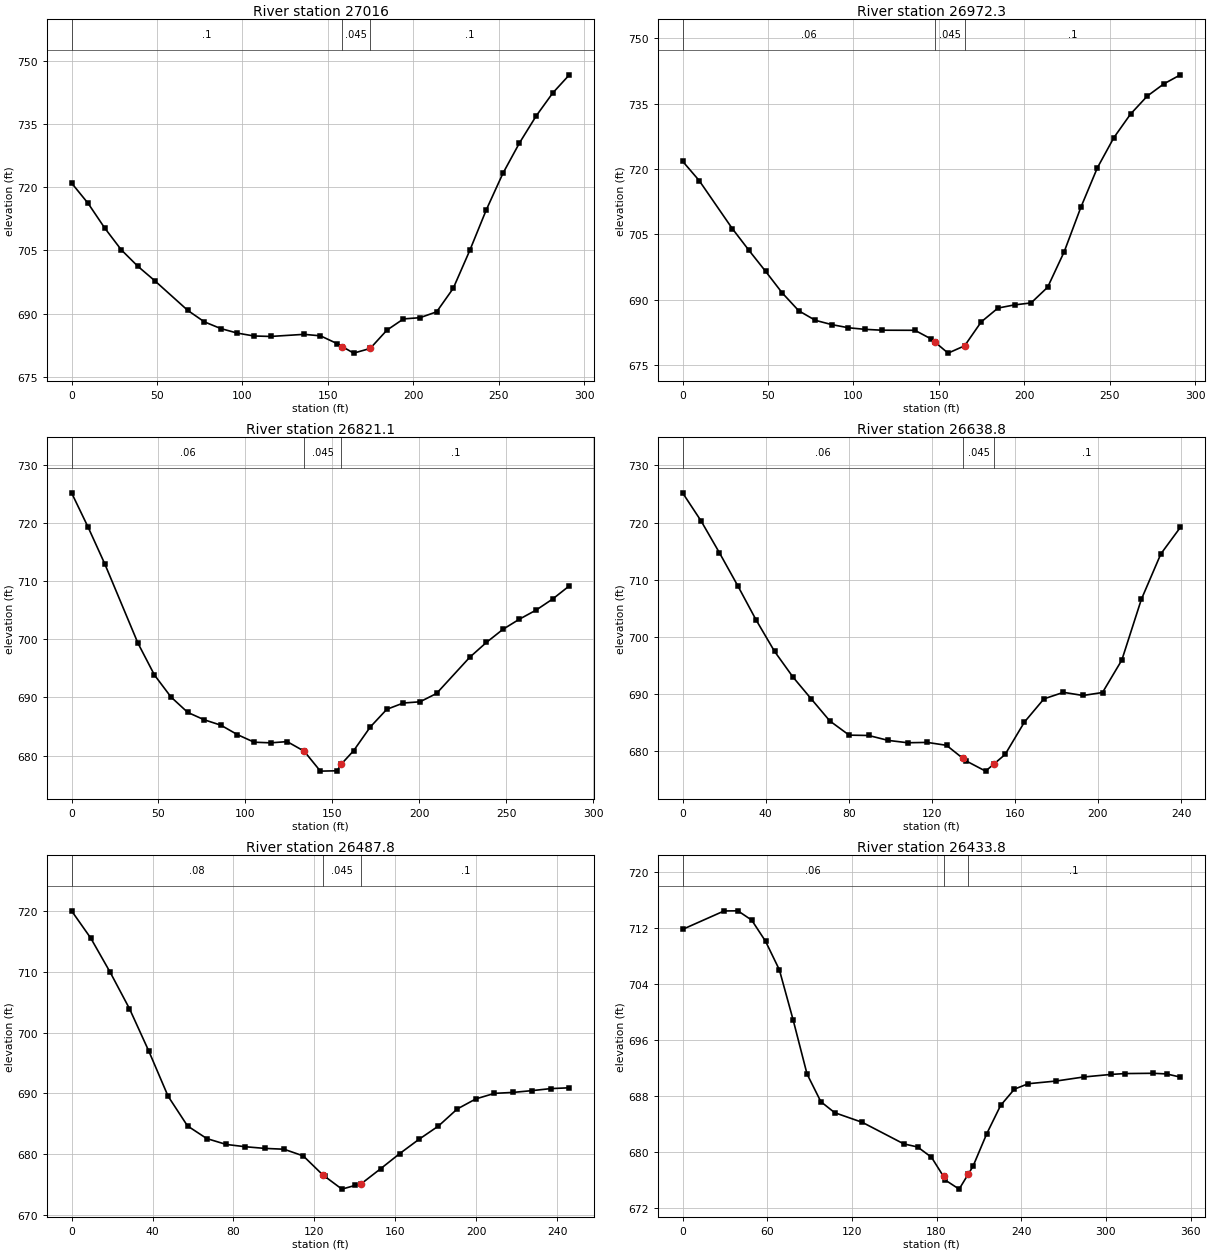
Type RM Length L Ch R = 1 ,27016   ,43.7,43.7,43.7
XS GIS Cut Line= 2
     1759379.112      479162.208      1759665.57      479108.822
#Sta/Elev= 30
       0  721.06     9.7  716.21    19.4  710.35    29.1  705.16    38.8  701.24
    48.6  697.84      68  690.75    77.7  688.02    87.4  686.41    97.1  685.33
   106.8  684.65   116.6  684.54     136  685.04   145.7  684.69   155.4  682.84
   158.4  682.14   165.1  680.57   174.8  681.68   184.6  686.04   194.3  688.71
     204  689.01   213.7   690.4   223.4  695.98   233.1  705.01   242.8   714.7
   252.5  723.36   262.2   730.6     272  737.04   281.7   742.5   291.4  746.81
#Mann= 3 , 0 , 0
       0      .1       0   158.4    .045       0   174.8      .1       0
Bank Sta=158.4,174.8
XS Rating Curve= 0 ,0
Exp/Cntr=0.3,0.1

Type RM Length L Ch R = 1 ,26972.3 ,151.3,151.2,151.2
XS GIS Cut Line= 2
     1759392.133      479203.874     1759678.591      479150.489
#Sta/Elev= 30
       0   721.8     9.7  717.37    29.1  706.34    38.8  701.38    48.6  696.53
    58.3  691.59      68  687.48    77.7  685.29    87.4   684.3    97.1  683.58
   106.8  683.22   116.6  683.02     136     683   145.7  680.97   147.5  680.37
   155.4  677.76   165.1  679.44   174.8  684.92   184.6   688.1   194.3  688.83
     204  689.28   213.7  692.89   223.4  701.04   233.1  711.19   242.8  720.29
   252.5  727.24   262.2  732.61     272  736.75   281.7  739.55   291.4  741.63
#Mann= 3 , 0 , 0
       0     .06       0   147.5    .045       0   165.1      .1       0
Bank Sta=147.5,165.1
XS Rating Curve= 0 ,0
Exp/Cntr=0.3,0.1

Type RM Length L Ch R = 1 ,26821.1 ,182.6,182.3,181.8
XS GIS Cut Line= 2
     1759424.685       479351.01     1759705.935      479297.624
#Sta/Elev= 30
       0  725.16     9.5  719.27    19.1  712.96    38.2  699.32    47.7  693.85
    57.2  690.08    66.8  687.44    76.3  686.17    85.9  685.24    95.4  683.62
     105  682.32   114.5  682.21     124  682.42   133.8  680.77   143.1  677.35
   152.7  677.41  155.18  678.57   162.2  680.85   171.8  684.93   181.3  687.97
   190.8  689.05   200.4  689.26   209.9  690.69     229  696.91   238.6  699.46
   248.1  701.71   257.6  703.46   267.2  705.02   276.7  706.92   286.3  709.18
#Mann= 3 , 0 , 0
       0     .06       0   133.8    .045       0  155.18      .1       0
Bank Sta=133.8,155.18
XS Rating Curve= 0 ,0
Exp/Cntr=0.3,0.1

Type RM Length L Ch R = 1 ,26638.8 ,150.6,151.1,151.5
XS GIS Cut Line= 3
     1759481.977      479537.208     1759548.383      479512.468
     1759713.747      479478.614
#Sta/Elev= 29
       0   725.2     8.9  720.29    17.7  714.75    26.6  708.94    35.4  702.98
    44.3  697.48    53.2  692.98      62  689.16    70.9  685.33    80.2  682.85
    89.6  682.79      99  681.93   108.4  681.52   117.8  681.58   127.1  681.07
     135  678.78   136.5  678.35   145.9  676.56     150  677.83   155.3  679.47
   164.6  685.13     174  689.19   183.4  690.33   192.8  689.78   202.2   690.3
   211.5  695.97   220.9  706.58   230.3  714.53   239.7  719.17
#Mann= 3 , 0 , 0
       0     .06       0     135    .045       0     150      .1       0
Bank Sta=135,150
XS Rating Curve= 0 ,0
Exp/Cntr=0.3,0.1

Type RM Length L Ch R = 1 ,26487.8 ,55.2,53.9,52.7
XS GIS Cut Line= 3
     1759518.435      479668.718      1759696.82      479636.166
     1759758.018      479656.999
#Sta/Elev= 29
       0  720.08     9.5  715.58    19.1  709.95    28.6  703.98    38.2  696.96
    47.7  689.55    57.3  684.66    66.8  682.58    76.4  681.61    85.9  681.23
    95.4  680.96     105  680.82   114.5  679.72   124.1  676.61   125.1  676.36
   133.6  674.25   140.1  674.86   143.2  675.15   152.7   677.6   162.2  680.11
   171.8  682.48   181.3  684.64   190.6  687.45   199.8  689.11     209  690.02
   218.3  690.18   227.5  690.47   236.7   690.8     246  690.94
#Mann= 3 , 0 , 0
       0     .08       0   124.1    .045       0   143.2      .1       0
Bank Sta=124.1,143.2
XS Rating Curve= 0 ,0
Exp/Cntr=0.3,0.1

Type RM Length L Ch R = 1 ,26433.8 ,69.8,69.9,69.7
XS GIS Cut Line= 2
     1759477.897      479741.982     1759820.345      479657.347
#Sta/Elev= 30
       0  711.81    29.4  714.44    39.2  714.46      49  713.13    58.8  710.11
    68.6  706.03    78.4  698.84    88.2  691.15      98  687.19   107.8  685.62
   127.4  684.24   156.8  681.16   166.6  680.72   176.4  679.25  184.94  676.51
   186.2  675.99     196   674.7   202.3  676.79   205.8  677.95   215.6  682.63
   225.4  686.66   235.2  688.99     245  689.76   264.6  690.14   284.2  690.72
   303.8  691.09   313.6  691.21   333.2  691.25     343  691.16   352.8   690.7
#Mann= 3 , 0 , 0
       0     .06       0  184.94    .045       0   202.3      .1       0
Bank Sta=184.94,202.3
XS Rating Curve= 0 ,0
Exp/Cntr=0.3,0.1

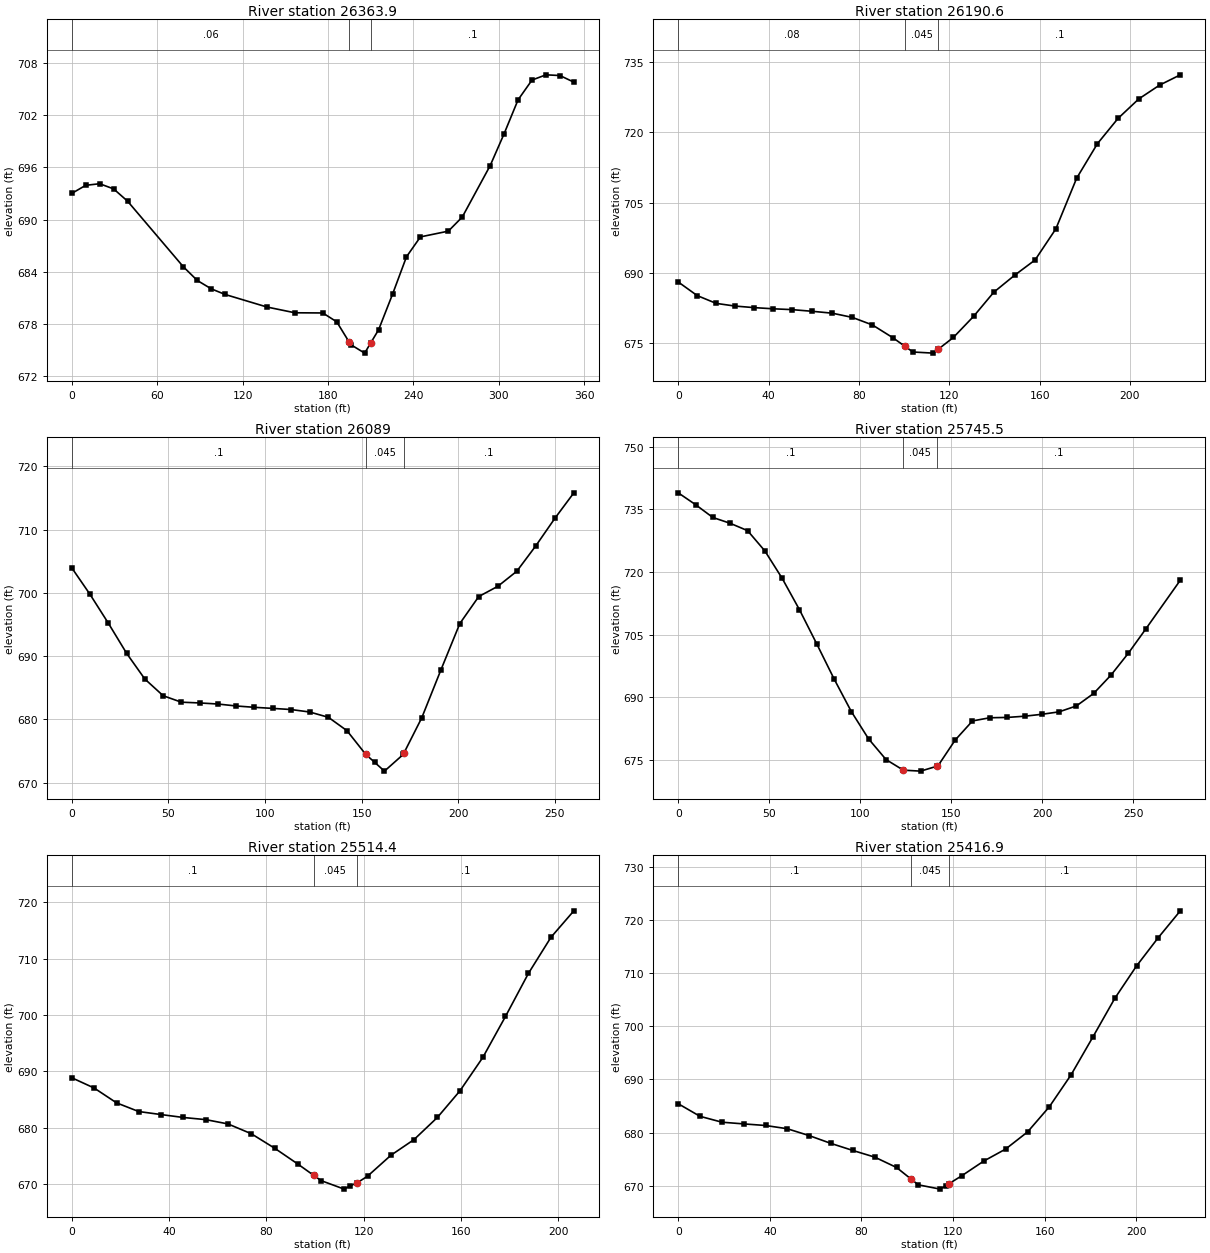
Type RM Length L Ch R = 1 ,26363.9 ,151.2,173.3,195.6
XS GIS Cut Line= 2
     1759476.768      479813.249     1759819.216      479728.614
#Sta/Elev= 30
       0     693     9.8  693.93    19.6  694.11    29.4  693.52    39.2  692.11
    78.4  684.58    88.2  683.01      98  682.05   107.8   681.4   137.2  679.96
   156.8   679.3   176.4  679.28   186.2  678.26   195.1  675.89     196  675.65
   205.8  674.67   210.1  675.85   215.6  677.35   225.4  681.43   235.2  685.73
     245  688.01   264.6  688.67   274.4  690.29     294  696.19   303.8  699.85
   313.6  703.74   323.4  706.01   333.2  706.61     343  706.53   352.8  705.77
#Mann= 3 , 0 , 0
       0     .06       0   195.1    .045       0   210.1      .1       0
Bank Sta=195.1,210.1
XS Rating Curve= 0 ,0
Exp/Cntr=0.3,0.1

Type RM Length L Ch R = 1 ,26190.6 ,91.4,101.6,112.5
XS GIS Cut Line= 4
     1759506.716       479819.76     1759536.664      479860.124
      1759603.07       479920.02     1759653.852      479985.124
#Sta/Elev= 28
       0  688.08     8.4  685.18    16.8  683.52    25.1  682.95    33.5  682.62
    41.9  682.37    50.3  682.19    59.2  681.84    68.2  681.43    77.1  680.53
      86  678.92      95  676.21   100.2  674.43   103.9  673.16   112.9  672.92
   115.2  673.78   121.8  676.25   130.8  680.77   139.7  685.89   148.9   689.5
     158  692.77   167.2   699.4   176.4  710.19   185.6  717.55   194.7  722.92
   203.9  727.08   213.1  730.02   222.3  732.22
#Mann= 3 , 0 , 0
       0     .08       0   100.2    .045       0   115.2      .1       0
Bank Sta=100.2,115.2
XS Rating Curve= 0 ,0
Exp/Cntr=0.3,0.1

Type RM Length L Ch R = 1 ,26089   ,362.6,343.5,323.3
XS GIS Cut Line= 4
     1759398.643      479821.062     1759474.164      479905.697
     1759500.206      479968.197     1759517.133       480045.02
#Sta/Elev= 30
       0  703.95     9.4  699.78    18.9  695.22    28.4  690.44    37.8  686.39
    47.3  683.75    56.7  682.73    66.2  682.61    75.6  682.44    85.1  682.13
    94.5  681.92     104  681.75   113.4  681.57   123.1  681.18   132.8  680.34
   142.4  678.23   152.1  674.49   156.8  673.21   161.8  671.84   171.5  674.47
   171.8  674.65   181.1  680.26     191  687.82   200.8  695.15   210.6  699.42
   220.5  701.04   230.3  703.42   240.1  707.42     250  711.78   259.8   715.8
#Mann= 3 , 0 , 0
       0      .1       0   152.1    .045       0   171.8      .1       0
Bank Sta=152.1,171.8
XS Rating Curve= 0 ,0
Exp/Cntr=0.3,0.1

Type RM Length L Ch R = 1 ,25745.5 ,231.6,231.1,230.3
XS GIS Cut Line= 2
     1759117.393      480111.427      1759377.81      480202.572
#Sta/Elev= 30
       0  738.99     9.5  736.16      19  733.08    28.5  731.69    38.1  729.92
    47.6  725.06    57.1  718.49    66.6  710.97    76.1  702.77    85.6  694.39
    95.1  686.54   104.6  679.97   114.2  675.01   123.7  672.47   133.2  672.24
     142   673.4   142.7  673.49   152.2   679.7   161.7  684.28   171.2  685.04
   180.8  685.12   190.3  685.41   199.8  685.87   209.3  686.46   218.8  687.88
   228.3  690.88   237.8  695.27   247.4  700.55   256.9  706.32   275.9  718.03
#Mann= 3 , 0 , 0
       0      .1       0   123.7    .045       0     142      .1       0
Bank Sta=123.7,142
XS Rating Curve= 0 ,0
Exp/Cntr=0.3,0.1

Type RM Length L Ch R = 1 ,25514.4 ,99.2,97.5,95.9
XS GIS Cut Line= 4
     1759087.445      480347.104     1759148.643      480366.635
     1759230.675      480392.677     1759278.852      480421.322
#Sta/Elev= 26
       0  688.87     9.2  687.05    18.4  684.42    27.5  682.88    36.7  682.34
    45.9  681.82    55.1  681.44    64.2  680.68    73.8  678.94    83.4  676.37
    92.9  673.57    99.5  671.54   102.5  670.62     112  669.11   114.5  669.71
  117.14  670.18   121.6  671.41   131.2  675.12   140.7   677.9   150.3  681.83
   159.6  686.56     169  692.49   178.3  699.75   187.7  707.37     197   713.8
   206.4  718.49
#Mann= 3 , 0 , 0
       0      .1       0    99.5    .045       0  117.14      .1       0
Bank Sta=99.5,117.14
XS Rating Curve= 0 ,0
Exp/Cntr=0.3,0.1

Type RM Length L Ch R = 1 ,25416.9 ,42.3,42,42.3
XS GIS Cut Line= 2
     1759037.966      480438.249     1759250.206      480492.937
#Sta/Elev= 27
       0  685.42     9.5  683.05    19.1  681.94    28.6  681.62    38.1  681.32
    47.6  680.71    57.2  679.41    66.7  677.94    76.2  676.62    85.8  675.36
    95.3  673.41   101.7  671.21   104.8  670.14   114.4  669.33   116.7  669.95
  118.25  670.36   123.9  671.88   133.4  674.62   142.9  676.87   152.5   680.1
     162  684.84   171.5  690.86   181.1  698.05   190.6  705.28   200.1  711.39
   209.6  716.73   219.2  721.77
#Mann= 3 , 0 , 0
       0      .1       0   101.7    .045       0  118.25      .1       0
Bank Sta=101.7,118.25
XS Rating Curve= 0 ,0
Exp/Cntr=0.3,0.1

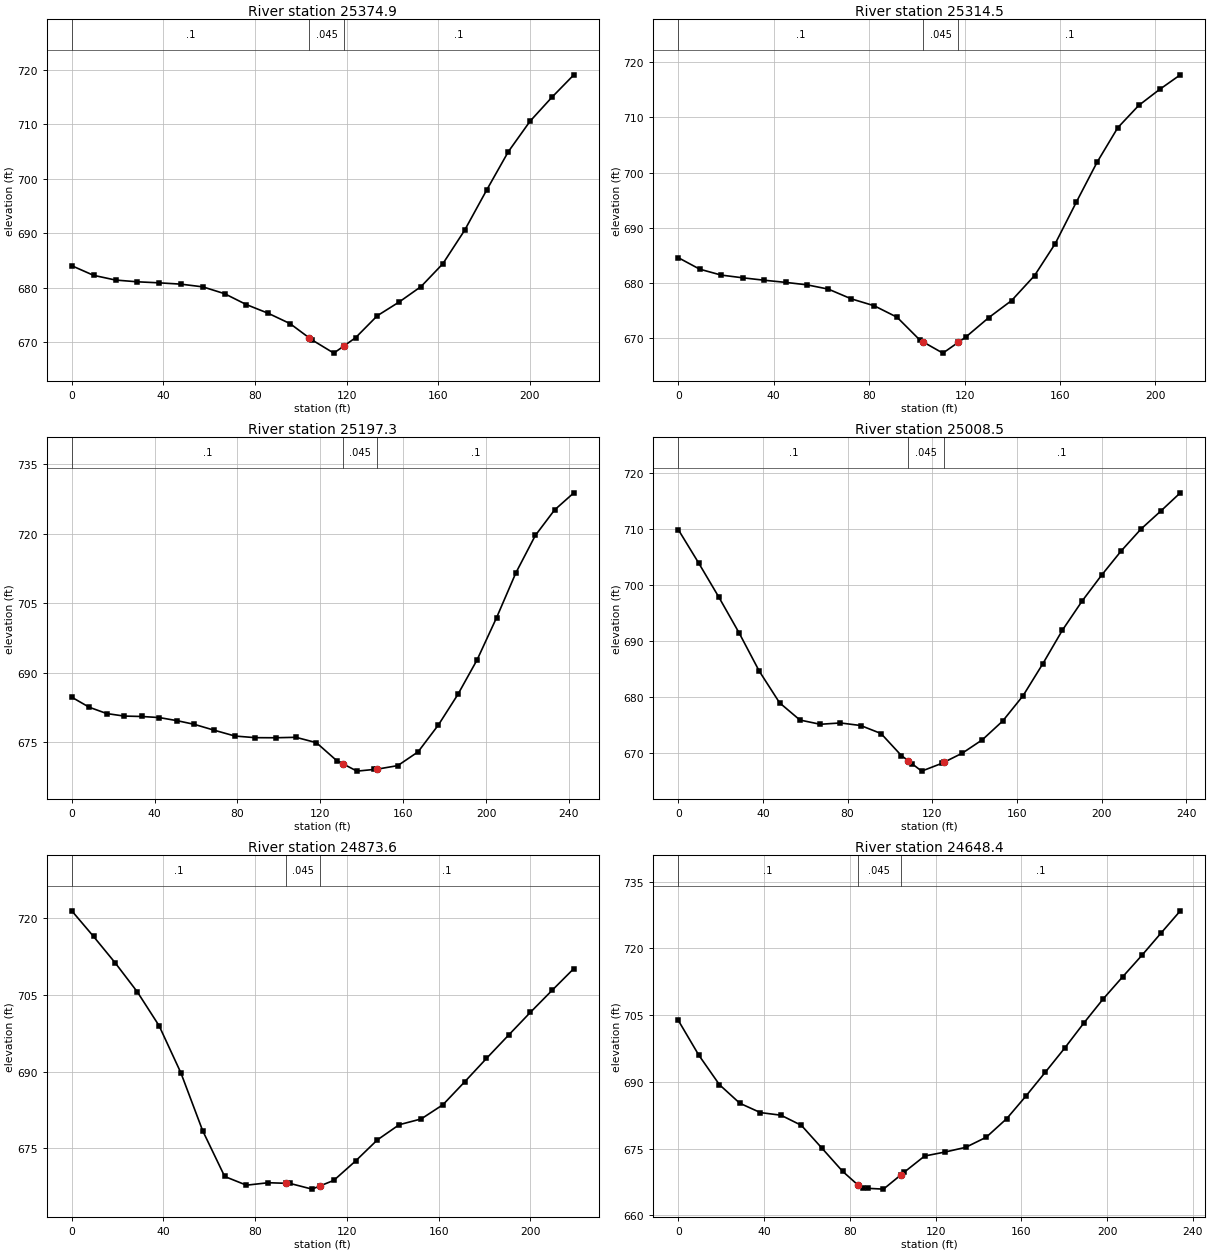
Type RM Length L Ch R = 1 ,25374.9 ,52.5,60.4,67.7
XS GIS Cut Line= 2
     1759011.925      480472.104     1759224.164      480526.791
#Sta/Elev= 26
       0  684.02     9.5  682.26    19.1  681.39    28.6  681.07    38.1  680.88
    47.6  680.64    57.2  680.14    66.7  678.89    76.2  676.89    85.8  675.28
    95.3  673.39   103.7  670.76   104.8  670.42   114.4  667.97   118.7  669.25
   123.9   670.8   133.4  674.84   142.9  677.35   152.5   680.2     162  684.38
   171.5  690.52   181.1  697.89   190.6  704.97   200.1  710.57   209.6  714.95
   219.2  719.08
#Mann= 3 , 0 , 0
       0      .1       0   103.7    .045       0   118.7      .1       0
Bank Sta=103.7,118.7
XS Rating Curve= 0 ,0
Exp/Cntr=0.3,0.1

Type RM Length L Ch R = 1 ,25314.5 ,96.4,117.2,137.7
XS GIS Cut Line= 4
      1758999.41      480480.278     1759044.983      480523.681
     1759117.683      480570.339     1759168.681      480603.976
#Sta/Elev= 26
       0  684.61       9  682.52      18  681.45      27  680.96      36  680.52
      45  680.13    53.9  679.69    62.9  678.91    72.5  677.15    82.1   675.9
    91.7  673.82   101.3  669.67   102.4   669.4   110.9  667.32   117.4  669.29
   120.5  670.23   130.1  673.74   139.7  676.84   149.3  681.35     158  687.16
   166.8  694.64   175.5  701.87   184.2  708.14     193  712.18   201.7  715.06
   210.4  717.71
#Mann= 3 , 0 , 0
       0      .1       0   102.4    .045       0   117.4      .1       0
Bank Sta=102.4,117.4
XS Rating Curve= 0 ,0
Exp/Cntr=0.3,0.1

Type RM Length L Ch R = 1 ,25197.3 ,185.5,188.7,191.8
XS GIS Cut Line= 4
     1758984.581      480490.333     1758992.393      480548.927
     1759005.414      480666.114     1758998.904      480731.218
#Sta/Elev= 29
       0  684.75     8.4  682.59    16.9  681.22    25.3  680.68    33.8  680.59
    42.2  680.36    50.7   679.7    59.1   678.9    68.9  677.61    78.8  676.37
    88.6  676.02    98.4     676   108.2   676.1   118.1  674.94   127.9  671.07
   131.1  670.33   137.7   668.8   146.1  669.17   147.5  669.23   157.4  669.99
   167.2  672.96     177  678.76   186.4  685.34   195.7  692.82   205.1  701.92
   214.4  711.57   223.8  719.65   233.1  725.16   242.4  728.85
#Mann= 3 , 0 , 0
       0      .1       0   131.1    .045       0   147.5      .1       0
Bank Sta=131.1,147.5
XS Rating Curve= 0 ,0
Exp/Cntr=0.3,0.1

Type RM Length L Ch R = 1 ,25008.5 ,157.3,134.9,112.3
XS GIS Cut Line= 3
     1758834.841      480443.458     1758828.331      480606.218
     1758842.654      480679.135
#Sta/Elev= 29
       0  709.98     9.6  704.03    19.2  697.89    28.8  691.48    38.3  684.66
    47.9  679.01    57.5  675.94    67.1  675.18    76.6  675.42    86.2  674.96
    95.8  673.53   105.4   669.6  108.72  668.65   110.6  668.09     115  666.81
   124.6  668.21   125.6   668.4   134.2  670.02   143.7  672.42   153.3  675.77
   162.9  680.28   172.2  685.97   181.5     692   190.8   697.2     200  701.82
   209.3  706.17   218.6  710.06   227.9  713.26   237.2  716.54
#Mann= 3 , 0 , 0
       0      .1       0  108.72    .045       0   125.6      .1       0
Bank Sta=108.72,125.6
XS Rating Curve= 0 ,0
Exp/Cntr=0.3,0.1

Type RM Length L Ch R = 1 ,24873.6 ,228.3,225.2,221.9
XS GIS Cut Line= 2
     1758636.925      480554.135     1758814.008      480683.041
#Sta/Elev= 26
       0  721.39     9.5  716.38      19  711.19    28.6  705.55    38.1  698.93
    47.6  689.73    57.1  678.43    66.7  669.49    76.2  667.79    85.7  668.27
    93.4  668.16    95.2  668.13   104.8  667.02   108.4  667.67   114.3  668.73
   123.8  672.52   133.3  676.64   142.8   679.6   152.4  680.73   161.9  683.51
   171.4  687.99   180.9  692.56   190.5  697.09     200  701.54   209.5  705.85
     219  710.11
#Mann= 3 , 0 , 0
       0      .1       0    93.4    .045       0   108.4      .1       0
Bank Sta=93.4,108.4
XS Rating Curve= 0 ,0
Exp/Cntr=0.3,0.1

Type RM Length L Ch R = 1 ,24648.4 ,236.9,235.7,234.6
XS GIS Cut Line= 3
     1758560.102      480780.697     1758695.518      480852.312
     1758768.435      480887.468
#Sta/Elev= 29
       0  703.84     9.6     696    19.2  689.38    28.7  685.21    38.3  683.11
    47.9  682.52    57.4  680.25      67  675.12    76.6  669.94   83.92  666.79
    86.2  666.15    88.7  666.09    95.7  665.92   103.7  669.07   105.3   669.7
   114.9  673.36   124.5  674.26     134   675.3   143.6  677.57   153.2  681.77
   162.2  686.87   171.2   692.2   180.2   697.6   189.2  703.27   198.2  708.67
   207.2  713.59   216.2  718.43   225.1  723.42   234.1  728.42
#Mann= 3 , 0 , 0
       0      .1       0   83.92    .045       0   103.7      .1       0
Bank Sta=83.92,103.7
XS Rating Curve= 0 ,0
Exp/Cntr=0.3,0.1

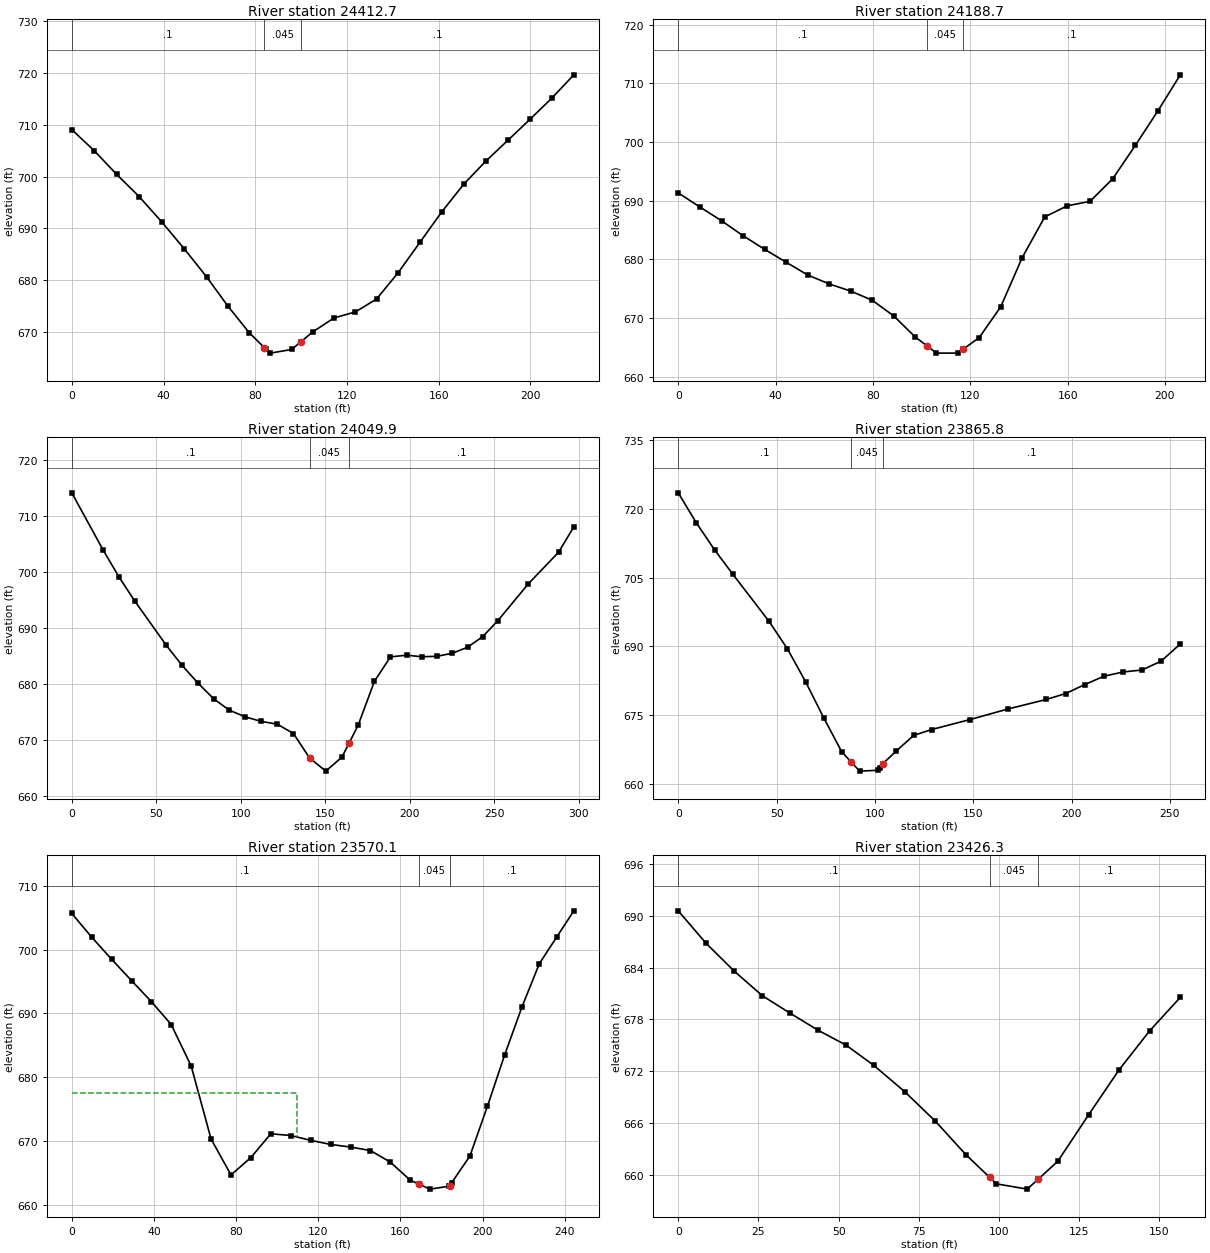
Type RM Length L Ch R = 1 ,24412.7 ,223,224,225
XS GIS Cut Line= 4
     1758487.185      480999.447     1758535.362      481033.302
     1758610.883      481068.458     1758685.102      481087.989
#Sta/Elev= 27
       0  709.05     9.8  704.98    19.6   700.4    29.4  696.13    39.2  691.27
    49.1  686.04    58.9   680.6    68.1     675    77.4  669.88   83.92  667.04
    84.9  666.68    86.6  665.96    95.9  666.67    99.9  668.15   105.2   670.1
   114.4  672.75   123.7  673.91   132.9   676.4   142.2  681.41   151.8  687.32
   161.4  693.24     171  698.58   180.6  703.01   190.2  707.01   199.7     711
   209.3  715.12   218.9  719.61
#Mann= 3 , 0 , 0
       0      .1       0   83.92    .045       0    99.9      .1       0
Bank Sta=83.92,99.9
XS Rating Curve= 0 ,0
Exp/Cntr=0.3,0.1

Type RM Length L Ch R = 1 ,24188.7 ,138.1,138.8,139.2
XS GIS Cut Line= 4
     1758414.268      481184.343     1758448.122      481236.427
     1758518.435      481272.885     1758573.122      481308.041
#Sta/Elev= 26
       0  691.34     8.9  688.94    17.8  686.59    26.6  684.06    35.5  681.73
    44.4  679.52    53.2  677.36    62.1  675.83    70.9  674.62    79.7  673.06
    88.5  670.41    97.3  666.84   102.2   665.3   106.1  664.07   114.9  664.06
   117.2  664.76   123.7  666.72   132.5  671.94   141.3  680.29   150.6  687.25
   159.9  689.15   169.2   689.9   178.5  693.73   187.8  699.41     197  705.25
   206.3  711.44
#Mann= 3 , 0 , 0
       0      .1       0   102.2    .045       0   117.2      .1       0
Bank Sta=102.2,117.2
XS Rating Curve= 0 ,0
Exp/Cntr=0.3,0.1

Type RM Length L Ch R = 1 ,24049.9 ,190.5,184.1,177.8
XS GIS Cut Line= 4
      1758284.06      481364.031     1758396.039      481364.031
      1758471.56      481405.697     1758569.216      481390.072
#Sta/Elev= 30
       0  714.16    18.7  703.87      28   699.1    37.3  694.82      56  686.89
    65.3  683.33    74.6   680.2      84  677.36    93.3  675.32   102.6  674.15
     112  673.34   121.6  672.84   131.2  671.16   140.7  666.81   150.3  664.45
   159.9  666.96   164.1  669.46   169.5  672.68   179.1   680.5   188.6  684.86
   198.2  685.16   207.2  684.88   216.2  684.96   225.2  685.51   234.2  686.58
   243.2  688.48   252.2  691.35   270.2  697.92   288.1  703.56   297.1   708.1
#Mann= 3 , 0 , 0
       0      .1       0   140.7    .045       0   164.1      .1       0
Bank Sta=140.7,164.1
XS Rating Curve= 0 ,0
Exp/Cntr=0.3,0.1

Type RM Length L Ch R = 1 ,23865.8 ,284.8,295.8,307.3
XS GIS Cut Line= 4
     1758268.435      481563.249     1758330.935      481546.322
     1758393.435      481560.645     1758519.737      481554.135
#Sta/Elev= 27
       0  723.42     9.2   716.9    18.5     711    27.8  705.69    46.2  695.45
    55.5   689.5    64.8   682.3    73.9  674.55    83.1  667.12    87.7  664.98
    92.2  662.89   101.4  663.07   102.7  663.65   103.9  664.46   110.6  667.16
   119.7  670.66   128.9  671.94   148.3   674.1   167.8  676.42   187.2  678.48
     197  679.77   206.7  681.71   216.4  683.52   226.2  684.46   235.9  684.89
   245.6  686.83   255.3  690.55
#Mann= 3 , 0 , 0
       0      .1       0    87.7    .045       0   103.9      .1       0
Bank Sta=87.7,103.9
XS Rating Curve= 0 ,0
Exp/Cntr=0.3,0.1

Type RM Length L Ch R = 1 ,23570.1 ,133.9,143.8,152.7
XS GIS Cut Line= 4
      1758252.81      481723.406     1758281.456      481762.468
     1758394.737      481853.614     1758423.383      481895.281
#Sta/Elev= 30
       0  705.69     9.7  701.97    19.4   698.5    29.1  695.15    38.8  691.84
    48.4  688.27    58.1  681.78    67.8  670.32    77.5  664.67    87.2  667.41
    96.9  671.13   106.6  670.86   116.3   670.1     126  669.46   135.7  669.05
   145.4   668.5   155.1  666.68   164.8  663.84   168.8  663.26   174.4  662.45
   183.8  662.91   184.1  662.92   184.9  663.44   193.8  667.64   202.3  675.41
   210.7  683.48   219.1  690.99   227.6  697.81     236  701.96   244.4   706.1
#Mann= 3 , 0 , 0
       0      .1       0   168.8    .045       0   184.1      .1       0
#XS Ineff= 2 , 0
          109.61  677.54
Permanent Ineff=
       F       F
Bank Sta=168.8,184.1
XS Rating Curve= 0 ,0
Exp/Cntr=0.3,0.1

Type RM Length L Ch R = 1 ,23426.3 ,201.4,177.1,152.3
XS GIS Cut Line= 3
     1758203.331      481831.479     1758242.393      481878.354
      1758284.06      481964.291
#Sta/Elev= 20
       0  690.57     8.7   686.8    17.4   683.6    26.2  680.74    34.9   678.7
    43.6  676.73    52.3  675.01      61  672.65    70.6  669.61    80.1  666.21
    89.7   662.3    97.1  659.67    99.2  658.93   108.8  658.32   112.1  659.44
   118.3  661.54   127.9  666.92   137.4  672.14     147  676.69   156.5  680.54
#Mann= 3 , 0 , 0
       0      .1       0    97.1    .045       0   112.1      .1       0
Bank Sta=97.1,112.1
XS Rating Curve= 0 ,0
Exp/Cntr=0.3,0.1

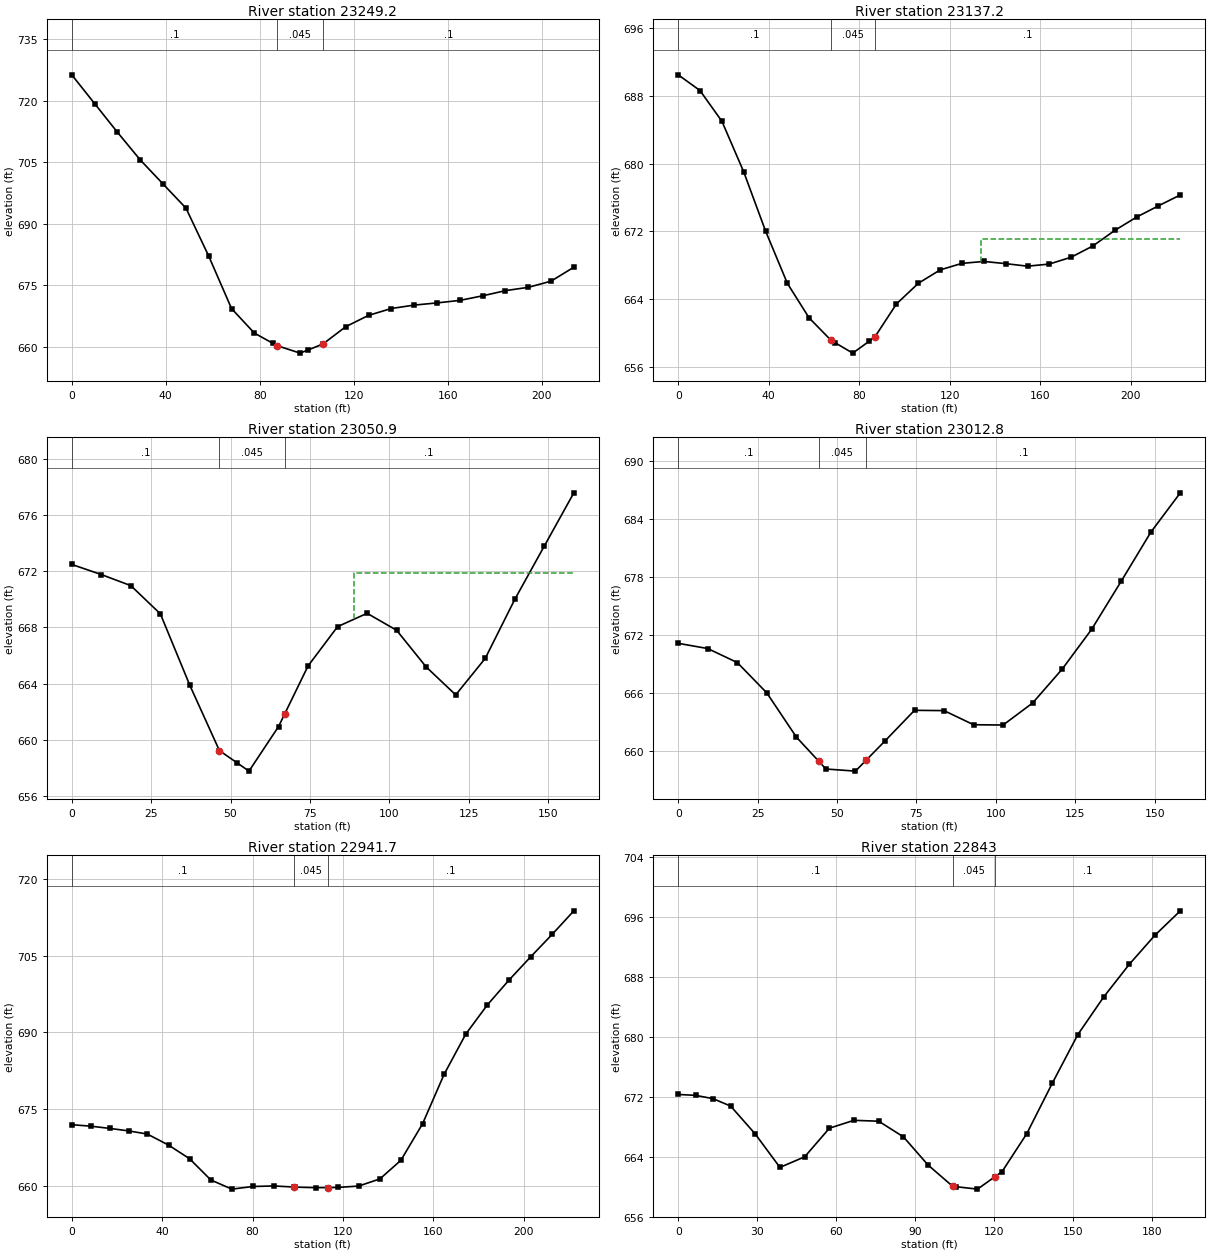
Type RM Length L Ch R = 1 ,23249.2 ,121.9,112,102
XS GIS Cut Line= 2
     1758060.102      482037.208     1758273.643      482046.322
#Sta/Elev= 25
       0  726.33     9.7  719.33    19.4  712.34    29.2  705.53    38.9  699.66
    48.6   693.8    58.3  682.08      68  669.29    77.7  663.31    85.5  660.83
    87.4  660.23    97.2  658.41   100.5  659.17   106.9  660.63   116.6  664.86
   126.3  667.62     136   669.3   145.7  670.13   155.4  670.66   165.2  671.28
   174.9   672.4   184.6  673.66   194.3  674.47     204  675.97   213.7  679.38
#Mann= 3 , 0 , 0
       0      .1       0    87.4    .045       0   106.9      .1       0
Bank Sta=87.4,106.9
XS Rating Curve= 0 ,0
Exp/Cntr=0.3,0.1

Type RM Length L Ch R = 1 ,23137.2 ,84.8,86.3,88
XS GIS Cut Line= 2
     1758119.997      482175.229     1758324.425      482089.291
#Sta/Elev= 26
       0  690.46     9.6  688.61    19.3  684.98    28.9  679.04    38.6  672.03
    48.2  665.88    57.8  661.81    67.5  659.16    69.4  658.86    77.1  657.65
    84.4  659.06    86.8  659.53    96.4  663.45   106.1  665.89   115.7  667.46
   125.3  668.23     135  668.46   144.6   668.2   154.3   667.9   163.9  668.15
   173.6  668.96   183.2  670.29   192.8  672.11   202.5  673.69   212.1  675.01
   221.8   676.3
#Mann= 3 , 0 , 0
       0      .1       0    67.5    .045       0    86.8      .1       0
#XS Ineff= 2 , 0
                          133.97          671.12
Permanent Ineff=
       F       F
Bank Sta=67.5,86.8
XS Rating Curve= 0 ,0
Exp/Cntr=0.3,0.1

Type RM Length L Ch R = 1 ,23050.9 ,38.1,38,38.1
XS GIS Cut Line= 2
     1758173.383      482241.635     1758323.122      482190.854
#Sta/Elev= 20
       0  672.49     9.3  671.77    18.6  670.98    27.9  668.97    37.2  663.87
    46.5  659.23      52  658.37    55.8  657.77    65.1  660.94      67  661.82
    74.4  665.26    83.7  668.06      93  669.01   102.3   667.8   111.6  665.19
   120.9   663.2   130.2   665.8   139.5     670   148.8   673.8   158.1  677.59
#Mann= 3 , 0 , 0
       0      .1       0    46.5    .045       0      67      .1       0
#XS Ineff= 2 , 0
                           88.72           671.9
Permanent Ineff=
       F       F
Bank Sta=46.5,67
XS Rating Curve= 0 ,0
Exp/Cntr=0.3,0.1

Type RM Length L Ch R = 1 ,23012.8 ,45.1,71.1,94.1
XS GIS Cut Line= 2
     1758195.518      482274.187     1758345.258      482223.406
#Sta/Elev= 20
       0  671.18     9.3  670.64    18.6  669.19    27.9  666.05    37.2  661.48
    44.2     659    46.5  658.18    55.8  657.96    59.2   659.1    65.1  661.08
    74.4  664.25    83.7  664.22      93  662.76   102.3  662.73   111.6  665.01
   120.9  668.51   130.2  672.64   139.5  677.61   148.8  682.67   158.1  686.75
#Mann= 3 , 0 , 0
       0      .1       0    44.2    .045       0    59.2      .1       0
Bank Sta=44.2,59.2
XS Rating Curve= 0 ,0
Exp/Cntr=0.3,0.1

Type RM Length L Ch R = 1 ,22941.7 ,86.7,98.7,112.1
XS GIS Cut Line= 4
     1758170.417      482273.898     1758202.969      482281.493
     1758291.945      482349.852     1758351.624      482397.596
#Sta/Elev= 27
       0  671.94     8.4  671.65    16.7  671.22    25.1  670.73    33.4  670.11
    42.8  667.95    52.1  665.28    61.5  661.12    70.8  659.32    80.2  659.84
    89.5  659.94    98.2  659.73    98.9  659.71   108.2   659.6   113.2  659.63
   117.6  659.65   126.9  659.92   136.3  661.32   145.6  664.97   155.2  672.14
   164.7   681.8   174.3  689.69   183.8  695.38   193.4  700.26     203  704.82
   212.5  709.21   222.1  713.83
#Mann= 3 , 0 , 0
       0      .1       0    98.2    .045       0   113.2      .1       0
Bank Sta=98.2,113.2
XS Rating Curve= 0 ,0
Exp/Cntr=0.3,0.1

Type RM Length L Ch R = 1 ,22843   ,256.8,249.1,242.3
XS GIS Cut Line= 4
     1758153.852      482267.677     1758164.268      482284.604
      1758190.31      482393.979     1758218.956       482444.76
#Sta/Elev= 24
       0  672.32     6.6   672.2    13.2  671.76    19.9  670.77    29.2  667.06
    38.6  662.59      48     664    57.4  667.82    66.7  668.87    76.1  668.75
    85.5  666.66    94.8  662.92   104.2  660.06   105.3  660.02   113.6  659.69
   120.3  661.36   122.9  662.01   132.3  667.08     142  673.82   151.7  680.31
   161.5  685.32   171.2  689.67   180.9  693.54   190.6  696.82
#Mann= 3 , 0 , 0
       0      .1       0   104.2    .045       0   120.3      .1       0
Bank Sta=104.2,120.3
XS Rating Curve= 0 ,0
Exp/Cntr=0.3,0.1