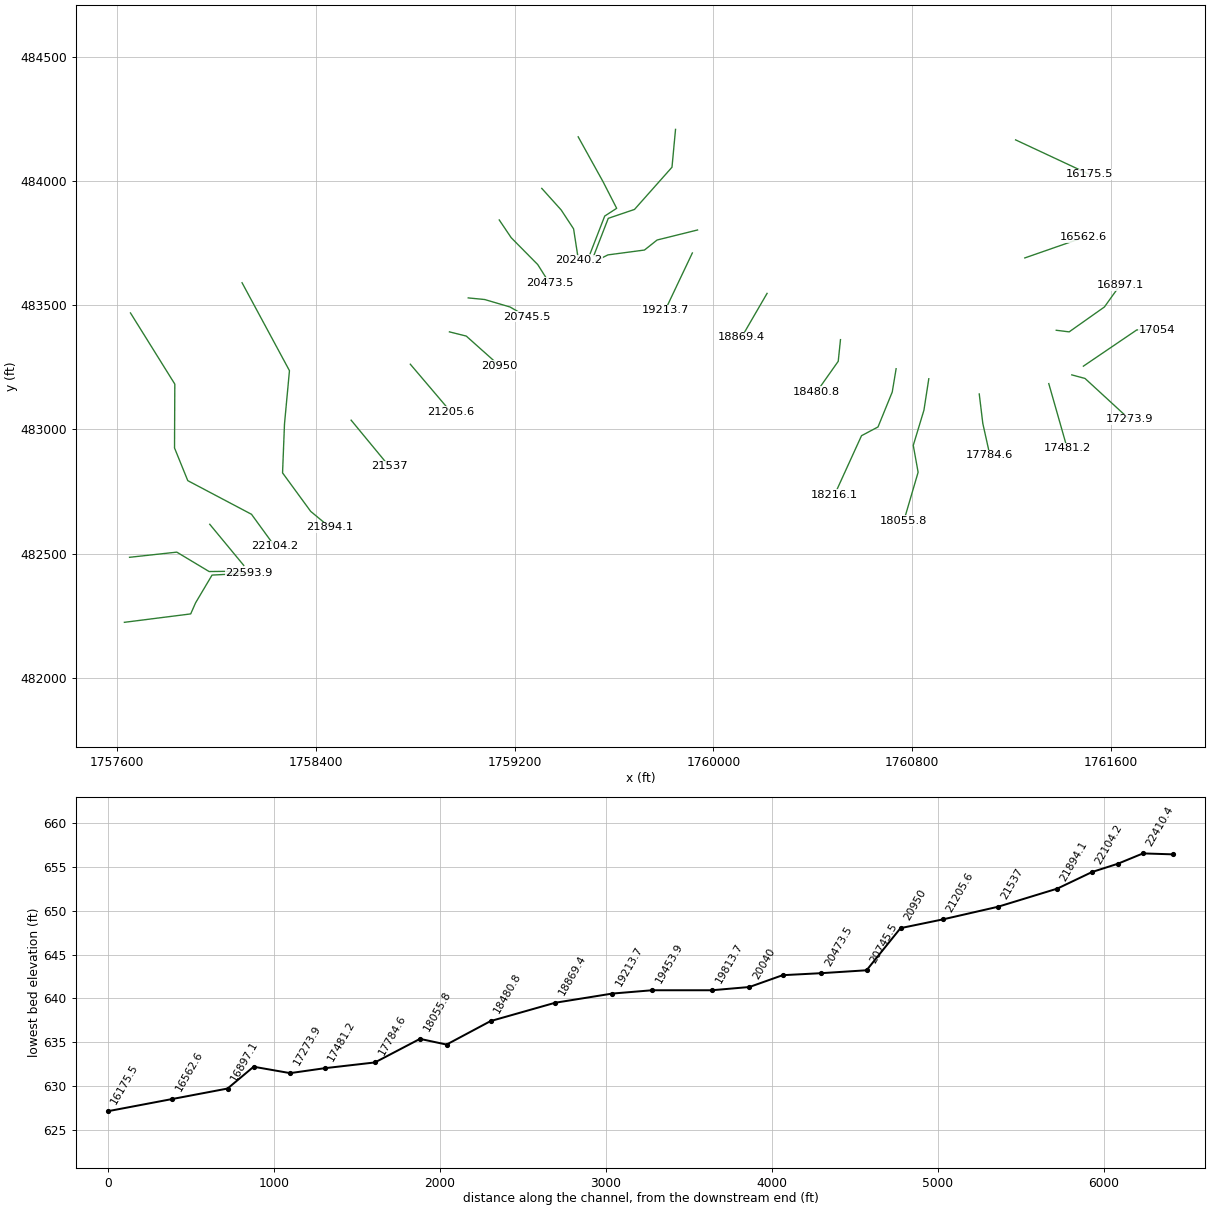
HEC-RAS study TRACEFORK.prj: TRACEFORK

--- TRACEFORK.g01 (geometry) --- (continued)

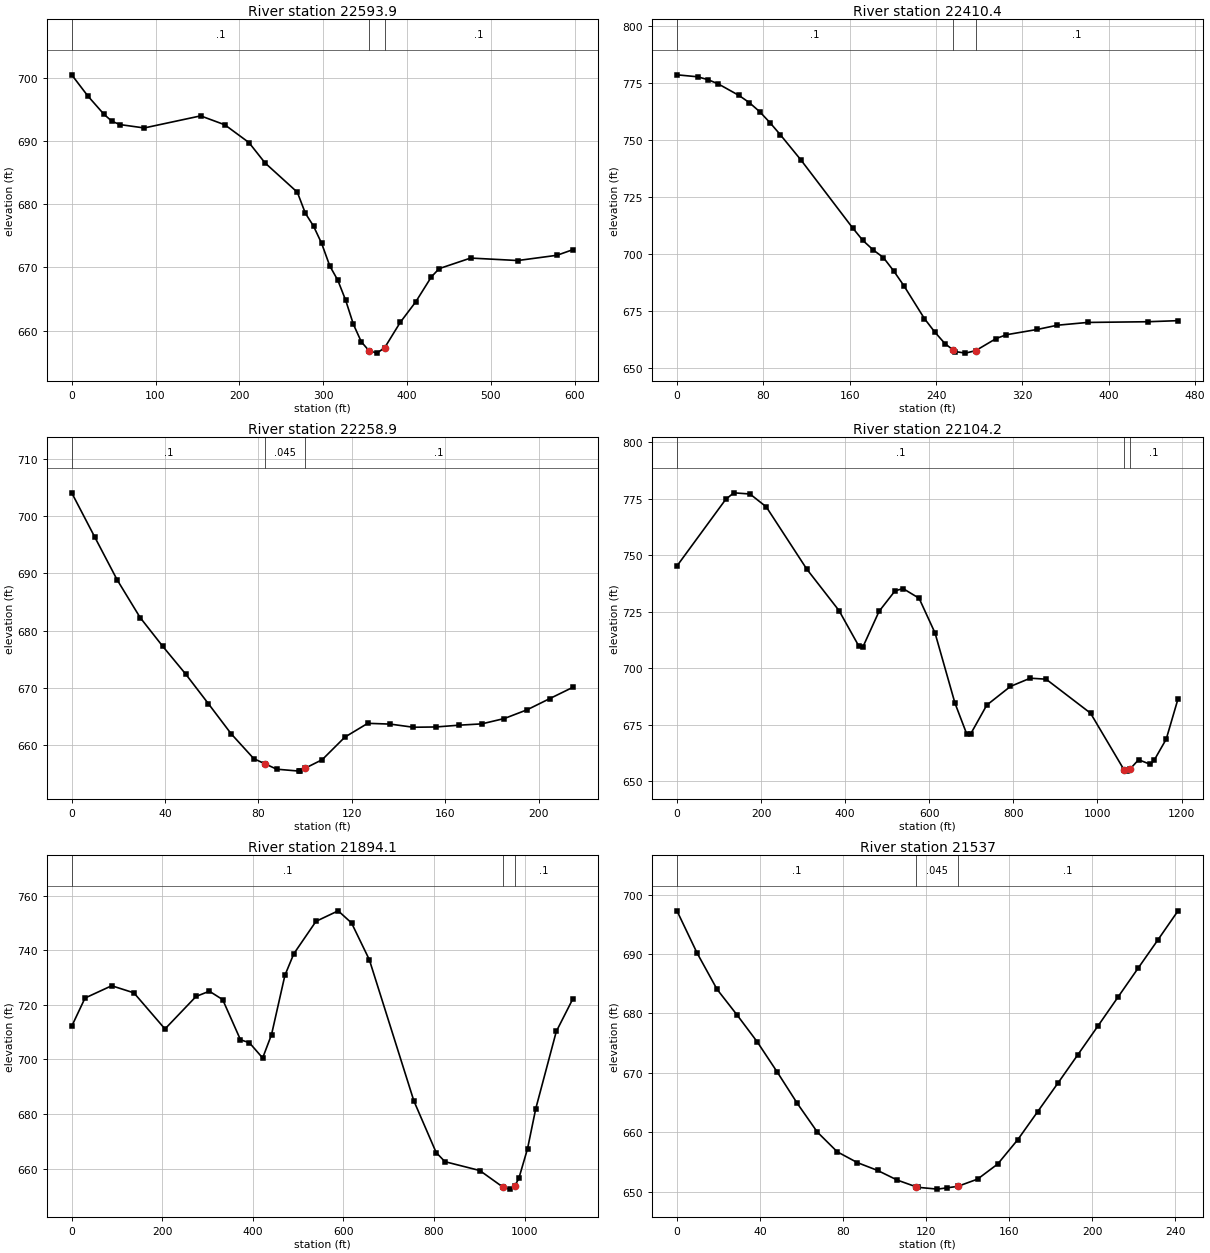
Type RM Length L Ch R = 1 ,22593.9 ,219.4,183.4,147.6
XS GIS Cut Line= 5
     1757629.112      482223.406     1757896.039       482257.26
      1757915.57      482301.531     1757981.977       482413.51
     1758131.716      482421.322
#Sta/Elev= 30
       0  700.43    19.2  697.09    38.4   694.2      48  693.08    57.7  692.56
    86.5  692.03   153.8  693.94   182.6  692.53   211.4  689.72   230.6   686.5
   269.1  681.87   278.7  678.54   288.4  676.52   298.1  673.78   307.8  670.22
   317.4  667.95   326.8  664.77     336  660.98   345.4  658.22   354.6  656.81
     364  656.43   373.3  657.29   391.8  661.28   410.4  664.55     429  668.49
   438.3  669.79   475.8  671.46     532  671.07   578.8   671.9   597.6  672.78
#Mann= 3 , 0 , 0
       0      .1       0   354.6    .045       0   373.3      .1       0
Bank Sta=354.6,373.3
XS Rating Curve= 0 ,0
Exp/Cntr=0.3,0.1

Type RM Length L Ch R = 1 ,22410.4 ,159.3,151.5,143.7
XS GIS Cut Line= 4
     1757649.945      482485.124      1757840.05      482505.958
     1757970.258      482427.833     1758091.352      482429.135
#Sta/Elev= 30
       0  778.61    19.1  777.75    28.7  776.48    38.2  774.63    57.4  769.57
    66.9  766.45    76.5  762.49    86.1  757.64    95.6   752.4   114.8  741.27
   162.6  711.53   172.1  706.02   181.7  701.83   191.2  698.46   200.7  692.63
   210.2   686.1   229.2   671.7   238.7  665.86   248.2  660.73   255.9   657.9
   257.7  657.24   267.2  656.54   276.7  657.63   295.6  662.92   305.1   664.6
   333.6  666.91   352.4  668.78   380.4     670   436.2  670.31   464.2  670.78
#Mann= 3 , 0 , 0
       0      .1       0   255.9    .045       0   276.7      .1       0
Bank Sta=255.9,276.7
XS Rating Curve= 0 ,0
Exp/Cntr=0.3,0.1

Type RM Length L Ch R = 1 ,22258.9 ,156.1,154.7,153.3
XS GIS Cut Line= 2
     1757972.862      482617.937     1758109.581      482452.572
#Sta/Elev= 26
       0  704.14     9.8  696.44    19.5  688.86    29.3  682.28      39  677.23
    48.8  672.38    58.5   667.2    68.3   661.9      78  657.54    82.9  656.62
    87.8   655.7    97.5  655.36    97.9  655.44  100.09  655.89   107.3  657.37
     117  661.32   126.8  663.74   136.5   663.6   146.3  663.05     156   663.1
   165.8  663.41   175.6  663.64   185.3  664.58   195.1  666.12   204.8  668.08
   214.6  670.04
#Mann= 3 , 0 , 0
       0      .1       0    82.9    .045       0  100.09      .1       0
Bank Sta=82.9,100.09
XS Rating Curve= 0 ,0
Exp/Cntr=0.3,0.1

Type RM Length L Ch R = 1 ,22104.2 ,209.8,210.1,210.3
XS GIS Cut Line= 6
     1757653.562      483468.921     1757832.099       483182.44
     1757830.935      482925.229      1757884.32      482793.718
     1758140.831      482658.302     1758234.581      482529.395
#Sta/Elev= 30
       0  745.23   115.7  774.63     135  777.56   173.6  777.04   212.2  771.36
   308.6  743.81   385.2  725.48   432.8  709.61   442.4  709.48   480.5  725.11
   518.6   734.2   537.6  735.19   575.7  730.92   613.7  715.52     661  684.53
   689.4  670.66   698.9  671.04   736.7  683.63   793.1  691.91   840.1  695.54
   877.7  695.11   983.5  680.06  1063.3  654.96  1069.7  654.42  1078.3  655.51
  1097.8  659.47    1126   657.4  1135.3  659.38  1163.5  668.58  1191.6  686.43
#Mann= 3 , 0 , 0
       0      .1       0  1063.3    .045       0  1078.3      .1       0
Bank Sta=1063.3,1078.3
XS Rating Curve= 0 ,0
Exp/Cntr=0.3,0.1

Type RM Length L Ch R = 1 ,21894.1 ,355.8,357.1,358.4
XS GIS Cut Line= 6
     1758102.781      483590.449     1758293.611      483236.528
     1758273.643      483021.583     1758265.831      482824.968
     1758379.112       482670.02     1758455.935      482606.218
#Sta/Elev= 30
       0  712.17    29.4  722.51    88.3  727.01   137.3  724.41     206  711.18
   274.6  723.09     304  725.01   333.4  721.93   372.7  707.22   392.3  706.15
   421.7  700.55   441.3  709.12   470.8  730.81   490.4   738.7   539.5   750.6
   588.5  754.45     618     750   657.3  736.54   755.7   684.8   804.9  665.92
   824.3  662.57   901.1  659.34   953.4  653.14   968.3  652.52   977.9   653.5
   987.5  656.47  1006.7  667.35  1024.8  681.96  1070.2  710.27  1106.5  722.12
#Mann= 3 , 0 , 0
       0      .1       0   953.4    .045       0   977.9      .1       0
Bank Sta=953.4,977.9
XS Rating Curve= 0 ,0
Exp/Cntr=0.3,0.1

Type RM Length L Ch R = 1 ,21537   ,330.8,331.4,331.5
XS GIS Cut Line= 2
     1758541.872      483037.208     1758695.518       482851.01
#Sta/Elev= 28
       0  697.25     9.7  690.15    19.3  684.06      29  679.72    38.6  675.25
    48.3  670.14    57.9   664.9    67.6  660.05    77.2  656.73    86.9  654.91
    96.6   653.6   106.2  651.96   115.3  650.83   115.9  650.76   125.5  650.45
   130.3  650.68   135.2  650.91   144.8  652.13   154.5  654.67   164.2  658.78
   173.8   663.5   183.5  668.27   193.1  673.05   202.8  677.89   212.4  682.72
   222.1  687.59   231.8  692.43   241.4  697.27
#Mann= 3 , 0 , 0
       0      .1       0   115.3    .045       0   135.2      .1       0
Bank Sta=115.3,135.2
XS Rating Curve= 0 ,0
Exp/Cntr=0.3,0.1

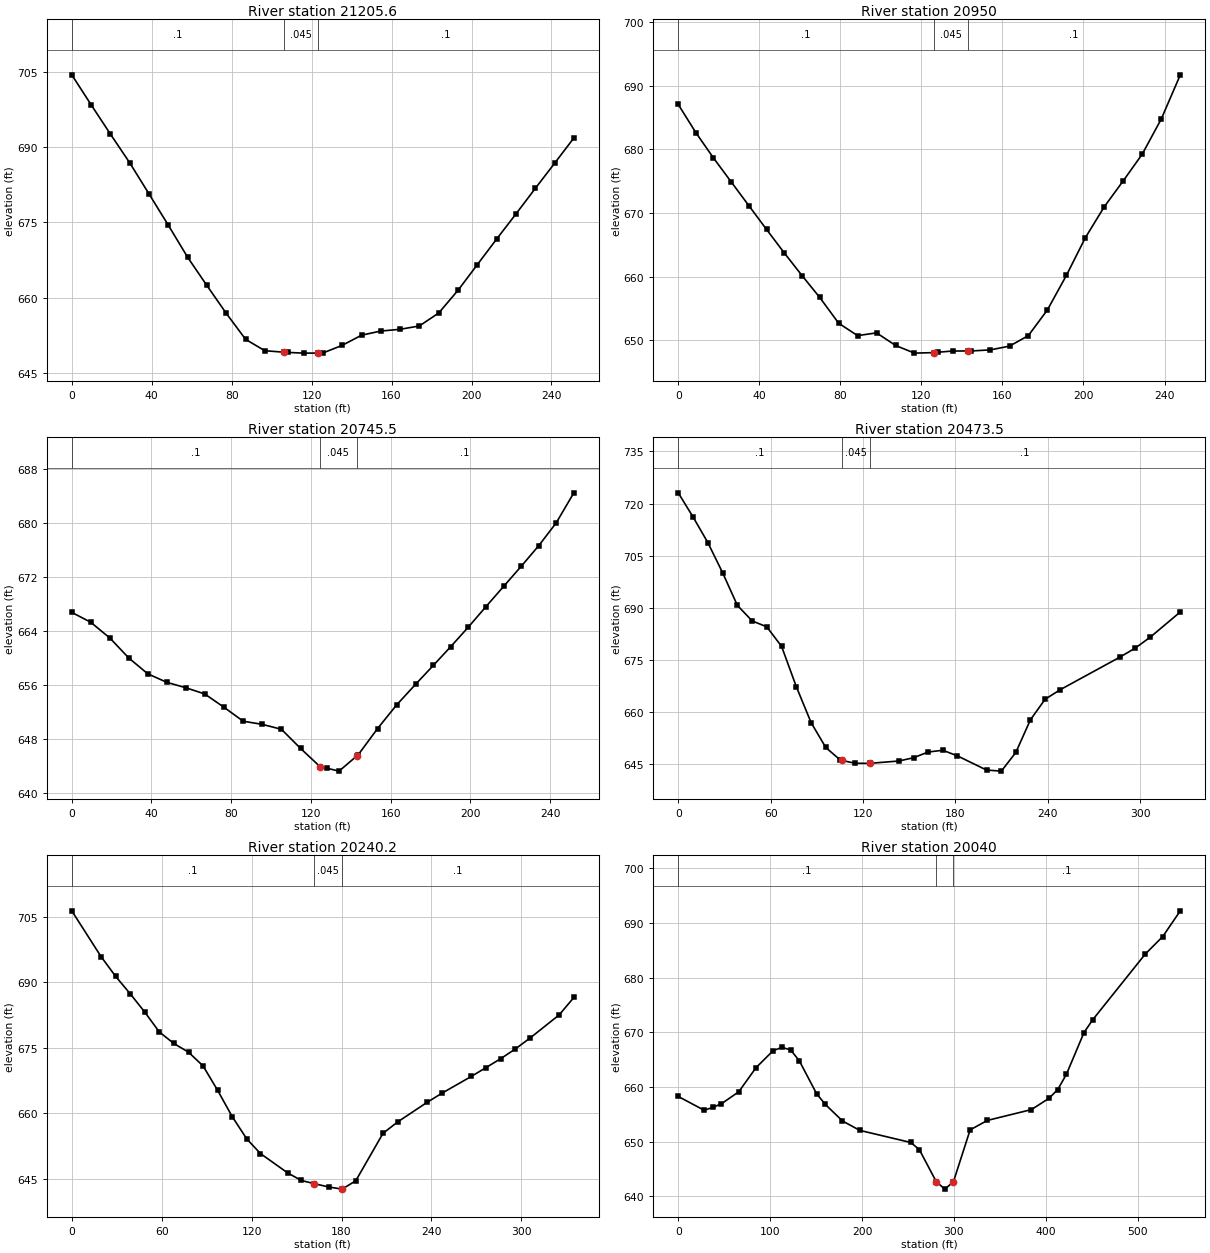
Type RM Length L Ch R = 1 ,21205.6 ,252.2,255.6,258.8
XS GIS Cut Line= 2
     1758780.154      483262.468     1758942.914      483071.062
#Sta/Elev= 29
       0  704.35     9.7  698.39    19.3  692.58      29  686.85    38.6   680.7
    48.3  674.45      58  668.05    67.6  662.46    77.3  656.92      87  651.74
    96.6  649.49   106.3  649.19   108.2  649.15     116  649.01   123.2  649.02
   125.6  649.03   135.3  650.56     145  652.58   154.6   653.4   164.3  653.75
   173.9  654.41   183.6  656.99   193.3  661.53   202.9   666.6   212.6  671.71
   222.3  676.72   231.9  681.76   241.6  686.78   251.2  691.79
#Mann= 3 , 0 , 0
       0      .1       0   106.3    .045       0   123.2      .1       0
Bank Sta=106.3,123.2
XS Rating Curve= 0 ,0
Exp/Cntr=0.3,0.1

Type RM Length L Ch R = 1 ,20950   ,194.4,204.5,214.8
XS GIS Cut Line= 3
     1758937.706      483392.677     1759005.414      483375.749
     1759138.227       483257.26
#Sta/Elev= 30
       0  687.07     8.7  682.64    17.4  678.66    26.2  674.88    34.9  671.15
    43.6  667.43    52.3  663.76    61.1  660.19    69.8  656.77    79.2   652.7
    88.5  650.76    97.9  651.19   107.3  649.21   116.6  648.01     126  648.09
   128.1  648.15   135.4  648.34   143.1  648.35   144.7  648.35   154.1  648.52
   163.5  649.11   172.8  650.76   182.2   654.8   191.6  660.23   200.9  666.12
   210.3  671.01   219.7   675.1     229  679.26   238.4  684.78   247.8  691.72
#Mann= 3 , 0 , 0
       0      .1       0     126    .045       0   143.1      .1       0
Bank Sta=126,143.1
XS Rating Curve= 0 ,0
Exp/Cntr=0.3,0.1

Type RM Length L Ch R = 1 ,20745.5 ,283.4,271.9,260.5
XS GIS Cut Line= 4
     1759013.227      483529.395     1759079.633      483522.885
     1759181.195      483492.937     1759250.206      483453.874
#Sta/Elev= 30
       0  666.73     9.5  665.27    19.1  662.93    28.6  659.97    38.1  657.63
    47.7  656.36    57.2  655.56    66.7  654.64    76.4  652.66      86   650.6
    95.6  650.13   105.2   649.4   114.8  646.56   124.5  643.88   127.9  643.64
   134.1   643.2   142.9  645.42   143.7  645.62   153.4   649.5     163  653.02
   172.6   656.1   181.4  658.87   190.2  661.67     199  664.56   207.8  667.58
   216.7  670.59   225.5  673.56   234.3  676.62   243.1  680.02   251.9  684.45
#Mann= 3 , 0 , 0
       0      .1       0   124.5    .045       0   142.9      .1       0
Bank Sta=124.5,142.9
XS Rating Curve= 0 ,0
Exp/Cntr=0.3,0.1

Type RM Length L Ch R = 1 ,20473.5 ,236.9,233.4,229.6
XS GIS Cut Line= 4
     1759138.227      483843.197     1759186.404      483771.583
     1759293.175       483663.51      1759340.05      483589.291
#Sta/Elev= 30
       0  723.08     9.6  716.14    19.2  708.75    28.8  700.06    38.4  690.64
      48  686.16    57.5  684.46    67.1  678.82    76.7  667.18    86.3  656.82
    95.8  649.68   105.3  646.04   106.3  645.95   114.8  645.14   124.3  645.11
   143.3  645.79   152.8  646.73   162.3  648.38   171.8  648.88   181.3  647.26
   200.2  643.18   209.8  642.87   219.2  648.26   228.7  657.68   238.2  663.58
     248  666.33     287  675.78   296.8  678.35   306.5  681.48     326  688.75
#Mann= 3 , 0 , 0
       0      .1       0   106.3    .045       0   124.3      .1       0
Bank Sta=106.3,124.3
XS Rating Curve= 0 ,0
Exp/Cntr=0.3,0.1

Type RM Length L Ch R = 1 ,20240.2 ,203.5,200.2,197.1
XS GIS Cut Line= 4
     1759309.378      483970.223     1759387.503      483883.417
     1759437.416      483807.462     1759456.948      483681.594
#Sta/Elev= 30
       0  706.41    19.5  695.94    29.2  691.42    38.9  687.44    48.7  683.21
    58.4  678.66    68.1  676.01    77.9  674.02    87.6  670.87    97.3  665.29
     107  659.28   116.8  654.13   125.9  650.79     144  646.37   153.1  644.63
   161.7   643.9   171.3  643.14   180.4  642.64   189.5  644.56   207.7  655.44
   217.5  658.05   237.1  662.53   246.9   664.6   266.5  668.45   276.3  670.47
   286.1  672.51   295.8  674.72   305.6  677.21   325.2  682.56     335  686.55
#Mann= 3 , 0 , 0
       0      .1       0   161.7    .045       0   180.4      .1       0
Bank Sta=161.7,180.4
XS Rating Curve= 0 ,0
Exp/Cntr=0.3,0.1

Type RM Length L Ch R = 1 ,20040   ,254.9,226.2,194.9
XS GIS Cut Line= 5
     1759455.935      484177.833     1759556.195      483996.843
     1759610.883      483890.072     1759562.706      483858.822
     1759504.112      483707.781
#Sta/Elev= 30
       0  658.24    28.2  655.72    37.6  656.24      47  656.91    65.8  659.09
    84.6   663.5   103.4  666.64   112.9  667.22   122.3  666.75   131.7  664.78
   150.5  658.76   159.9  656.81   178.7  653.76   197.5  652.04     253  649.82
   262.3  648.53   280.7  642.67     290  641.29   299.4  642.62   317.6  652.13
   336.4  653.86   384.3  655.84   403.4   657.9   412.9   659.5   422.4  662.31
   441.5  669.93     451  672.28   508.2   684.3   527.2   687.5   546.3   692.2
#Mann= 3 , 0 , 0
       0      .1       0   280.7    .045       0   299.4      .1       0
Bank Sta=280.7,299.4
XS Rating Curve= 0 ,0
Exp/Cntr=0.3,0.1

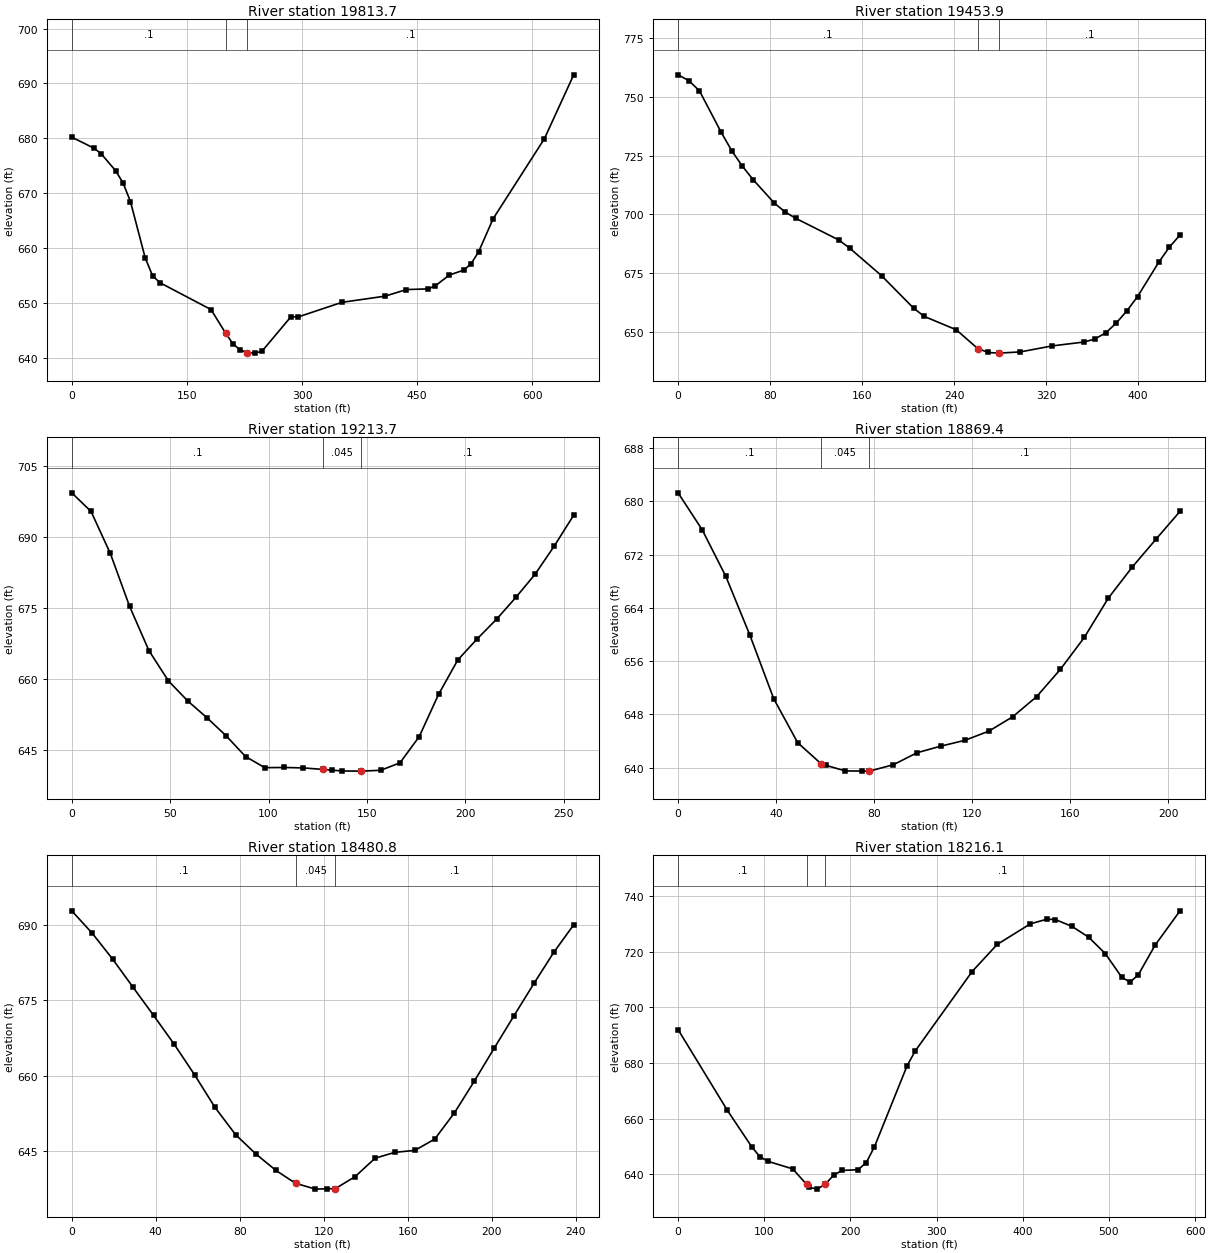
Type RM Length L Ch R = 1 ,19813.7 ,375.4,359.8,346.5
XS GIS Cut Line= 5
     1759847.862      484207.781     1759833.539      484055.437
     1759682.642      483885.587     1759577.029      483849.708
     1759518.435      483698.666
#Sta/Elev= 30
       0  680.22    28.7  678.24    38.2  677.23    57.4  674.07    66.9  671.87
    76.5  668.48    95.6  658.28   105.2  655.02   114.8  653.74   181.4  648.85
   200.4  644.55   209.8  642.65   219.3  641.49   228.8  641.02   238.2  640.92
   247.7  641.25   285.6  647.56     295  647.51   351.8  650.16   408.1  651.29
     436  652.49   463.9  652.61   473.2  653.13   491.8  655.13   510.8  656.04
   520.3  657.22   529.9  659.34   548.9  665.39   615.6  679.93   653.8  691.57
#Mann= 3 , 0 , 0
       0      .1       0   200.4    .045       0   228.8      .1       0
Bank Sta=200.4,228.8
XS Rating Curve= 0 ,0
Exp/Cntr=0.3,0.1

Type RM Length L Ch R = 1 ,19453.9 ,217.3,240.2,262.8
XS GIS Cut Line= 5
     1759936.404      483802.833     1759773.643      483762.468
     1759722.862      483722.104     1759575.727      483702.572
     1759526.247      483677.833
#Sta/Elev= 30
       0  759.41     9.3  756.96    18.6  752.58    37.3   735.1    46.6  727.13
    55.9  720.51    65.2   714.8    83.8  704.73    93.2  700.97   102.5  698.26
   139.7   689.1   149.1  685.64     177  673.84   204.8  660.03     214  656.55
   241.8  650.87   260.4  642.89   269.7  641.19   278.9  640.92   297.5  641.44
   325.3     644   353.2  645.67   362.4  646.98   371.7  649.51     381  653.79
   390.2  658.96   399.4  664.99   417.9  679.69   427.1  686.06   436.3  691.23
#Mann= 3 , 0 , 0
       0      .1       0   260.4    .045       0   278.9      .1       0
Bank Sta=260.4,278.9
XS Rating Curve= 0 ,0
Exp/Cntr=0.3,0.1

Type RM Length L Ch R = 1 ,19213.7 ,346.1,344.4,342.4
XS GIS Cut Line= 2
      1759915.57      483710.385     1759806.195      483479.916
#Sta/Elev= 28
       0  699.38     9.8  695.44    19.6  686.56    29.4  675.37    39.2  666.04
    49.1  659.64    58.9  655.39    68.7  651.83    78.5  647.99    88.3  643.63
    98.1  641.27   107.9  641.31   117.7  641.22   127.6   640.9   132.2  640.75
   137.4  640.57   147.2  640.54     157  640.72   166.8  642.29   176.6  647.84
   186.4  656.75   196.2  664.05     206  668.48   215.9  672.66   225.7  677.27
   235.5  682.18   245.3  688.18   255.1  694.65
#Mann= 3 , 0 , 0
       0      .1       0   127.6    .045       0   147.2      .1       0
Bank Sta=127.6,147.2
XS Rating Curve= 0 ,0
Exp/Cntr=0.3,0.1

Type RM Length L Ch R = 1 ,18869.4 ,390.5,388.5,386.7
XS GIS Cut Line= 2
     1760216.352      483547.624     1760113.487      483370.541
#Sta/Elev= 24
       0  681.26     9.8  675.74    19.5  668.71    29.3   659.9      39  650.38
    48.8  643.76    58.5  640.55    60.2  640.37    68.3  639.52    75.2   639.5
      78  639.49    87.8  640.44    97.5  642.25   107.3  643.25     117  644.11
   126.8  645.49   136.5  647.64   146.3  650.67     156  654.77   165.8  659.58
   175.5  665.43   185.3  670.11     195   674.3   204.8  678.48
#Mann= 3 , 0 , 0
       0      .1       0    58.5    .045       0      78      .1       0
Bank Sta=58.5,78
XS Rating Curve= 0 ,0
Exp/Cntr=0.3,0.1

Type RM Length L Ch R = 1 ,18480.8 ,259.3,264.8,269.9
XS GIS Cut Line= 3
     1760511.925      483361.427      1760502.81      483274.187
      1760415.57      483150.489
#Sta/Elev= 28
       0  692.84     9.8  688.35    19.5   683.2    29.2  677.61      39  671.99
    48.7  666.32    58.5  660.18    68.2   653.7      78  648.27    87.7  644.41
    97.2  641.14   106.6  638.56   106.8  638.54   116.1   637.4   121.8  637.47
   125.6  637.51     135   639.9   144.5  643.56   153.9  644.73   163.4  645.11
   172.9  647.37   182.3   652.6   191.8  658.94   201.2  665.46   210.7  671.97
   220.2  678.39   229.6  684.56   239.1  690.06
#Mann= 3 , 0 , 0
       0      .1       0   106.8    .045       0   125.6      .1       0
Bank Sta=106.8,125.6
XS Rating Curve= 0 ,0
Exp/Cntr=0.3,0.1

Type RM Length L Ch R = 1 ,18216.1 ,158.5,160.3,162.4
XS GIS Cut Line= 5
     1760735.883      483244.239     1760720.258      483150.489
     1760662.966      483009.864      1760596.56      482974.708
     1760488.487      482737.729
#Sta/Elev= 30
       0  691.99      57   663.1    85.5  649.91      95  646.33   104.5  644.68
     133  641.99   149.2  636.42     152  635.37   161.5  634.72     171  636.55
   180.5   639.7     190  641.42   208.9  641.69   218.4  644.25   227.9  649.92
   265.7  678.93   275.1  684.26   341.3  712.84   370.3  722.55   408.8  729.94
   428.1  731.63   437.8  731.49   457.1  729.04   476.4  725.17   495.7   719.3
     515  710.74   524.6  709.02   534.2  711.71   553.6  722.29   582.5  734.62
#Mann= 3 , 0 , 0
       0      .1       0   149.2    .045       0     171      .1       0
Bank Sta=149.2,171
XS Rating Curve= 0 ,0
Exp/Cntr=0.3,0.1

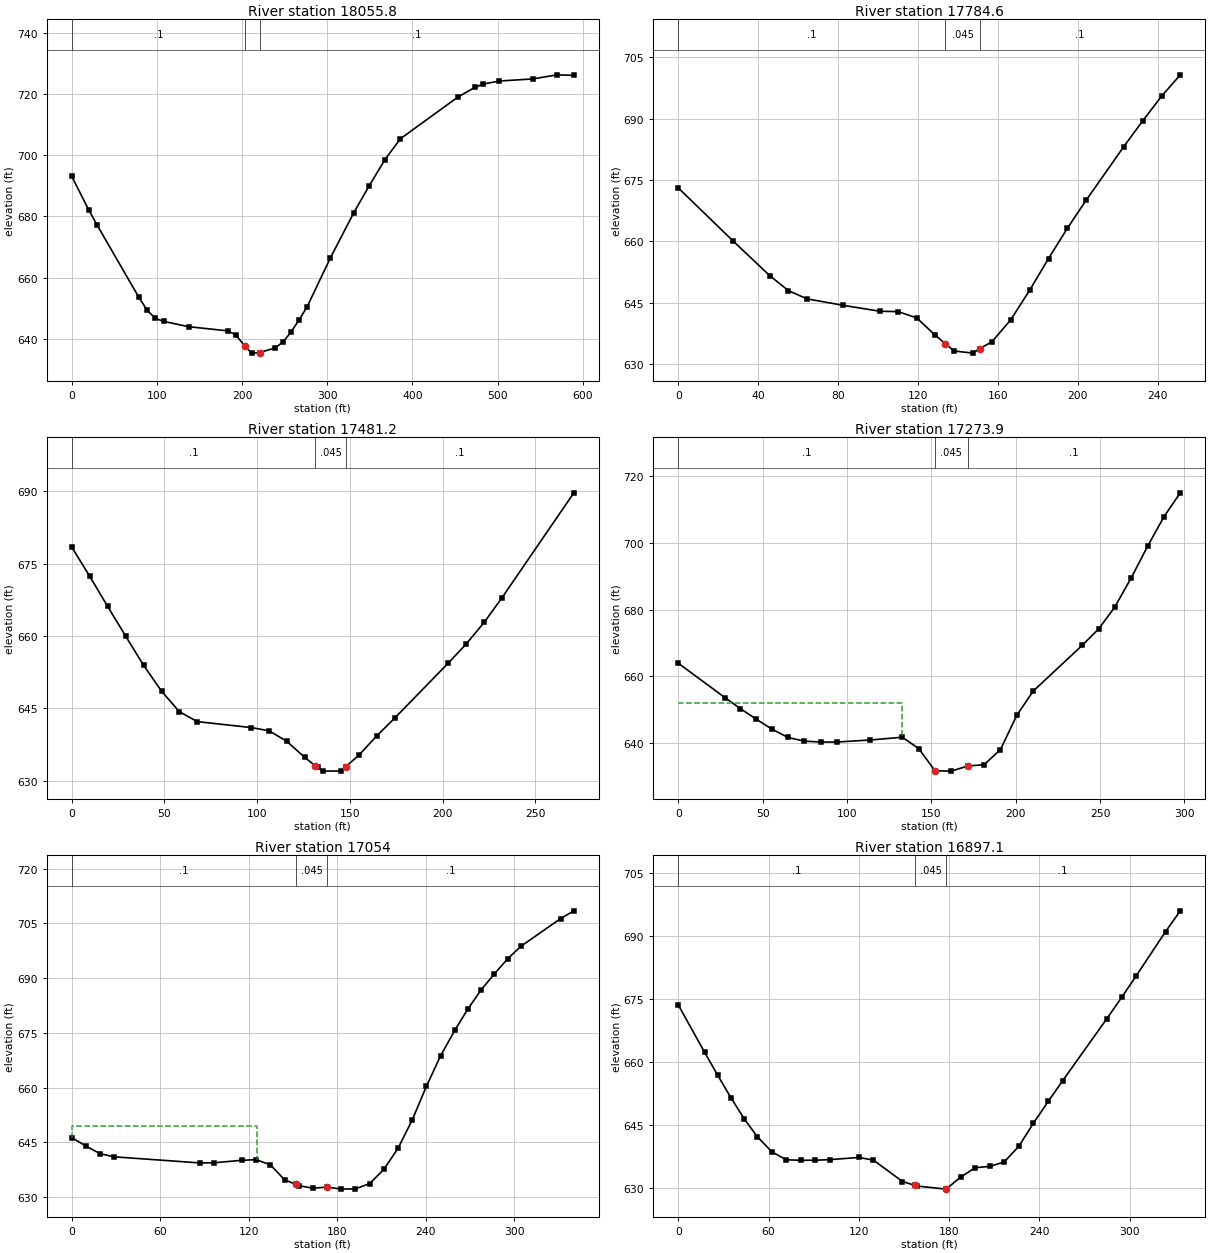
Type RM Length L Ch R = 1 ,18055.8 ,259.3,271.2,282.4
XS GIS Cut Line= 5
     1760867.393      483203.874     1760847.862      483077.572
     1760804.893      482935.645     1760824.425      482827.572
     1760767.133       482632.26
#Sta/Elev= 30
       0  693.12    19.7  682.25    29.5  677.31    78.6  653.68    88.5  649.36
    98.3   646.7   108.1  645.72   137.1  644.01   183.4  642.63   192.7  641.28
   203.3  637.66   211.2  635.37   220.5  635.56     239  637.08   248.3   639.1
   257.6  642.31   266.8  646.19   276.1  650.38   303.6  666.44     331  681.16
   349.3  690.07   367.6  698.53   385.9   705.4   453.8  719.09   473.2  722.15
   482.8  723.25   502.2  724.25     541  724.92   570.1  726.27   589.5  726.09
#Mann= 3 , 0 , 0
       0      .1       0   203.3    .045       0   220.5      .1       0
Bank Sta=203.3,220.5
XS Rating Curve= 0 ,0
Exp/Cntr=0.3,0.1

Type RM Length L Ch R = 1 ,17784.6 ,302,303.4,304.6
XS GIS Cut Line= 3
     1761070.518      483142.677     1761084.841      483024.187
     1761113.487      482895.281
#Sta/Elev= 24
       0  673.08    27.5  660.08    45.9  651.58    55.1  647.99    64.3  645.97
    82.6  644.36     101  642.92   110.2  642.82   119.4  641.29   128.8     637
   133.8  634.98   138.2   633.2   147.6  632.68  150.93  633.78   157.1  635.46
   166.5  640.84     176  648.08   185.4  655.81   194.8  663.17   204.2  670.02
   223.1  683.18   232.5  689.41     242  695.49   251.4  700.72
#Mann= 3 , 0 , 0
       0      .1       0   133.8    .045       0  150.93      .1       0
Bank Sta=133.8,150.93
XS Rating Curve= 0 ,0
Exp/Cntr=0.3,0.1

Type RM Length L Ch R = 1 ,17481.2 ,194.7,207.3,219.7
XS GIS Cut Line= 2
     1761350.466      483184.343     1761424.685      482923.927
#Sta/Elev= 25
       0  678.45     9.7  672.38    19.3  666.18      29  660.03    38.7  653.97
    48.4   648.6      58  644.35    67.7  642.28    96.7  641.05   106.4  640.38
     116  638.19   125.7  634.85  131.27  633.14   132.8  632.78   135.4  632.02
   145.1  632.05   147.8  632.96   154.7  635.27   164.4  639.28   174.1  642.98
   203.1  654.42   212.8   658.4   222.4  662.82   232.1  667.98   270.8  689.69
#Mann= 3 , 0 , 0
       0      .1       0  131.27    .045       0   147.8      .1       0
Bank Sta=131.27,147.8
XS Rating Curve= 0 ,0
Exp/Cntr=0.3,0.1

Type RM Length L Ch R = 1 ,17273.9 ,187,219.9,252.2
XS GIS Cut Line= 3
     1761442.914      483219.499       1761496.3      483205.177
     1761674.685      483041.114
#Sta/Elev= 26
       0  663.88    27.6  653.57    36.8  650.24    46.1  647.12    55.3  644.14
      65  641.57    74.7  640.47    84.4   640.2      94   640.2   113.4  640.79
   132.8  641.64   142.5  638.25   152.2  631.59   161.9  631.46   171.6     633
   181.3   633.4     191  637.93   200.7  648.25   210.4  655.49   239.5  669.27
   249.2  674.17   258.8  680.78   268.6  689.61   278.2     699   287.9  707.87
   297.6  715.05
#Mann= 3 , 0 , 0
       0      .1       0   152.2    .045       0   171.6      .1       0
#XS Ineff= 2 , 0
          132.86  652.02
Permanent Ineff=
       F       F
Bank Sta=152.2,171.6
XS Rating Curve= 0 ,0
Exp/Cntr=0.3,0.1

Type RM Length L Ch R = 1 ,17054   ,159.7,157,155.8
XS GIS Cut Line= 3
     1761489.789      483254.656     1761704.633      483400.489
     1761785.362      483401.791
#Sta/Elev= 30
       0  646.32     9.6  643.98    19.2  641.89    28.8  641.04    86.6  639.38
    96.2   639.4   115.4   640.1     125  640.26   134.6  638.87   144.3  634.76
     152  633.47   153.9  633.15   163.5  632.43   173.1  632.76   182.7  632.19
   192.3  632.26     202  633.72   211.6  637.61   221.2  643.39   230.8  651.12
   240.4  660.32     250   668.7   259.7  675.72   268.6   681.6   277.6  686.83
   286.6  691.23   295.6  695.35   304.5  698.74   331.4  706.34   340.4  708.47
#Mann= 3 , 0 , 0
       0      .1       0     152    .045       0   173.1      .1       0
#XS Ineff= 2 , 0
          125.86  649.59
Permanent Ineff=
       F       F
Bank Sta=152,173.1
XS Rating Curve= 0 ,0
Exp/Cntr=0.3,0.1

Type RM Length L Ch R = 1 ,16897.1 ,339.6,334.4,328
XS GIS Cut Line= 4
     1761380.414      483399.187     1761432.497      483392.677
     1761574.425      483492.937     1761636.925      483580.177
#Sta/Elev= 30
       0  673.55    17.5  662.28    26.2   656.8      35  651.46    43.7   646.5
    52.5   642.2    62.1   638.6    71.8  636.68    81.4  636.56    91.1  636.58
   100.8  636.72   120.1  637.24   129.7   636.6     149  631.51   157.3  630.59
   158.7  630.43     178   629.7   187.6  632.55   197.3   634.8     207  635.11
   216.6  636.17   226.3   639.9     236  645.39   245.8  650.56   255.5  655.54
   284.8  670.27   294.6  675.32   304.3  680.46   323.8  690.99   333.6  695.93
#Mann= 3 , 0 , 0
       0      .1       0   157.3    .045       0     178      .1       0
Bank Sta=157.3,178
XS Rating Curve= 0 ,0
Exp/Cntr=0.3,0.1

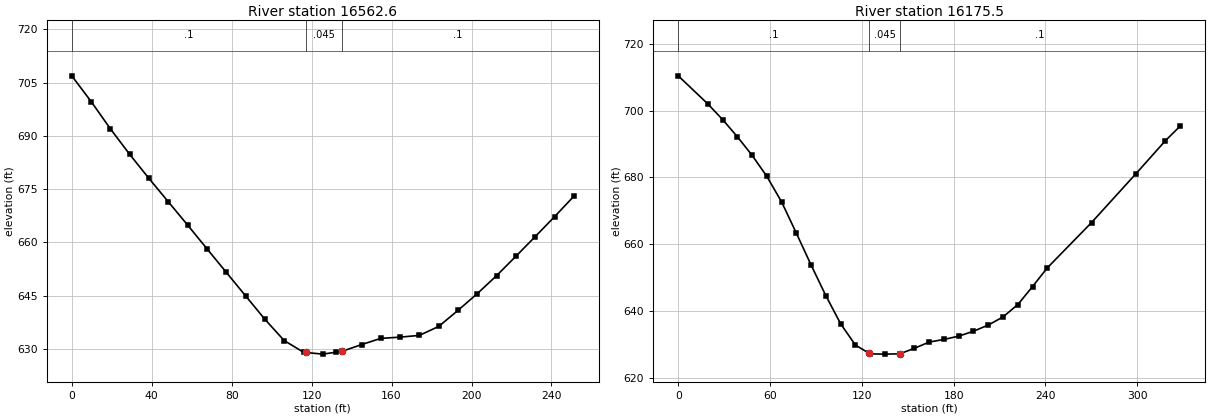
Type RM Length L Ch R = 1 ,16562.6 ,404.5,387.1,369.7
XS GIS Cut Line= 2
     1761253.823      483690.275     1761491.091      483772.885
#Sta/Elev= 29
       0  706.94     9.7  699.69    19.3  692.02      29  684.79    38.6  678.03
    48.3  671.44      58  664.85    67.6  658.22    77.3  651.56      87   644.9
    96.6  638.33   106.3  632.31     116  629.02     117  628.97   125.6   628.5
     132  629.03   135.3  629.31     145  631.19   154.6  632.94   164.3  633.29
   173.9  633.78   183.6  636.31   193.3  640.86   202.9  645.56   212.6  650.65
   222.2  656.08   231.9  661.64   241.6  667.27   251.2     673
#Mann= 3 , 0 , 0
       0      .1       0     117    .045       0   135.3      .1       0
Bank Sta=117,135.3
XS Rating Curve= 0 ,0
Exp/Cntr=0.3,0.1

Type RM Length L Ch R = 1 ,16175.5 ,249.6,277.1,303.8
XS GIS Cut Line= 2
      1761216.93      484165.535     1761514.239      484026.646
#Sta/Elev= 30
       0  710.44    19.3  702.05      29  697.34    38.6  692.23    48.3  686.63
    57.9  680.35    67.6  672.66    77.2  663.34    86.9  653.74    96.5  644.61
   106.2  636.17   115.8  629.82   124.8  627.37   125.5  627.18   135.1  627.11
   144.8   627.2   154.4  628.86   164.1  630.73   173.7  631.51   183.4   632.5
     193  633.97   202.7  635.82   212.3  638.25     222  641.96   231.6  647.34
   241.3  652.96   270.2  666.52   299.2  681.13   318.5  691.04   328.2  695.44
#Mann= 3 , 0 , 0
       0      .1       0   124.8    .045       0   144.8      .1       0
Bank Sta=124.8,144.8
XS Rating Curve= 0 ,0
Exp/Cntr=0.3,0.1