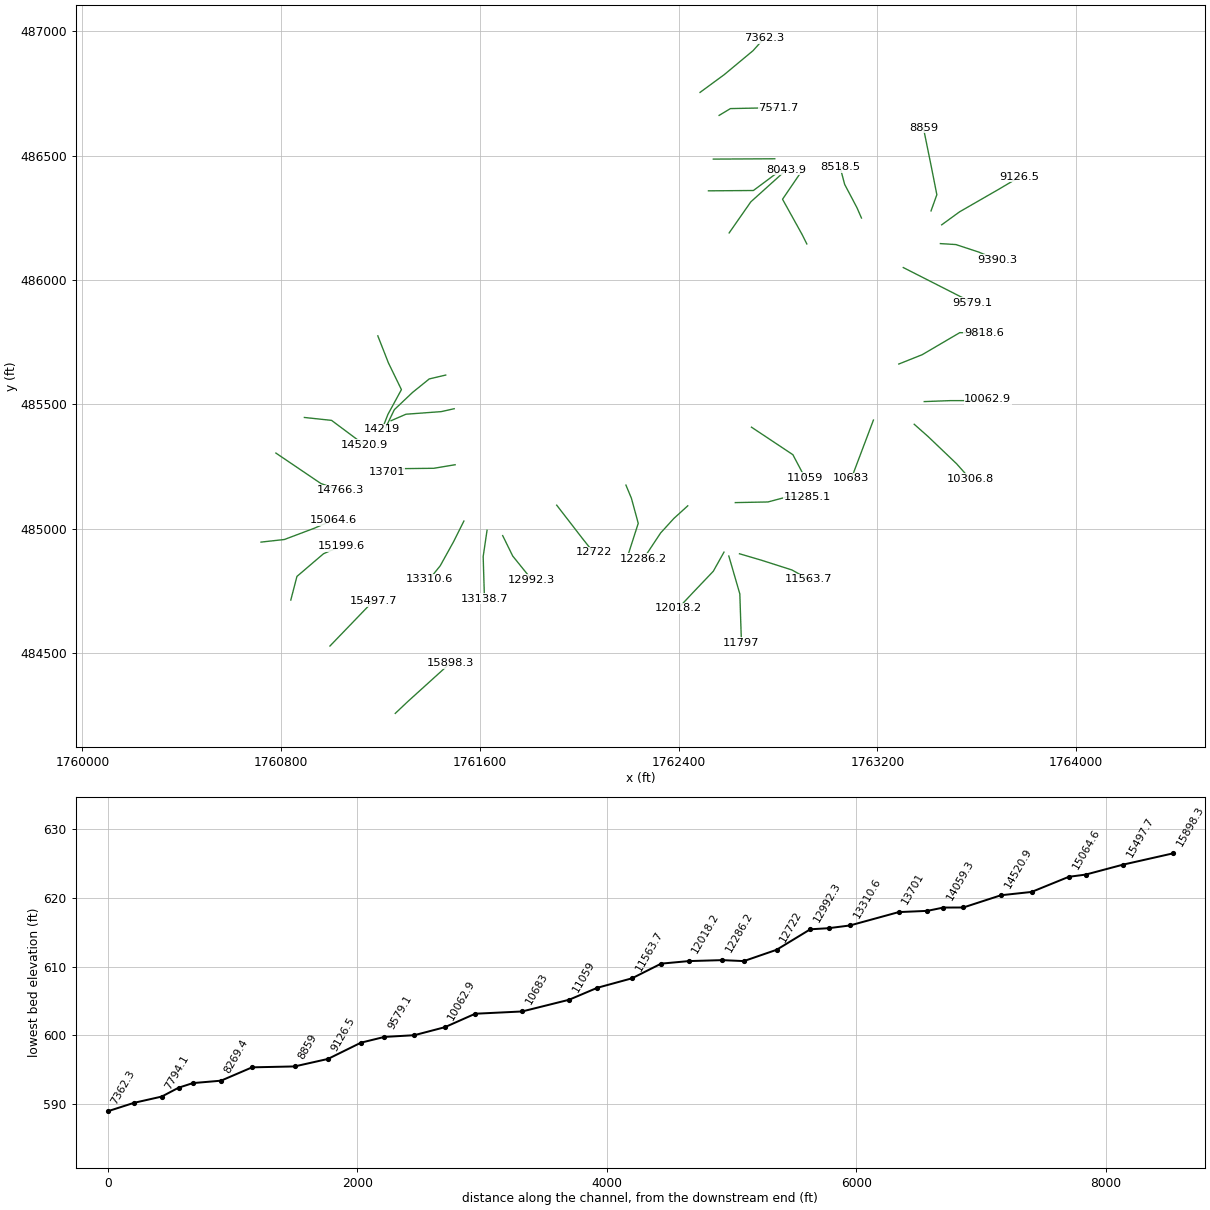
HEC-RAS study TRACEFORK.prj: TRACEFORK

--- TRACEFORK.g01 (geometry) --- (continued)

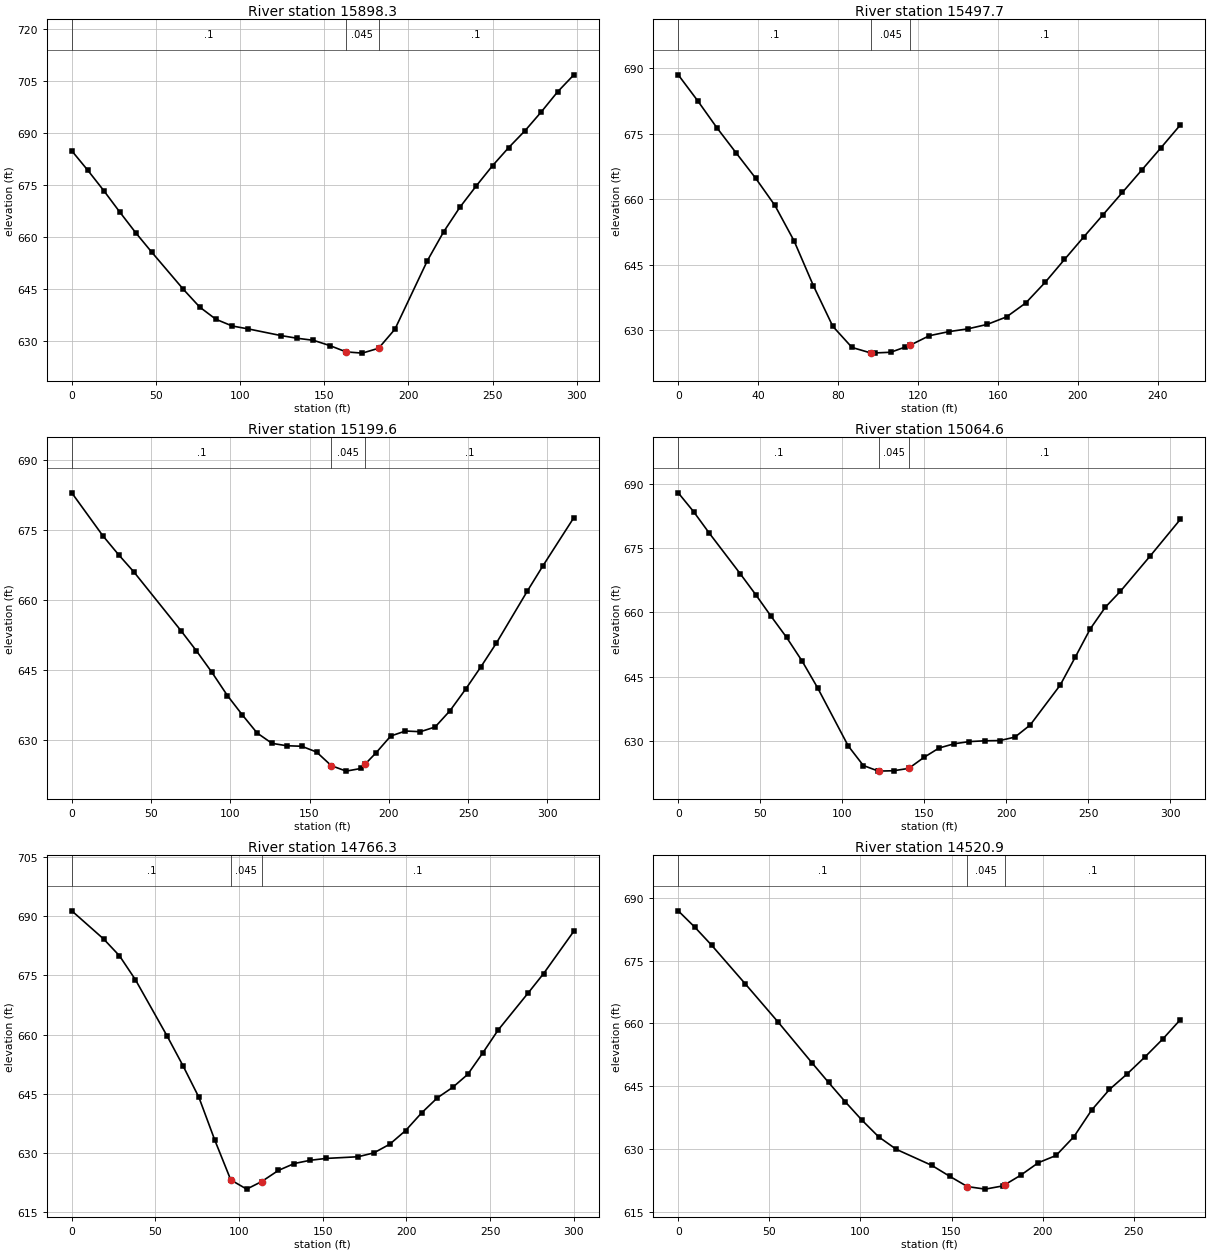
Type RM Length L Ch R = 1 ,15898.3 ,399.7,400.6,402
XS GIS Cut Line= 3
      1761259.32       484257.26     1761307.497      484302.833
     1761479.517      484458.504
#Sta/Elev= 29
       0  684.89     9.5  679.28      19   673.4    28.4  667.28    37.9  661.28
    47.4  655.68    66.3  644.88      76  639.76    85.6  636.24    95.3  634.29
     105  633.43   124.3  631.52     134  630.74   143.6  630.15   153.3  628.63
     163  626.81   172.6  626.45   182.3  627.86     192  633.36   211.3  653.18
     221  661.54   230.6  668.59   240.3  674.74     250   680.6   259.6  685.83
   269.3   690.7     279  696.16   288.6   701.9   298.3  706.84
#Mann= 3 , 0 , 0
       0      .1       0     163    .045       0   182.3      .1       0
Bank Sta=163,182.3
XS Rating Curve= 0 ,0
Exp/Cntr=0.3,0.1

Type RM Length L Ch R = 1 ,15497.7 ,300.1,298.1,295.7
XS GIS Cut Line= 2
       1760996.3      484528.093     1761170.779      484709.083
#Sta/Elev= 29
       0  688.47     9.7  682.56    19.3   676.4      29   670.6    38.7  664.86
    48.4   658.6      58  650.49    67.7  640.21    77.4  630.94      87  626.11
    96.7  624.81    98.4  624.85   106.4  625.01   113.4  626.16     116  626.59
   125.7  628.79   135.4  629.72     145  630.36   154.7  631.38   164.4   633.1
     174  636.28   183.7  640.99   193.4  646.23     203  651.36   212.7  656.46
   222.4  661.57   232.1  666.69   241.7  671.78   251.4     677
#Mann= 3 , 0 , 0
       0      .1       0    96.7    .045       0     116      .1       0
Bank Sta=96.7,116
XS Rating Curve= 0 ,0
Exp/Cntr=0.3,0.1

Type RM Length L Ch R = 1 ,15199.6 ,142.7,135,127
XS GIS Cut Line= 4
     1760838.747      484712.989     1760863.487      484808.041
     1760970.258      484899.187     1761041.872      484930.437
#Sta/Elev= 30
       0  682.89    19.6  673.71    29.5  669.67    39.3  665.92    68.8  653.44
    78.6  649.11    88.4   644.5    98.2  639.52   107.6  635.39   116.9  631.53
   126.3  629.31   135.6   628.8     145  628.69   154.4  627.46   163.7  624.54
   173.1  623.37   182.4  623.94     185  624.85   191.8  627.24   201.2  630.88
   210.5  631.95   219.9   631.8   229.2  632.81   238.6   636.3   248.4  640.88
   258.1  645.69   267.9  650.79   287.4   661.9   297.2  667.28   316.7  677.58
#Mann= 3 , 0 , 0
       0      .1       0   163.7    .045       0     185      .1       0
Bank Sta=163.7,185
XS Rating Curve= 0 ,0
Exp/Cntr=0.3,0.1

Type RM Length L Ch R = 1 ,15064.6 ,320.1,298.3,277
XS GIS Cut Line= 4
     1760718.956      484946.062     1760812.706      484956.479
       1760933.8      485002.052      1761009.32      485034.604
#Sta/Elev= 30
       0  687.86     9.4  683.46    18.9  678.48    37.7  669.06    47.2  664.16
    56.6   659.1      66  654.21    75.5  648.68    84.9  642.48   103.6  628.92
   112.8  624.36     122  623.05   122.6  623.06   131.3  623.14   140.5  623.69
   149.8  626.26     159  628.44   168.3  629.43   177.5  629.93   186.8  630.11
     196  630.17   205.2  630.97   214.5  633.79   232.8  643.08     242  649.61
   251.1  656.17   260.3  661.22   269.4  664.89   287.7  673.18     306  681.67
#Mann= 3 , 0 , 0
       0      .1       0   122.6    .045       0   140.5      .1       0
Bank Sta=122.6,140.5
XS Rating Curve= 0 ,0
Exp/Cntr=0.3,0.1

Type RM Length L Ch R = 1 ,14766.3 ,246.4,245.4,244.5
XS GIS Cut Line= 3
     1760778.852      485304.135     1760959.841      485181.739
     1761036.664      485154.395
#Sta/Elev= 28
       0  691.36      19  684.24    28.5  679.97      38  673.93      57  659.62
    66.5  652.08      76  644.07    85.5  633.22      95  623.19   104.5  620.85
   113.4  622.75   123.5   625.6     133  627.34   142.5  628.16     152  628.63
     171  629.05   180.5  630.03     190  632.23   199.5   635.7     209  640.15
   218.5     644   227.6  646.63   236.6  649.93   245.7  655.43   254.7  661.12
   272.8   670.6   281.9  675.45     300   686.2
#Mann= 3 , 0 , 0
       0      .1       0      95    .045       0   113.4      .1       0
Bank Sta=95,113.4
XS Rating Curve= 0 ,0
Exp/Cntr=0.3,0.1

Type RM Length L Ch R = 1 ,14520.9 ,312.6,301.9,290.8
XS GIS Cut Line= 3
     1760893.435      485447.364      1761002.81      485435.645
     1761135.622      485336.687
#Sta/Elev= 27
       0  686.87     9.2  682.92    18.3  678.67    36.7  669.47      55   660.2
    73.3  650.61    82.5  645.87    91.7  641.23   100.8  636.87     110  632.87
   119.7  629.88   139.2  626.04     149  623.44   158.7  620.98   168.5  620.37
   178.2  621.14   179.4  621.45   187.9  623.67   197.7  626.69   207.4  628.41
   217.2   632.9   226.9  639.24   236.7  644.18   246.4  647.89   256.1  651.91
   265.9   656.2   275.6  660.85
#Mann= 3 , 0 , 0
       0      .1       0   158.7    .045       0   179.4      .1       0
Bank Sta=158.7,179.4
XS Rating Curve= 0 ,0
Exp/Cntr=0.3,0.1

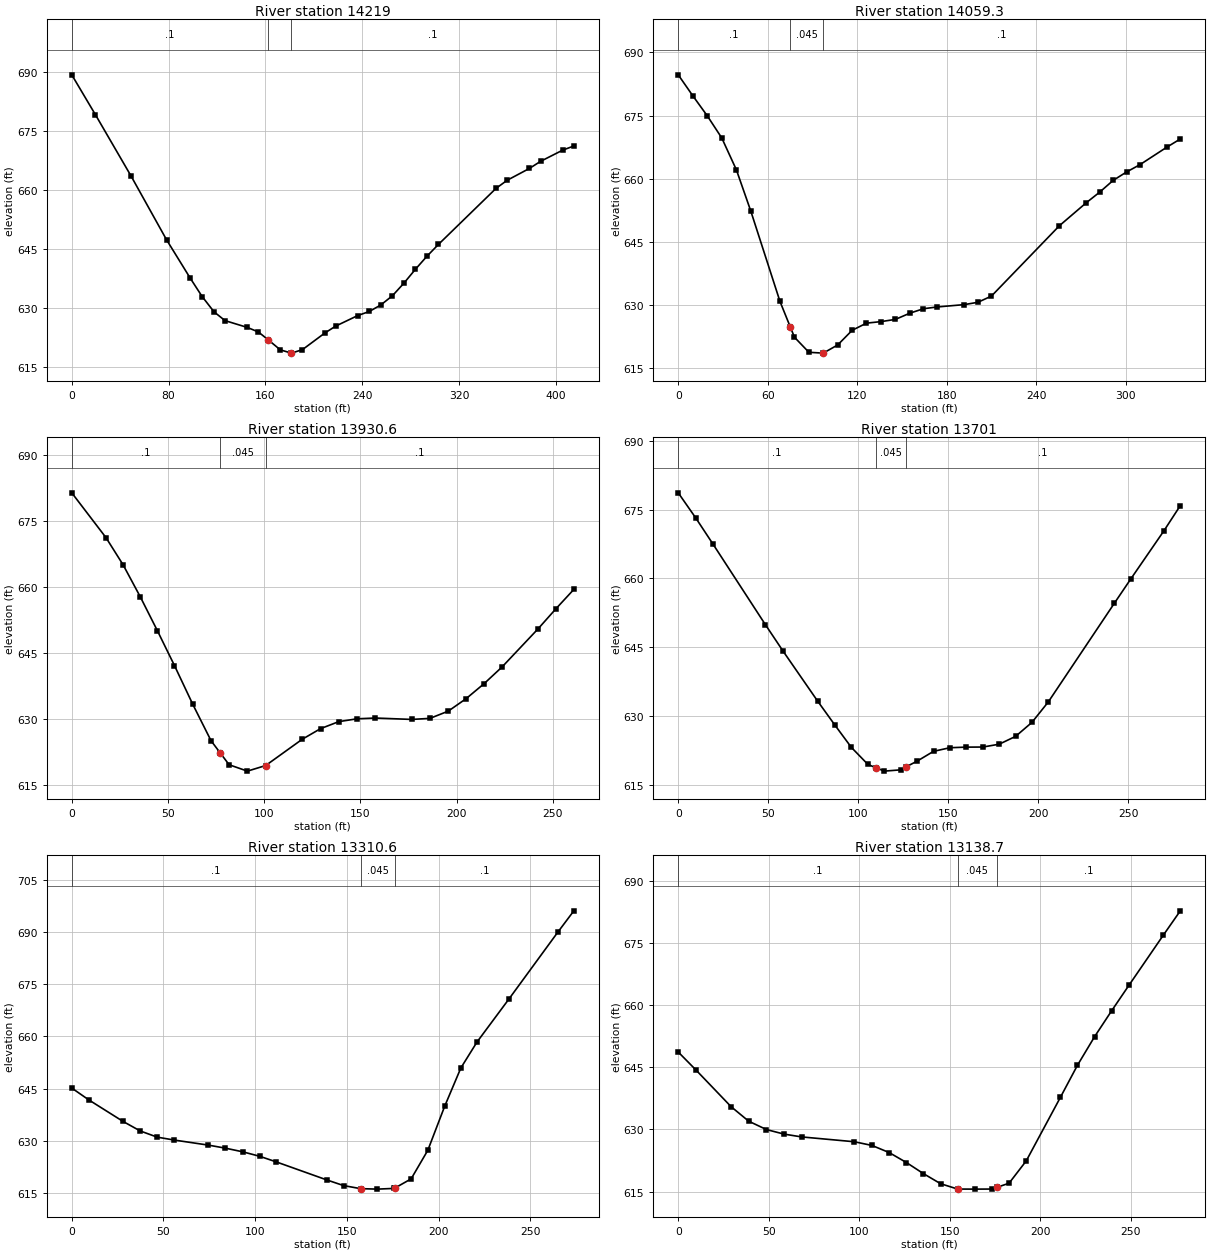
Type RM Length L Ch R = 1 ,14219   ,194.2,159.7,128.7
XS GIS Cut Line= 5
     1761189.008      485775.489     1761231.977      485666.114
      1761284.06      485559.343     1761229.372      485459.083
     1761205.935      485399.187
#Sta/Elev= 30
       0  689.29    19.6  679.13      49  663.57    78.3  647.39    97.9  637.62
   107.7  632.97   117.5  629.09   126.6  626.85   144.9  625.13   154.1  623.98
   162.3  621.97   172.3  619.42   181.5  618.59   190.6  619.48   208.9  623.66
     218  625.45   236.3  628.14   245.8  629.17   255.3  630.82   264.9  633.16
   274.4  636.36   283.9  639.89   293.4  643.19   302.9   646.2   350.5  660.44
   359.7   662.5   378.1  665.51   387.3  667.31   405.6  670.16   414.8  671.21
#Mann= 3 , 0 , 0
       0      .1       0   162.3    .045       0   181.5      .1       0
Bank Sta=162.3,181.5
XS Rating Curve= 0 ,0
Exp/Cntr=0.3,0.1

Type RM Length L Ch R = 1 ,14059.3 ,138.6,128.7,114.9
XS GIS Cut Line= 5
     1761462.445      485617.937     1761396.039      485602.312
     1761328.331      485547.624     1761255.414      485478.614
     1761220.258      485405.697
#Sta/Elev= 30
       0  684.66     9.8  679.67    19.5  674.91    29.2  669.66      39  662.09
    48.7  652.25    68.2  630.86    75.1  624.81    77.9  622.36    87.6  618.78
    97.2  618.58   106.9  620.52   116.6     624   126.2   625.7   135.9  626.06
   145.6  626.59   155.3  628.07   164.4  629.12   173.5  629.54   191.8   630.1
   200.9  630.65     210  632.13   255.6  648.85   273.6   654.3   282.6  656.82
   291.6   659.6   300.6   661.6   309.6  663.34   327.6  667.49   336.6  669.43
#Mann= 3 , 0 , 0
       0      .1       0    75.1    .045       0    97.2      .1       0
Bank Sta=75.1,97.2
XS Rating Curve= 0 ,0
Exp/Cntr=0.3,0.1

Type RM Length L Ch R = 1 ,13930.6 ,230.9,229.5,228.1
XS GIS Cut Line= 4
       1761496.3       485482.52     1761444.216      485470.802
     1761302.289      485460.385     1761242.393      485434.343
#Sta/Elev= 26
       0  681.35    17.8  671.16    26.7  664.98    35.6  657.73    44.5  650.02
    53.4  642.08    62.9  633.29    72.4  625.01    77.3  622.16    81.8  619.55
    91.3   618.1   100.8  619.37   119.8  625.34   129.3  627.75   138.8  629.35
   148.3  629.99   157.8  630.17   176.7  629.85   186.2  630.09   195.7  631.73
     205  634.57   214.4     638   223.7  641.78   242.4  650.44   251.7  655.01
     261   659.4
#Mann= 3 , 0 , 0
       0      .1       0    77.3    .045       0   100.8      .1       0
Bank Sta=77.3,100.8
XS Rating Curve= 0 ,0
Exp/Cntr=0.3,0.1

Type RM Length L Ch R = 1 ,13701   ,366.1,390.4,413.9
XS GIS Cut Line= 4
     1761500.206       485257.26     1761414.268      485242.937
     1761295.779      485241.635     1761224.164       485226.01
#Sta/Elev= 26
       0  678.69     9.7  673.22    19.4  667.44    48.4  649.91    58.1   644.2
    77.4  633.23    87.1  627.93    96.2  623.09   105.4  619.37   109.7  618.68
   114.5  617.92   123.6   618.2  126.48  618.84   132.7   620.1   141.8  622.24
   150.9  623.03     160  623.16   169.2  623.18   178.3   623.8   187.4  625.51
   196.5  628.57   205.6  633.05   242.3   654.6   251.4  659.89   269.8   670.4
   278.9   675.9
#Mann= 3 , 0 , 0
       0      .1       0   109.7    .045       0  126.48      .1       0
Bank Sta=109.7,126.48
XS Rating Curve= 0 ,0
Exp/Cntr=0.3,0.1

Type RM Length L Ch R = 1 ,13310.6 ,159.9,171.9,184.3
XS GIS Cut Line= 4
     1761535.362      485030.697     1761493.695      484947.364
      1761440.31       484851.01     1761396.039      484796.322
#Sta/Elev= 25
       0  645.13     9.3  641.71      28  635.49    37.3  632.76    46.6  630.97
    55.9  630.13    74.5  628.67    83.8  627.79    93.2  626.74   102.4  625.46
   111.5  623.83   139.1  618.62   148.2     617   157.4  616.12   166.6  615.98
   175.8  616.19   176.2  616.31     185  618.94   194.1  627.19   203.3  639.89
   212.1  650.92   220.9   658.4   238.5  670.94   264.9  690.04   273.7  696.24
#Mann= 3 , 0 , 0
       0      .1       0   157.4    .045       0   176.2      .1       0
Bank Sta=157.4,176.2
XS Rating Curve= 0 ,0
Exp/Cntr=0.3,0.1

Type RM Length L Ch R = 1 ,13138.7 ,131.4,146.4,161.2
XS GIS Cut Line= 3
     1761628.678      484993.805     1761613.053      484887.902
     1761618.261      484717.763
#Sta/Elev= 26
       0  648.69     9.7  644.39    29.2  635.49    38.9  631.99    48.7  629.97
    58.4  628.87    68.1  628.19    97.3  627.02     107  626.13   116.5  624.41
     126  622.01   135.4  619.33   144.9  616.89   154.3   615.6   163.8  615.58
   173.2   615.6   175.9     616   182.7     617   192.2   622.4   211.1  637.77
   220.5   645.5     230  652.43   239.4  658.67   248.9  664.79   267.8  676.84
   277.3  682.79
#Mann= 3 , 0 , 0
       0      .1       0   154.3    .045       0   175.9      .1       0
Bank Sta=154.3,175.9
XS Rating Curve= 0 ,0
Exp/Cntr=0.3,0.1

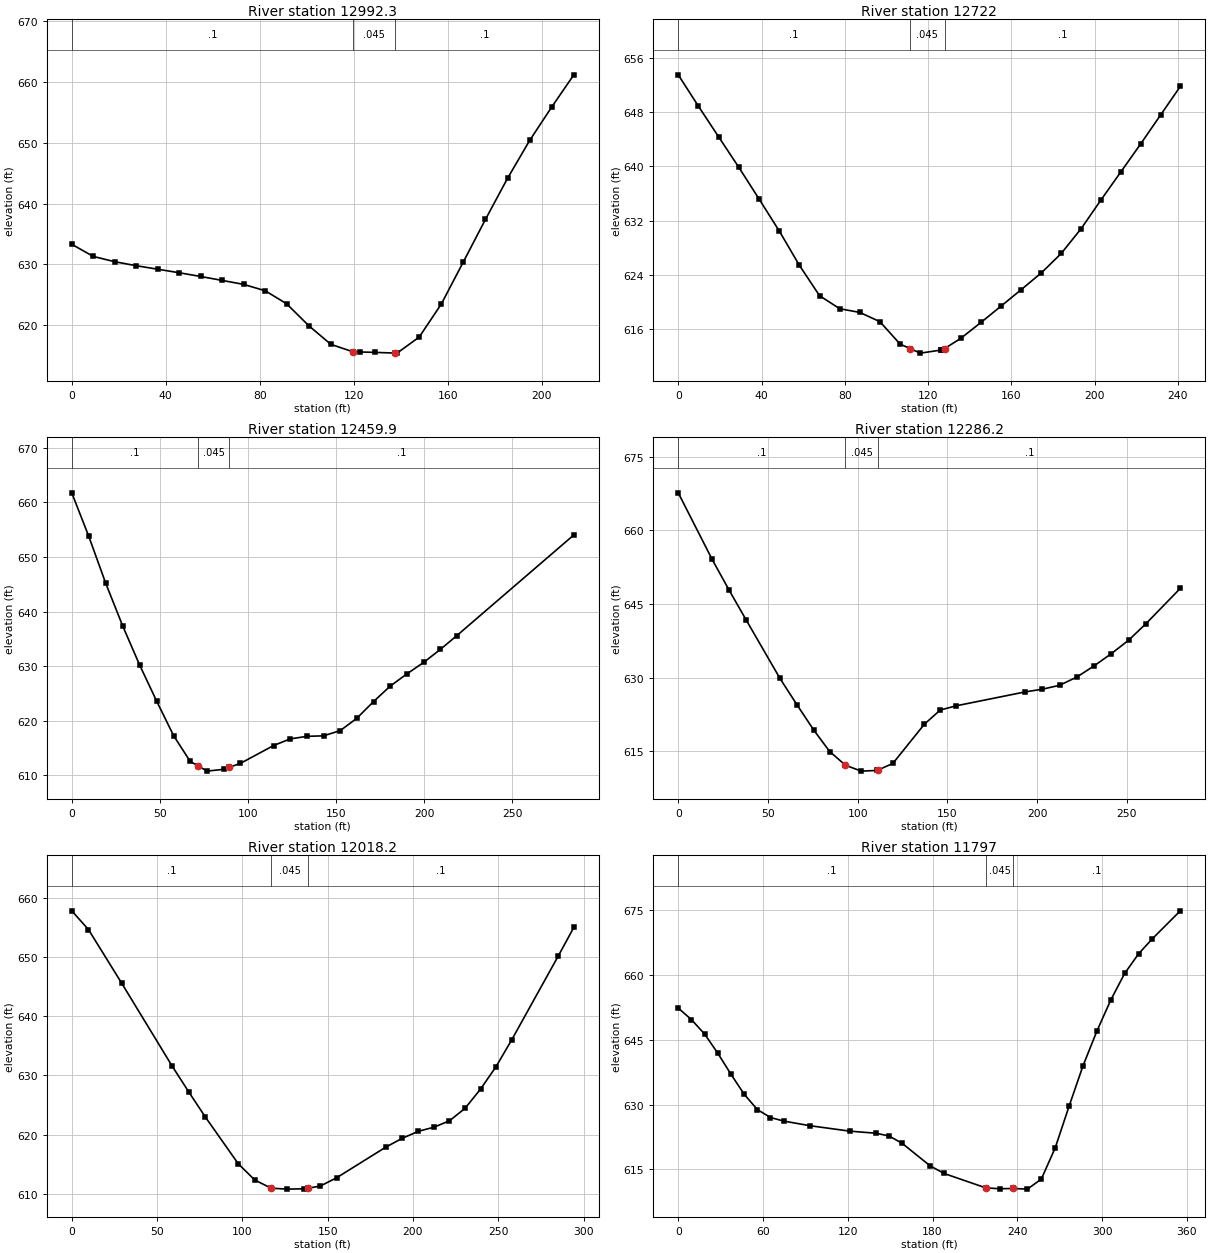
Type RM Length L Ch R = 1 ,12992.3 ,270.8,270.3,269.3
XS GIS Cut Line= 3
     1761691.612      484972.104     1761731.977      484890.072
       1761808.8       484795.02
#Sta/Elev= 26
       0  633.31     9.1  631.32    18.3  630.44    27.4  629.79    36.6  629.21
    45.7  628.63    54.8  628.02      64  627.37    73.1  626.72    82.3  625.67
    91.4  623.53   100.8  619.94   110.2  616.87   119.6  615.64   122.7  615.61
     129  615.54   137.7  615.43   138.4  615.42   147.8  618.06   157.2  623.48
   166.6  630.42     176   637.4   185.4  644.16   194.8  650.37   204.2  655.88
   213.6  661.16
#Mann= 3 , 0 , 0
       0      .1       0   119.6    .045       0   137.7      .1       0
Bank Sta=119.6,137.7
XS Rating Curve= 0 ,0
Exp/Cntr=0.3,0.1

Type RM Length L Ch R = 1 ,12722   ,271,262.1,253.5
XS GIS Cut Line= 3
      1761909.06      485094.499     1762015.831      484956.479
     1762057.497      484904.395
#Sta/Elev= 29
       0  653.51     9.7  648.88    19.4  644.36    29.1  639.86    38.8   635.2
    48.5  630.48    58.2   625.4    67.9  620.91    77.6  618.99    87.2  618.45
    96.9  617.08   106.6  613.77   111.4  613.11   116.3  612.44     126  612.88
   126.4  612.95  127.99  613.12   135.7  614.61   145.4  616.96   155.1  619.38
   164.8  621.82   174.5   624.3     184  627.15   193.6  630.83   203.1  635.05
   212.6  639.17   222.1  643.29   231.7  647.57   241.2   651.8
#Mann= 3 , 0 , 0
       0      .1       0   111.4    .045       0  127.99      .1       0
Bank Sta=111.4,127.99
XS Rating Curve= 0 ,0
Exp/Cntr=0.3,0.1

Type RM Length L Ch R = 1 ,12459.9 ,196.6,173.8,150.9
XS GIS Cut Line= 4
     1762187.706      485175.229     1762209.841      485121.843
     1762237.185      485021.583     1762199.425      484904.395
#Sta/Elev= 26
       0  661.75     9.6  653.82    19.3  645.16    28.9  637.37    38.5  630.22
    48.2  623.58    57.8  617.28    67.2  612.57   71.74  611.76    76.7   610.8
    86.1  611.13    89.1  611.47    95.6  612.21   114.5  615.49   123.9   616.7
   133.4  617.17   142.8  617.26   152.3  618.22   161.7  620.48   171.2  623.54
   180.7  626.38   190.1   628.6   199.6   630.7   209.1  633.09   218.5  635.63
   284.8  654.04
#Mann= 3 , 0 , 0
       0      .1       0   71.74    .045       0    89.1      .1       0
Bank Sta=71.74,89.1
XS Rating Curve= 0 ,0
Exp/Cntr=0.3,0.1

Type RM Length L Ch R = 1 ,12286.2 ,268.4,267.9,268
XS GIS Cut Line= 4
     1762436.404      485091.895     1762380.414      485041.114
     1762327.029       484982.52     1762258.018      484878.354
#Sta/Elev= 25
       0  667.68    18.9   654.1    28.4  647.81    37.8  641.79    56.7  629.84
    66.1   624.5    75.6  619.27    84.4  614.94    93.2  612.14     102  610.94
   110.8  611.08   111.5  611.19   119.6  612.51   137.2  620.52     146  623.39
   154.8  624.25   193.3  627.09   202.9  627.64   212.5  628.44   222.1  630.11
   231.8  632.41   241.4   634.9     251  637.63   260.6  640.98   279.8   648.2
#Mann= 3 , 0 , 0
       0      .1       0    93.2    .045       0   111.5      .1       0
Bank Sta=93.2,111.5
XS Rating Curve= 0 ,0
Exp/Cntr=0.3,0.1

Type RM Length L Ch R = 1 ,12018.2 ,205.1,221.2,238.9
XS GIS Cut Line= 4
     1762582.237      484905.697     1762539.268      484828.874
     1762459.841      484745.541     1762397.341      484679.135
#Sta/Elev= 25
       0   657.8     9.8  654.63    29.3  645.56    58.7  631.64    68.5  627.25
    78.2  623.02    97.6  615.08   107.2  612.36   116.8  610.96   126.4   610.8
     136  610.86   138.6  610.98   145.6  611.31   155.2  612.71     184  617.88
   193.6  619.37   203.2  620.57   212.3  621.26   221.4  622.34   230.5  624.44
   239.6  627.69   248.7  631.49   257.9  636.02   285.2  650.19   294.3  655.01
#Mann= 3 , 0 , 0
       0      .1       0   116.8    .045       0   138.6      .1       0
Bank Sta=116.8,138.6
XS Rating Curve= 0 ,0
Exp/Cntr=0.3,0.1

Type RM Length L Ch R = 1 ,11797   ,202.7,233.3,261.8
XS GIS Cut Line= 3
     1762601.768      484890.072     1762646.039      484737.729
      1762652.55      484541.114
#Sta/Elev= 30
       0  652.32     9.3  649.66    18.7   646.3      28  641.88    37.3  637.02
    46.7  632.37      56  628.84    65.3     627    74.7  626.17    93.3   625.1
   121.3  623.85     140  623.36   149.3  622.72   158.6     621   178.3  615.82
   188.2  614.05   217.7  610.72   227.5  610.52   237.3  610.58   247.2  610.43
     257  612.75   266.8  619.94   276.7  629.65   286.5  638.95   296.4  647.04
   306.2   654.2     316  660.33   325.9  664.89   335.7  668.39   355.4  674.82
#Mann= 3 , 0 , 0
       0      .1       0   217.7    .045       0   237.3      .1       0
Bank Sta=217.7,237.3
XS Rating Curve= 0 ,0
Exp/Cntr=0.3,0.1

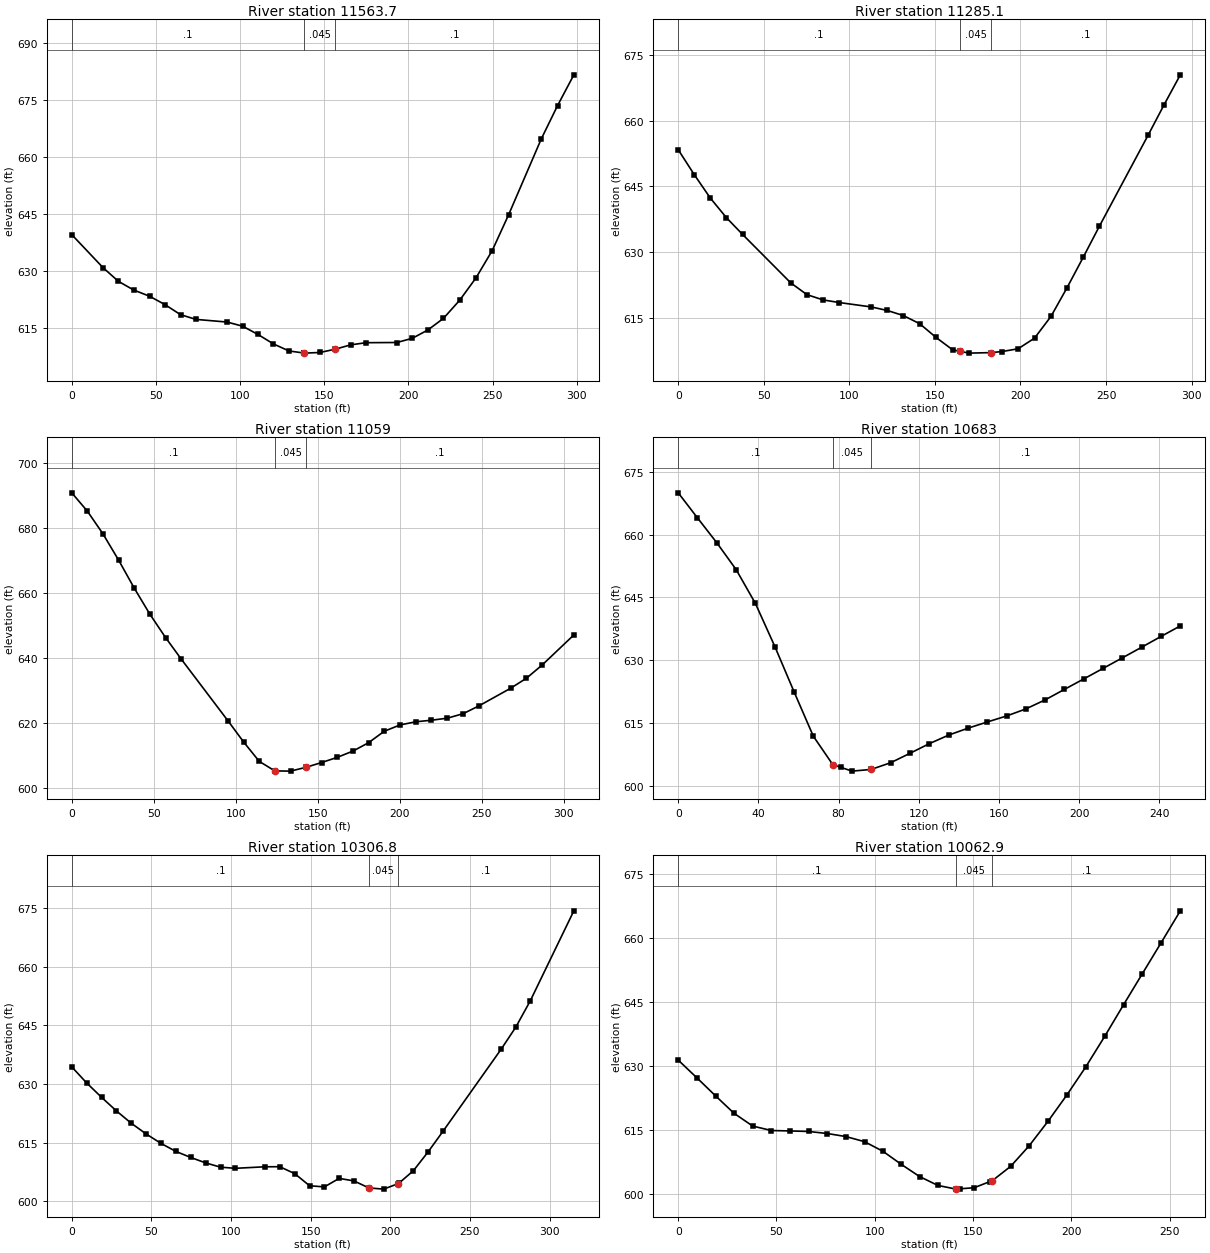
Type RM Length L Ch R = 1 ,11563.7 ,265.3,278.6,291.1
XS GIS Cut Line= 4
     1762644.737      484899.187     1762733.279      484873.145
     1762855.675      484834.083     1762923.383      484796.322
#Sta/Elev= 30
       0  639.53    18.5  630.86    27.7  627.22    36.9  624.91    46.2   623.3
    55.4  621.08    64.6  618.44    73.8  617.19    92.3  616.49   101.5   615.4
   110.6  613.23   119.8  610.73     129  608.88   137.8  608.33   138.2   608.3
   147.4  608.47   156.5  609.33   165.7  610.48   174.9  611.05   193.2   611.1
   202.4  612.22   211.6  614.41   220.8  617.45   230.5  622.25   240.2  628.16
   249.8  635.33   259.5  644.72   278.9  664.71   288.6  673.52   298.3  681.65
#Mann= 3 , 0 , 0
       0      .1       0   137.8    .045       0   156.5      .1       0
Bank Sta=137.8,156.5
XS Rating Curve= 0 ,0
Exp/Cntr=0.3,0.1

Type RM Length L Ch R = 1 ,11285.1 ,245.5,226.2,207
XS GIS Cut Line= 4
      1762627.81      485104.916      1762759.32       485107.52
     1762842.654      485129.656     1762918.175      485125.749
#Sta/Elev= 28
       0  653.38     9.4  647.67    18.8  642.31    28.2  637.84    37.6  634.03
    65.8  622.95    75.2  620.28    84.6  619.08      94  618.48   112.8  617.47
   122.1  616.67   131.5  615.51   141.1  613.64   150.7  610.49   160.3  607.69
   164.6  607.35   169.9  606.92  182.82  607.04     189  607.27   198.6  607.91
   208.2  610.34   217.8   615.3   227.2  621.85   236.7  628.84   246.1   635.9
   274.5  656.64   283.9  663.64   293.4  670.49
#Mann= 3 , 0 , 0
       0      .1       0   164.6    .045       0  182.82      .1       0
Bank Sta=164.6,182.82
XS Rating Curve= 0 ,0
Exp/Cntr=0.3,0.1

Type RM Length L Ch R = 1 ,11059   ,406.7,376,345.2
XS GIS Cut Line= 3
     1762692.914      485408.302     1762859.581      485297.624
      1762909.06      485203.874
#Sta/Elev= 29
       0  690.74     9.5  685.11      19  678.14    28.6  670.02    38.1  661.43
    47.6  653.44    57.2  646.23    66.7  639.65    95.3   620.6   104.8  614.13
   114.3  608.18   123.8  605.25   133.4  605.18   142.9  606.37   152.4  607.83
     162  609.44   171.5  611.36     181  613.93   190.5  617.44   200.1  619.37
   209.7  620.35   219.3  620.83     229  621.46   238.6  622.84   248.2  625.23
   267.5  630.64   277.2  633.74   286.8  637.81   306.1  647.05
#Mann= 3 , 0 , 0
       0      .1       0   123.8    .045       0   142.9      .1       0
Bank Sta=123.8,142.9
XS Rating Curve= 0 ,0
Exp/Cntr=0.3,0.1

Type RM Length L Ch R = 1 ,10683   ,349.3,376.1,402.6
XS GIS Cut Line= 2
       1763183.8      485436.947     1763095.258      485202.572
#Sta/Elev= 28
       0  669.96     9.6  663.97    19.3     658    28.9  651.61    38.5  643.54
    48.2  633.25    57.8  622.42    67.4  611.82    77.1  605.04    81.2  604.37
    86.7  603.48    96.2  603.88     106  605.49   115.6  607.73   125.3  610.05
   134.9  612.08   144.5  613.73   154.2  615.22   163.8  616.65   173.4  618.33
   183.1  620.51   192.7  623.01   202.4  625.52     212  628.03   221.6  630.54
   231.3   633.1   240.9  635.66   250.5  638.17
#Mann= 3 , 0 , 0
       0      .1       0    77.1    .045       0    96.2      .1       0
Bank Sta=77.1,96.2
XS Rating Curve= 0 ,0
Exp/Cntr=0.3,0.1

Type RM Length L Ch R = 1 ,10306.8 ,226.7,243.9,261.2
XS GIS Cut Line= 4
     1763347.862       485420.02     1763403.852      485370.541
     1763518.435      485261.166     1763573.122      485199.968
#Sta/Elev= 30
       0  634.39     9.3  630.31    18.7  626.61      28  623.15    37.4  619.97
    46.7  617.25      56  614.84    65.4  612.78    74.7  611.24      84  609.86
    93.4  608.76   102.7  608.47   121.3  608.86   130.6  608.88     140   607.1
   149.3  604.01   158.6  603.72   167.9   605.9   177.2  605.24   186.5  603.46
   195.8  603.15   204.7  604.52   205.2   604.6   214.5  607.87   223.8  612.72
   233.1  617.96   269.6  638.93   278.7  644.51   287.8  651.23   315.2  674.27
#Mann= 3 , 0 , 0
       0      .1       0   186.5    .045       0   204.7      .1       0
Bank Sta=186.5,204.7
XS Rating Curve= 0 ,0
Exp/Cntr=0.3,0.1

Type RM Length L Ch R = 1 ,10062.9 ,232.2,244.3,256.2
XS GIS Cut Line= 4
     1763388.227      485511.166     1763492.393      485515.072
     1763566.612      485515.072     1763643.435      485520.281
#Sta/Elev= 30
       0  631.39     9.5  627.24      19  623.02    28.4  618.94    37.9  615.95
    47.4  614.91    56.9  614.81    66.3  614.69    75.8  614.21    85.3   613.5
    94.8   612.3   104.2  610.04   113.5  606.99   122.8  604.14   132.1  602.06
   141.4  601.19   143.5  601.27   150.6  601.52   158.5  602.94   159.9  603.19
   169.2  606.54   178.5  611.29   188.1  617.03   197.7  623.18   207.3  629.74
     217  636.93   226.6  644.34   236.2  651.64   245.8  658.92   255.5  666.34
#Mann= 3 , 0 , 0
       0      .1       0   141.4    .045       0   159.9      .1       0
Bank Sta=141.4,159.9
XS Rating Curve= 0 ,0
Exp/Cntr=0.3,0.1

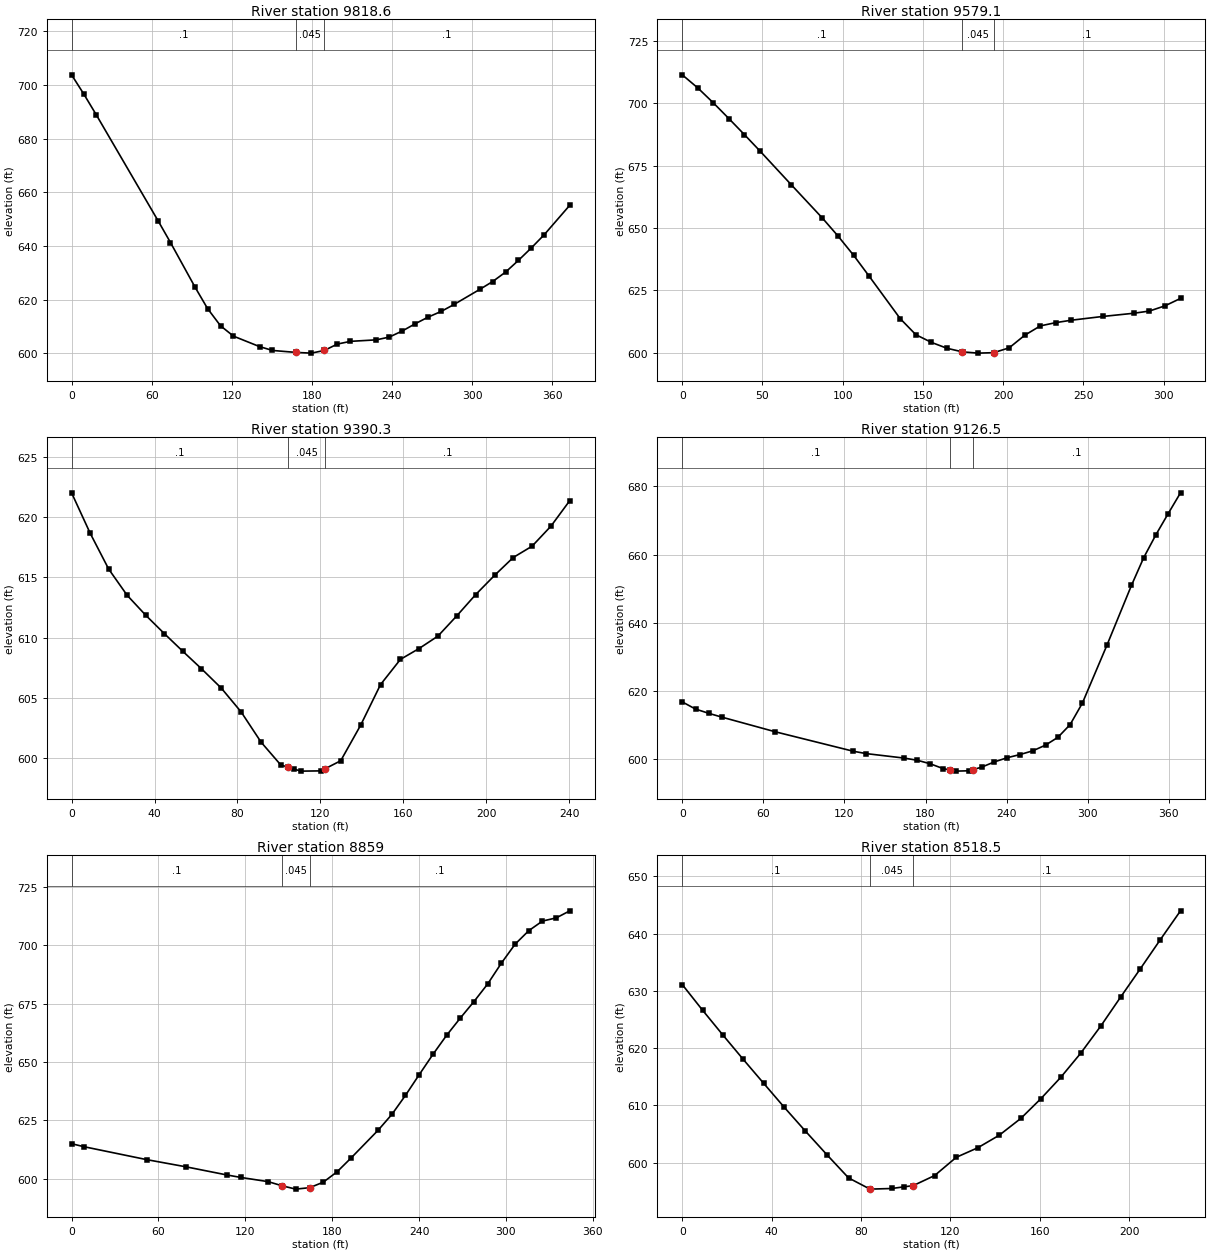
Type RM Length L Ch R = 1 ,9818.6  ,262.1,239.5,216.8
XS GIS Cut Line= 4
     1763285.796      485662.208     1763380.414      485699.968
     1763531.456       485788.51      1763627.81      485785.906
#Sta/Elev= 30
       0  703.77     9.3  696.49    18.5  688.87    64.8  649.37    74.1  641.26
    92.6  624.54   101.9  616.63   111.6  610.22   121.3  606.36   140.8  602.47
   150.5  601.03   168.5  600.28   179.7  600.03   189.4  601.04   199.1   603.4
   208.9  604.42   228.3  604.98     238  606.01   247.8  608.29   257.5  610.99
   267.2  613.47     277   615.6   286.6  618.18   305.9  623.81   315.5  626.72
   325.2  630.25   334.8  634.61   344.4  639.22   354.1  644.16   373.3  655.17
#Mann= 3 , 0 , 0
       0      .1       0   168.5    .045       0   189.4      .1       0
Bank Sta=168.5,189.4
XS Rating Curve= 0 ,0
Exp/Cntr=0.3,0.1

Type RM Length L Ch R = 1 ,9579.1  ,184.1,188.8,194.4
XS GIS Cut Line= 2
     1763304.025      486050.229     1763580.935      485909.604
#Sta/Elev= 29
       0   711.5     9.7  706.23    19.4  700.23    29.1  693.91    38.8  687.46
    48.5  680.89    67.9  667.41    87.4  653.97      97  646.86   106.8  639.07
   116.5  630.67   135.9   613.6   145.6  607.19   155.3   604.1     165  601.73
   174.1  600.37   174.7  600.28   184.4  599.78   194.1  599.96   203.8   601.9
   213.5  606.96   223.2  610.71   232.9  612.03   242.6     613     262  614.49
   281.5  615.79   291.2  616.67   300.9  618.76   310.6  621.74
#Mann= 3 , 0 , 0
       0      .1       0   174.1    .045       0   194.1      .1       0
Bank Sta=174.1,194.1
XS Rating Curve= 0 ,0
Exp/Cntr=0.3,0.1

Type RM Length L Ch R = 1 ,9390.3  ,245.7,263.9,280.9
XS GIS Cut Line= 4
     1763453.331      486146.583     1763515.831      486142.677
     1763606.977      486112.729     1763682.497      486081.479
#Sta/Elev= 30
       0     622       9  618.64    17.9  615.68    26.8  613.51    35.8  611.85
    44.7  610.34    53.7  608.86    62.6  607.43    72.2  605.82    81.8  603.84
    91.4  601.34     101  599.43   104.3  599.29   107.3  599.11   110.6  598.94
   120.2  598.96   122.3  599.14   129.8   599.8   139.4  602.74     149  606.11
   158.6   608.2   167.6   609.1   176.7  610.13   185.8  611.81   194.9  613.57
     204  615.16     213  616.64   222.1  617.58   231.2  619.24   240.3  621.36
#Mann= 3 , 0 , 0
       0      .1       0   104.3    .045       0   122.3      .1       0
Bank Sta=104.3,122.3
XS Rating Curve= 0 ,0
Exp/Cntr=0.3,0.1

Type RM Length L Ch R = 1 ,9126.5  ,239.2,267.5,295.5
XS GIS Cut Line= 4
     1763458.539      486222.104     1763530.154      486274.187
     1763686.404      486364.031     1763772.341      486414.812
#Sta/Elev= 30
       0  616.87     9.8  614.77    19.7  613.51    29.5  612.38    68.9   608.1
   126.5  602.41     136  601.72   164.4  600.39   173.9  599.76   183.4  598.74
   192.9  597.33  197.98  596.93   202.4  596.58   211.9  596.68   214.8     597
   221.4  597.73   230.8  599.27   240.3   600.5   249.8  601.43   259.3  602.53
   268.8  604.21   277.9  606.49   286.9  610.19     296  616.51   314.2  633.51
   332.3     651   341.4  659.16   350.5  665.92   359.5  672.06   368.6  678.14
#Mann= 3 , 0 , 0
       0      .1       0  197.98    .045       0   214.8      .1       0
Bank Sta=197.98,214.8
XS Rating Curve= 0 ,0
Exp/Cntr=0.3,0.1

Type RM Length L Ch R = 1 ,8859    ,333.7,340.4,346.9
XS GIS Cut Line= 4
      1763415.57      486278.093     1763439.008      486343.197
     1763416.872      486455.177     1763384.754      486612.729
#Sta/Elev= 28
       0  614.96     8.6  613.67    51.9  608.13    78.7  605.09   107.2  601.57
   116.8  600.51   135.8  598.69   145.3  596.94   154.8  595.49   164.4  596.11
   173.8  598.46   183.3  602.88   192.8   608.7   211.7  620.74   221.2  627.52
   230.6  635.69   240.1  644.57   249.6  653.29     259  661.42   268.5  668.85
   277.9   675.9   287.4  683.47   296.8  692.34   306.3  700.49   315.8  706.31
   325.2   710.4   334.7  711.76   344.1  714.79
#Mann= 3 , 0 , 0
       0      .1       0   145.3    .045       0   164.4      .1       0
Bank Sta=145.3,164.4
XS Rating Curve= 0 ,0
Exp/Cntr=0.3,0.1

Type RM Length L Ch R = 1 ,8518.5  ,248.7,249.2,249.5
XS GIS Cut Line= 4
     1763135.622      486249.447     1763117.393      486291.114
     1763067.914      486384.864     1763049.685      486453.874
#Sta/Elev= 26
       0  631.08     9.1   626.6    18.2  622.26    27.3  618.01    36.4  613.85
    45.5  609.71    55.1  605.49    64.8  601.33    74.4  597.32      84  595.36
    93.7  595.47      99  595.75   103.3  595.97   112.9  597.73   122.6  600.92
   132.2  602.58   141.8  604.77   151.5  607.72   160.4  611.14   169.3  614.87
   178.2  619.07   187.2  623.82   196.1  628.89     205  633.88   213.9  638.94
   222.9  643.96
#Mann= 3 , 0 , 0
       0      .1       0      84    .045       0   103.3      .1       0
Bank Sta=84,103.3
XS Rating Curve= 0 ,0
Exp/Cntr=0.3,0.1

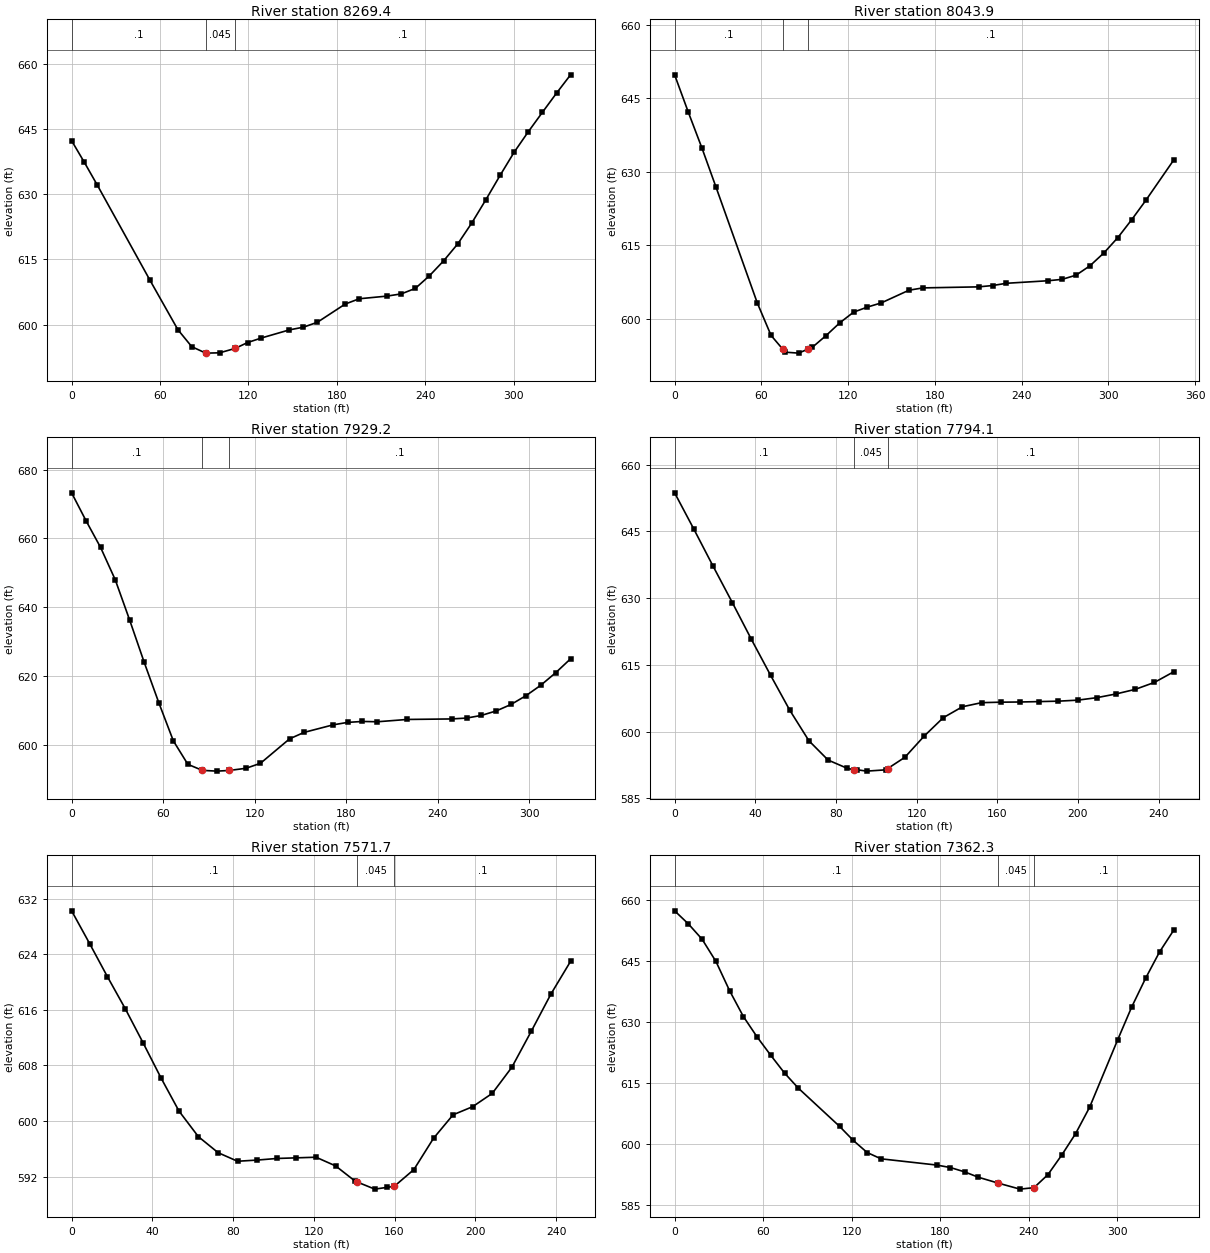
Type RM Length L Ch R = 1 ,8269.4  ,250.6,225.5,200.1
XS GIS Cut Line= 4
      1762915.57      486145.281     1762896.039      486184.343
     1762817.914      486324.968     1762893.435      486435.645
#Sta/Elev= 30
       0  642.35     8.7  637.33    17.5  632.08    53.1  610.25    72.1  598.82
    81.5  594.91      91  593.42   100.4  593.49   110.9   594.5   119.4  595.86
   128.8  596.91   147.8  598.78   157.2  599.39   166.7  600.52   185.6  604.72
   195.1  605.94   214.1  606.56   223.7  607.07   233.2  608.33   242.8  611.25
   252.4  614.68     262  618.59   271.5   623.4   281.1  628.78   290.7  634.36
   300.2  639.68   309.8   644.4   319.4  648.88     329  653.31   338.5  657.52
#Mann= 3 , 0 , 0
       0      .1       0      91    .045       0   110.9      .1       0
Bank Sta=91,110.9
XS Rating Curve= 0 ,0
Exp/Cntr=0.3,0.1

Type RM Length L Ch R = 1 ,8043.9  ,136.5,114.6,93.3
XS GIS Cut Line= 3
      1762603.07      486189.552      1762690.31      486314.552
     1762833.539      486443.458
#Sta/Elev= 30
       0  649.77     9.5  642.13      19  634.77    28.6  626.91    57.2  603.28
    66.7  596.68   74.71   593.9    76.2  593.27    85.7  593.07    92.2  593.88
    95.3  594.27   104.8  596.66   114.3  599.26   123.8  601.42   133.4  602.46
   142.9   603.3   162.1  605.89   171.7  606.36   210.2  606.57   219.9  606.84
   229.5   607.3   258.4  607.82     268   608.1   277.7  608.96   287.3  610.87
     297  613.51   306.6  616.62   316.2  620.28   325.9  624.19   345.1  632.37
#Mann= 3 , 0 , 0
       0      .1       0   74.71    .045       0    92.2      .1       0
Bank Sta=74.71,92.2
XS Rating Curve= 0 ,0
Exp/Cntr=0.3,0.1

Type RM Length L Ch R = 1 ,7929.2  ,134.6,135.1,134.8
XS GIS Cut Line= 3
     1762519.737      486358.822     1762700.727      486360.124
     1762817.914      486447.364
#Sta/Elev= 30
       0  673.24     9.5  665.09      19  657.37    28.6  647.99    38.1  636.22
    47.6  623.99    57.2  612.23    66.7  601.19    76.2  594.38    85.7  592.62
    95.3   592.4   103.2  592.59   114.3  593.22   123.8  594.67   142.9  601.78
   152.4  603.65   171.5  605.85     181  606.56   190.7  606.83   200.5  606.74
     220  607.41   249.2  607.56   258.9  607.81   268.6  608.58   278.4  609.89
   288.1  611.77   297.9  614.32   307.6  617.35   317.4     621   327.1  625.02
#Mann= 3 , 0 , 0
       0      .1       0    85.7    .045       0   103.2      .1       0
Bank Sta=85.7,103.2
XS Rating Curve= 0 ,0
Exp/Cntr=0.3,0.1

Type RM Length L Ch R = 1 ,7794.1  ,221.5,222.4,223.1
XS GIS Cut Line= 2
     1762539.268      486486.427     1762786.664      486487.729
#Sta/Elev= 30
       0  653.67     9.5  645.54      19  637.24    28.6  629.01    38.1   620.7
    47.6  612.64    57.1   604.8    66.6  597.93    76.1   593.6    85.6  591.74
    88.8  591.43    90.6  591.41    95.2  591.11   104.7   591.4   105.6  591.67
   114.2  594.23   123.7  598.97   133.2  603.12   142.7  605.58   152.2   606.5
   161.8  606.61   171.3  606.65   180.8  606.74   190.3  606.84   199.8  607.06
   209.3  607.62   218.8  608.45   228.4  609.49   237.9  611.05   247.4  613.42
#Mann= 3 , 0 , 0
       0      .1       0    88.8    .045       0   105.6      .1       0
Bank Sta=88.8,105.6
XS Rating Curve= 0 ,0
Exp/Cntr=0.3,0.1

Type RM Length L Ch R = 1 ,7571.7  ,194,209.3,224.4
XS GIS Cut Line= 3
     1762562.706      486662.208     1762608.279      486689.552
     1762802.289      486693.458
#Sta/Elev= 29
       0  630.23     8.9  625.53    17.7  620.78    26.6  616.14    35.4  611.25
    44.3  606.19    53.2  601.43    62.8  597.75    72.6  595.44    82.2  594.21
      92  594.38   101.7  594.61   111.4   594.7   121.1  594.79   130.8  593.54
   140.5  591.34   141.2  591.26   150.2   590.2   156.2  590.45   159.9  590.61
   169.6  593.02   179.3  597.51     189  600.89   198.7  602.06   208.4  603.97
   218.1  607.72   227.8  612.94   237.5  618.27   247.2  622.96
#Mann= 3 , 0 , 0
       0      .1       0   141.2    .045       0   159.9      .1       0
Bank Sta=141.2,159.9
XS Rating Curve= 0 ,0
Exp/Cntr=0.3,0.1

Type RM Length L Ch R = 1 ,7362.3  ,151.2,150,149
XS GIS Cut Line= 4
     1762485.883      486754.656     1762583.539       486826.27
     1762699.425      486922.624     1762743.695      486972.104
#Sta/Elev= 30
       0  657.39     9.3  654.18    18.6  650.42      28  644.95    37.3  637.73
    46.6  631.41    55.9  626.39    65.2  621.86    74.5  617.51    83.8  613.82
   111.8  604.41   121.1  600.95   130.5  597.98   139.9  596.43   177.6   594.9
     187  594.28   196.5  593.23   205.9   591.9   219.3  590.46   234.1  588.98
   243.6  589.34     253  592.53   262.4  597.35   271.8  602.62   281.3  609.11
   300.3  625.67   309.8  633.73   319.2  640.78   328.7  647.28   338.2  652.58
#Mann= 3 , 0 , 0
       0      .1       0   219.3    .045       0   243.6      .1       0
Bank Sta=219.3,243.6
XS Rating Curve= 0 ,0
Exp/Cntr=0.3,0.1