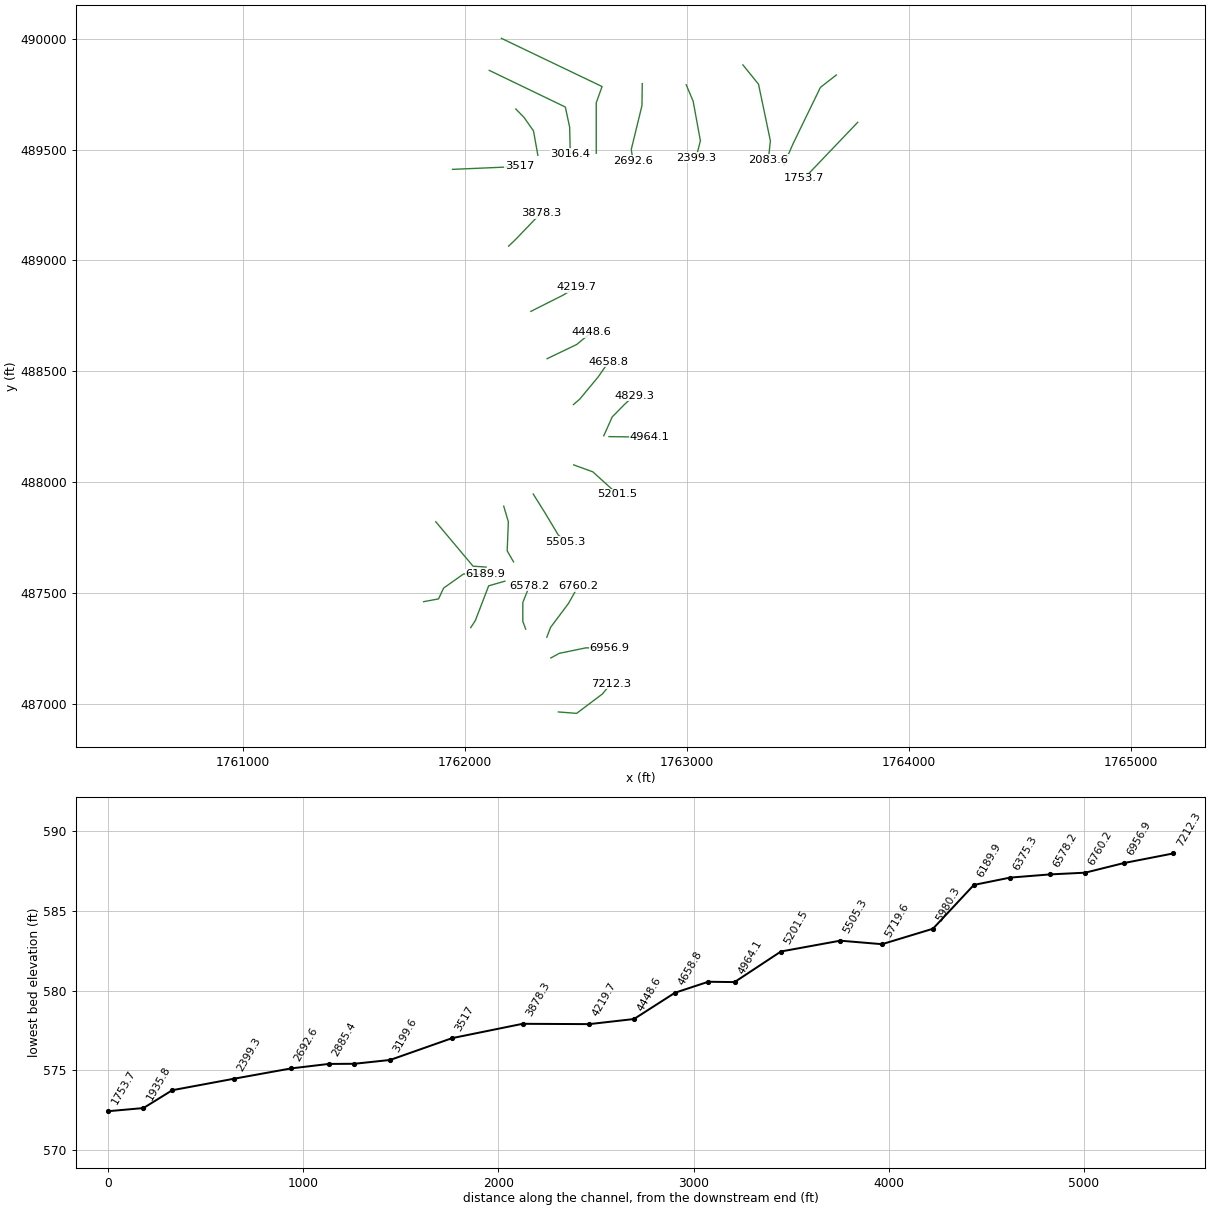
HEC-RAS study TRACEFORK.prj: TRACEFORK

--- TRACEFORK.g01 (geometry) --- (continued)

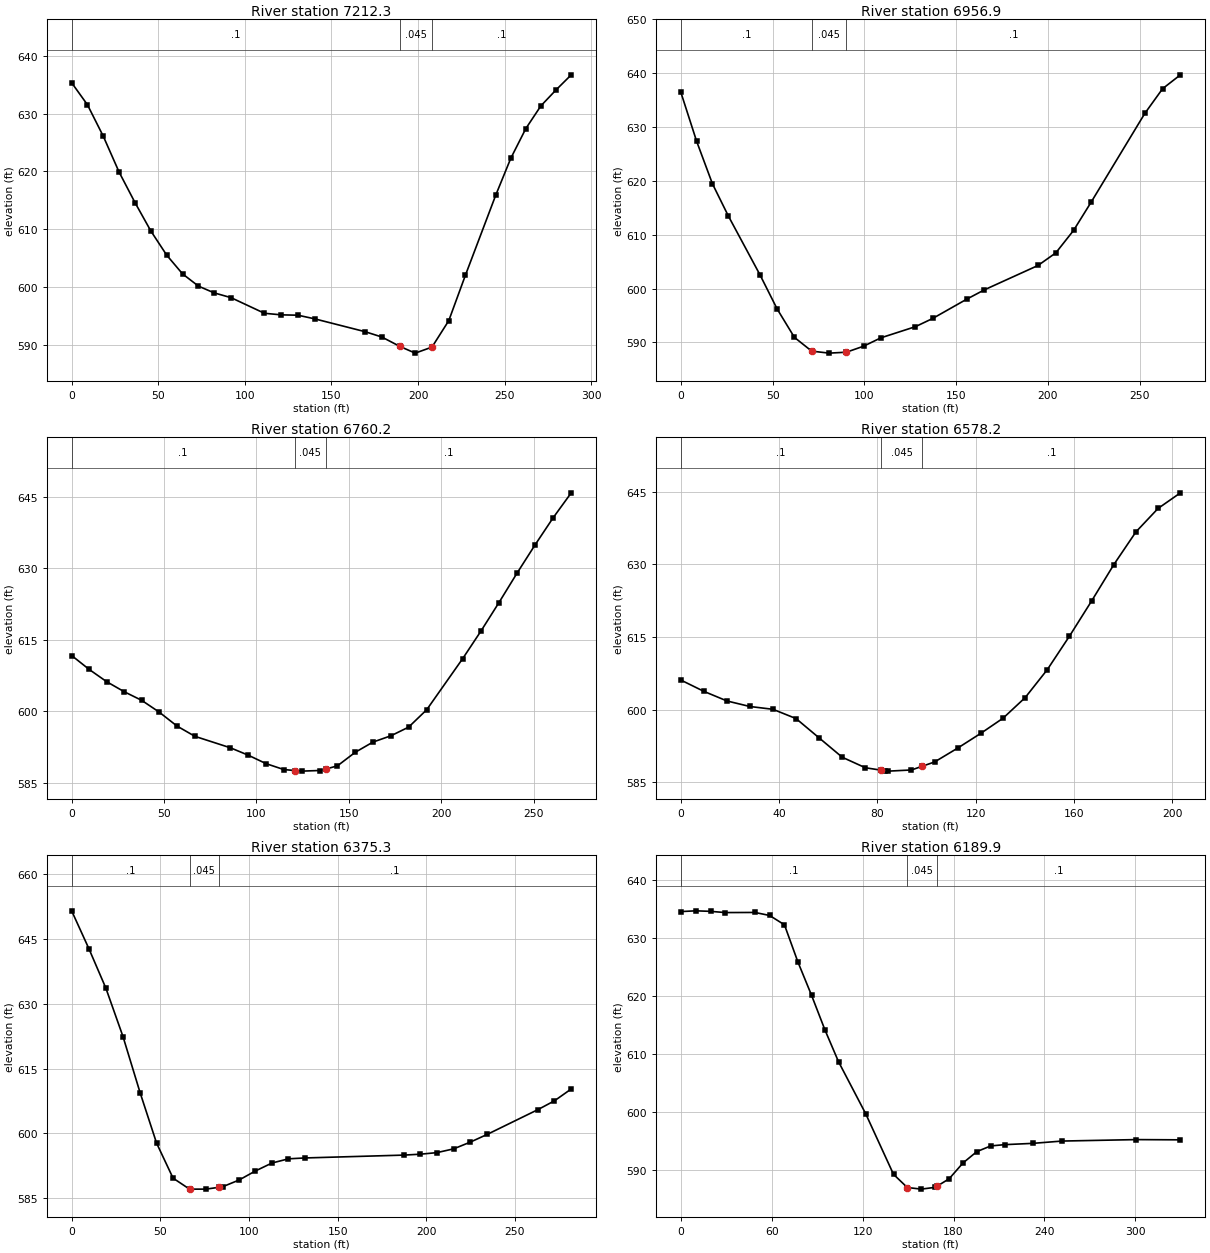
Type RM Length L Ch R = 1 ,7212.3  ,265.2,255.5,245.4
XS GIS Cut Line= 4
     1762420.779      486962.989      1762502.81      486956.479
     1762618.695      487043.718     1762657.758      487090.593
#Sta/Elev= 28
       0  635.31     9.1  631.52    18.3  626.05    27.4  619.88    36.6   614.6
    45.7  609.72    54.9  605.53      64  602.31    73.2  600.19    82.3  599.02
      92   598.2   111.3   595.5     121  595.23   130.6  595.17   140.3  594.54
   169.3  592.33     179  591.41   189.4  589.79   198.3  588.62     208  589.66
   217.7  594.23   227.3  602.07   244.8  615.89   253.5  622.27   262.2  627.41
   270.9  631.33   279.6  634.07   288.4  636.68
#Mann= 3 , 0 , 0
       0      .1       0   189.4    .045       0     208      .1       0
Bank Sta=189.4,208
XS Rating Curve= 0 ,0
Exp/Cntr=0.3,0.1

Type RM Length L Ch R = 1 ,6956.9  ,179.6,196.6,212.9
XS GIS Cut Line= 4
     1762386.925      487206.479     1762424.685      487227.312
     1762544.477      487252.052     1762651.247      487252.052
#Sta/Elev= 23
       0  636.44     8.6  627.34    17.2  619.46    25.9  613.46    43.1  602.56
    52.5  596.19    61.9  590.93    71.3  588.38    80.8  588.01    90.2  588.18
    99.6   589.3     109  590.85   127.8  592.92   137.2  594.44     156  598.07
   165.4  599.76   194.6  604.28   204.3  606.62     214   610.8   223.7  616.12
   252.8  632.51   262.5   637.1   272.2  639.67
#Mann= 3 , 0 , 0
       0      .1       0    71.3    .045       0    90.2      .1       0
Bank Sta=71.3,90.2
XS Rating Curve= 0 ,0
Exp/Cntr=0.3,0.1

Type RM Length L Ch R = 1 ,6760.2  ,167.4,182,196.8
XS GIS Cut Line= 4
     1762368.695      487300.229     1762385.622      487344.499
     1762466.352      487452.572      1762509.32      487529.395
#Sta/Elev= 29
       0   611.7     9.5  608.77      19  606.19    28.4   604.1    37.9  602.28
    47.4   599.8      57  596.88    66.7  594.72    85.9  592.31    95.6  590.75
   105.2  588.98   114.8  587.74   120.6  587.54   124.5  587.41   134.1  587.54
  137.64  587.86   143.8  588.52   153.4  591.36     163  593.51   172.7  594.83
   182.3  596.65   192.1  600.31   211.6  611.07   221.4  616.81   231.2  622.83
     241  629.03   250.8  634.99   260.5  640.64   270.3  645.88
#Mann= 3 , 0 , 0
       0      .1       0   120.6    .045       0  137.64      .1       0
Bank Sta=120.6,137.64
XS Rating Curve= 0 ,0
Exp/Cntr=0.3,0.1

Type RM Length L Ch R = 1 ,6578.2  ,211.1,202.9,194.5
XS GIS Cut Line= 4
     1762273.643      487336.687     1762260.622      487371.843
     1762260.622      487456.479      1762290.57      487531.999
#Sta/Elev= 26
       0   606.1     9.4  603.76    18.8  601.78    28.1  600.64    37.5  600.06
    46.9  598.15    56.3  594.16    65.7  590.17    75.1     588   81.49   587.5
    83.3  587.39    84.5   587.3    93.9  587.54    98.3  588.31   103.3  589.19
   112.7  592.05   122.1  595.09   131.2  598.23   140.2  602.48   149.2  608.25
   158.2  615.14   167.3  622.47   176.3  629.94   185.3  636.69   194.3  641.52
   203.4  644.74
#Mann= 3 , 0 , 0
       0      .1       0   81.49    .045       0    98.3      .1       0
Bank Sta=81.49,98.3
XS Rating Curve= 0 ,0
Exp/Cntr=0.3,0.1

Type RM Length L Ch R = 1 ,6375.3  ,198.6,185.4,172
XS GIS Cut Line= 4
     1762026.247      487343.197     1762047.081      487375.749
     1762106.977      487531.999     1762179.893      487552.833
#Sta/Elev= 25
       0  651.47     9.7  642.74    19.3  633.59      29  622.34    38.6  609.42
    47.9  597.75    57.2  589.64    66.5   587.1    75.8   587.1    83.2  587.53
    85.1  587.64    94.4   589.2   103.7  591.31     113  593.14   122.3  594.11
   131.6  594.31   187.4  594.97   196.7  595.18     206  595.54   215.5  596.42
   224.9  597.98   234.4  599.76   262.9  605.47   272.3  607.52   281.8  610.27
#Mann= 3 , 0 , 0
       0      .1       0    66.5    .045       0    83.2      .1       0
Bank Sta=66.5,83.2
XS Rating Curve= 0 ,0
Exp/Cntr=0.3,0.1

Type RM Length L Ch R = 1 ,6189.9  ,243.5,209.6,175.8
XS GIS Cut Line= 5
     1761814.008      487460.385     1761881.244      487473.019
     1761903.852      487521.583     1761993.695      487585.385
     1762091.352      487584.083
#Sta/Elev= 26
       0   634.5     9.8  634.63    19.6  634.54    29.3  634.33    48.9  634.35
    58.6  633.83    68.4  632.22    77.3   625.8    86.3  620.06    95.2  614.05
   104.1  608.61     122  599.66   140.4  589.19   149.5  586.92   158.7  586.64
   167.9  586.95   168.9  587.11   177.1  588.42   186.3  591.16   195.4  593.11
   204.6  594.09   213.8  594.31   232.2  594.53   251.7  594.93   300.5  595.18
   329.8  595.14
#Mann= 3 , 0 , 0
       0      .1       0   149.5    .045       0   168.9      .1       0
Bank Sta=149.5,168.9
XS Rating Curve= 0 ,0
Exp/Cntr=0.3,0.1

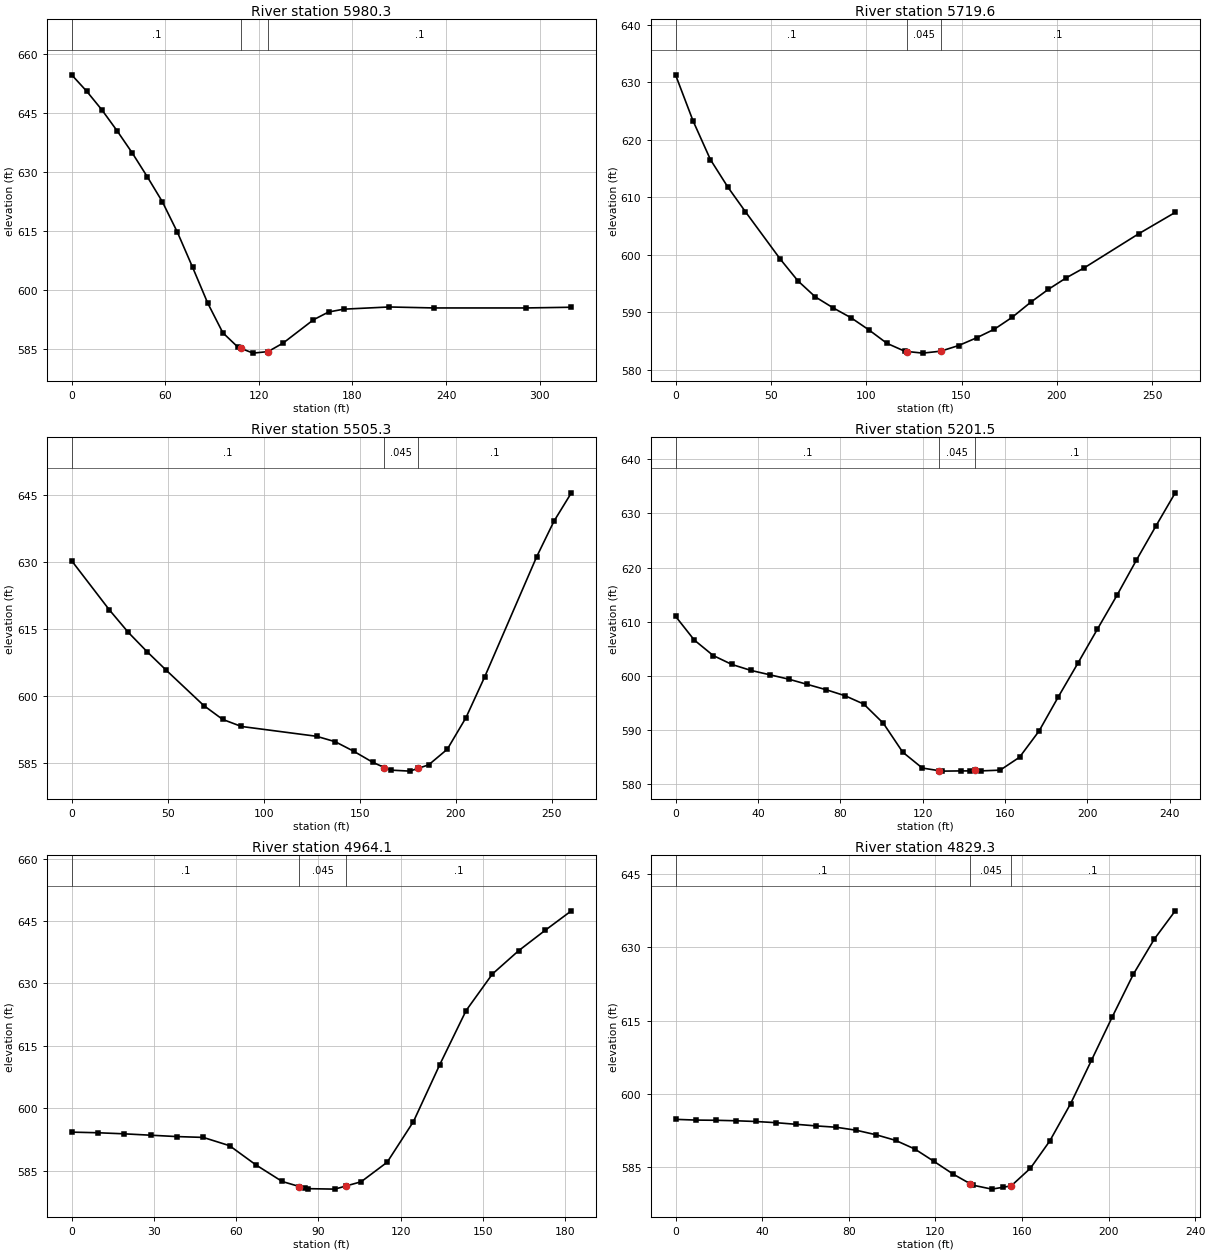
Type RM Length L Ch R = 1 ,5980.3  ,277.1,260.7,243.7
XS GIS Cut Line= 3
     1761868.695      487821.062     1762036.664      487620.541
     1762095.258      487616.635
#Sta/Elev= 23
       0   654.8     9.7  650.59    19.4  645.86    29.1  640.55    38.8  634.92
    48.4  628.88    58.1  622.49    67.8  614.68    77.5  605.78    87.2  596.65
    96.9  589.08   106.6   585.4   108.7  585.07   116.3  583.89   125.9  584.28
   135.6  586.47     155  592.39   164.7  594.37   174.4  595.09   203.4  595.65
   232.5   595.4   290.9   595.4   320.3  595.58
#Mann= 3 , 0 , 0
       0      .1       0   108.7    .045       0   125.9      .1       0
Bank Sta=108.7,125.9
XS Rating Curve= 0 ,0
Exp/Cntr=0.3,0.1

Type RM Length L Ch R = 1 ,5719.6  ,201.4,214.3,227.5
XS GIS Cut Line= 4
     1762174.685      487891.374     1762195.518      487821.062
      1762190.31      487689.552     1762218.956      487640.072
#Sta/Elev= 26
       0  631.29     9.2  623.28    18.3  616.56    27.5  611.75    36.7  607.48
      55  599.23    64.2  595.48    73.3   592.7    82.7  590.78    92.1  589.06
   101.5  586.94   110.9  584.62   120.3  583.24   121.6   583.2   129.7  582.92
   139.1  583.26   148.5  584.24   157.9  585.58   167.3  587.09   176.7  589.18
   186.2  591.74   195.6  594.02     205  596.02   214.5  597.77   243.1   603.7
   262.1  607.38
#Mann= 3 , 0 , 0
       0      .1       0   121.6    .045       0   139.1      .1       0
Bank Sta=121.6,139.1
XS Rating Curve= 0 ,0
Exp/Cntr=0.3,0.1

Type RM Length L Ch R = 1 ,5505.3  ,296.8,303.8,310.2
XS GIS Cut Line= 4
     1762307.497      487946.062     1762359.581      487862.729
     1762419.477      487762.468     1762452.029      487731.218
#Sta/Elev= 23
       0   630.3    19.6   619.3    29.5  614.24    39.3   609.9    49.1  605.82
    68.8  597.84    78.6  594.74    88.4  593.15   127.5  590.95   137.2  589.74
   146.9  587.59   156.7  585.14  162.89  583.93   166.4  583.36   176.1  583.14
   180.2  583.73   185.9  584.55   195.6  588.05   205.3  595.11   215.1   604.3
   242.1  631.16   251.2   639.2   260.2  645.52
#Mann= 3 , 0 , 0
       0      .1       0  162.89    .045       0   180.2      .1       0
Bank Sta=162.89,180.2
XS Rating Curve= 0 ,0
Exp/Cntr=0.3,0.1

Type RM Length L Ch R = 1 ,5201.5  ,220.4,237.4,254.1
XS GIS Cut Line= 3
     1762489.789      488077.572     1762575.727      488046.322
     1762687.706       487944.76
#Sta/Elev= 30
       0  611.01     9.1  606.63    18.3  603.77    27.4  602.12    36.6  601.03
    45.7  600.23    54.9  599.42      64  598.45    73.2  597.46    82.3  596.36
    91.4  594.82   100.9  591.28   110.3  585.96   119.8  583.03   128.1  582.53
   129.2  582.46   138.7   582.5   143.1   582.5  145.26   582.6   148.1   582.5
   157.6  582.64     167  585.02   176.5  589.86   185.9   596.2   195.4   602.4
   204.8  608.63   214.3  614.87   223.7  621.33   233.2  627.64   242.6  633.77
#Mann= 3 , 0 , 0
       0      .1       0   128.1    .045       0  145.26      .1       0
Bank Sta=128.1,145.26
XS Rating Curve= 0 ,0
Exp/Cntr=0.3,0.1

Type RM Length L Ch R = 1 ,4964.1  ,116,134.8,153.4
XS GIS Cut Line= 2
     1762648.643      488205.177     1762830.935      488202.572
#Sta/Elev= 23
       0  594.25     9.6   594.1    19.2  593.84    28.8  593.51    38.4  593.18
      48  592.98    57.6  590.99    67.2  586.38    76.8  582.38   83.08  581.16
      85   580.9    86.4  580.65      96  580.54     100  581.28   105.6  582.31
   115.1  587.01   124.7   596.8   134.3   610.5   143.9  623.49   153.5  632.29
   163.1  637.91   172.7  642.77   182.3  647.48
#Mann= 3 , 0 , 0
       0      .1       0   83.08    .045       0     100      .1       0
Bank Sta=83.08,100
XS Rating Curve= 0 ,0
Exp/Cntr=0.3,0.1

Type RM Length L Ch R = 1 ,4829.3  ,168.9,170.5,171.9
XS GIS Cut Line= 4
     1762625.206      488209.083     1762662.966      488293.718
     1762718.956       488351.01     1762761.925      488390.072
#Sta/Elev= 28
       0  594.82     9.3  594.67    18.5  594.63    27.8  594.53    37.1  594.38
    46.3  594.14    55.6  593.81    64.9  593.48    74.1  593.21    83.4   592.6
    92.7  591.66   101.6  590.53   110.5  588.76   119.4  586.22   128.3  583.61
   136.1  581.66   137.2  581.38   146.1  580.56   151.1  580.93     155  581.21
   163.9  584.82   172.8  590.36   182.5  598.04   192.1  606.88   201.8  615.83
   211.5  624.51   221.2   631.7   230.8  637.43
#Mann= 3 , 0 , 0
       0      .1       0   136.1    .045       0     155      .1       0
Bank Sta=136.1,155
XS Rating Curve= 0 ,0
Exp/Cntr=0.3,0.1

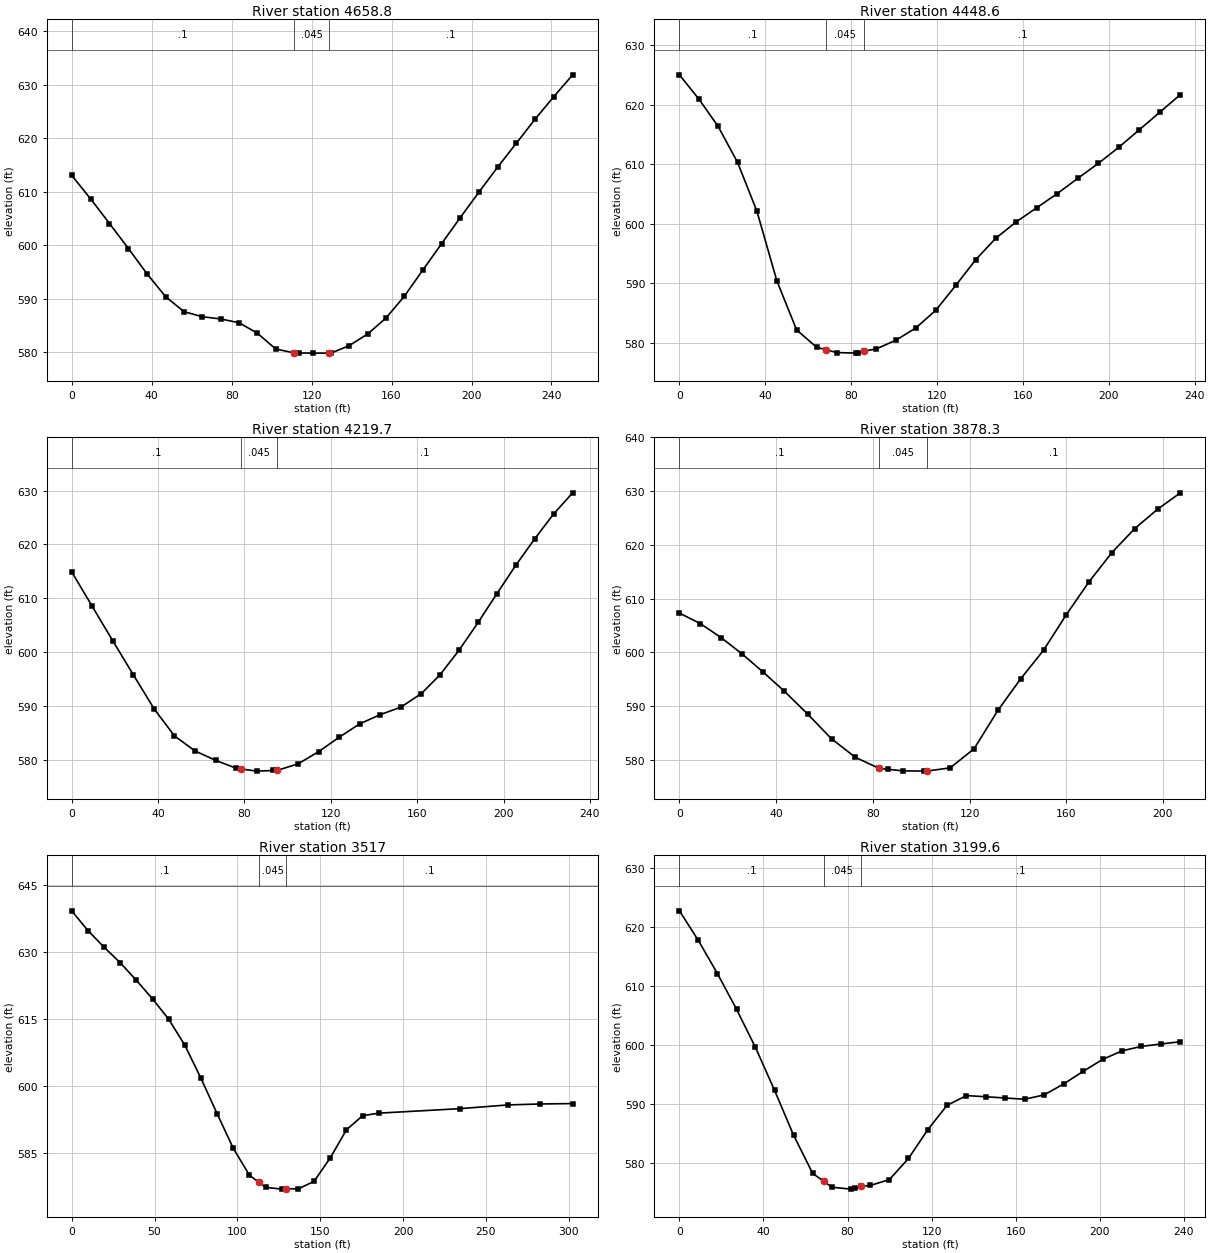
Type RM Length L Ch R = 1 ,4658.8  ,219.7,210.2,200.3
XS GIS Cut Line= 4
     1762488.487      488349.708     1762517.133      488374.447
     1762599.164      488473.406     1762647.341      488542.416
#Sta/Elev= 30
       0  613.09     9.5  608.67    18.9  604.09    28.4   599.4    37.8  594.63
      47  590.41    56.2  587.61    65.4  586.67    74.6  586.25    83.8  585.54
    92.9  583.58   102.1  580.63   111.3  579.92   113.7  579.91   120.5  579.87
   128.7  579.87   129.7  579.87   138.8  581.27     148  583.43   157.2  586.42
   166.4   590.5   175.7  595.42   185.1  600.35   194.4  605.21   203.8  609.99
   213.1  614.64   222.5  619.13   231.8  623.58   241.2  627.81   250.6  631.87
#Mann= 3 , 0 , 0
       0      .1       0   111.3    .045       0   128.7      .1       0
Bank Sta=111.3,128.7
XS Rating Curve= 0 ,0
Exp/Cntr=0.3,0.1

Type RM Length L Ch R = 1 ,4448.6  ,228.6,229,229.4
XS GIS Cut Line= 4
     1762369.997      488556.739      1762402.55      488572.364
      1762502.81      488620.541     1762569.216      488675.229
#Sta/Elev= 29
       0  625.05       9     621      18  616.39    27.1  610.31    36.1   602.1
    45.4  590.38    54.6  582.13    63.9  579.21    68.1  578.81    73.2  578.32
    82.5  578.22    83.1  578.27   86.14  578.57    91.7  578.92     101  580.42
   110.3   582.5   119.5  585.45   128.8  589.64   138.1  593.96   147.3  597.52
   156.9   600.3   166.5  602.69     176  605.05   185.6  607.63   195.1  610.13
   204.7  612.85   214.2  615.78   223.8  618.75   233.4  621.72
#Mann= 3 , 0 , 0
       0      .1       0    68.1    .045       0   86.14      .1       0
Bank Sta=68.1,86.14
XS Rating Curve= 0 ,0
Exp/Cntr=0.3,0.1

Type RM Length L Ch R = 1 ,4219.7  ,333.2,341.3,348.7
XS GIS Cut Line= 3
     1762297.081      488770.281     1762441.612      488843.197
     1762501.508      488879.656
#Sta/Elev= 28
       0  614.89     9.5   608.5      19  602.11    28.6  595.75    38.1   589.5
    47.6  584.44    57.1  581.65    66.7  579.89    76.2  578.44    78.4  578.31
    85.7   577.9    93.4  578.02    95.2  578.05   104.8  579.24   114.3   581.5
   123.8  584.17   133.3  586.66   142.8  588.38   152.4  589.77   161.9  592.29
   170.6   595.8   179.4  600.36   188.2   605.5   196.9  610.85   205.7  616.14
   214.5  621.08   223.2  625.66     232  629.58
#Mann= 3 , 0 , 0
       0      .1       0    78.4    .045       0    95.2      .1       0
Bank Sta=78.4,95.2
XS Rating Curve= 0 ,0
Exp/Cntr=0.3,0.1

Type RM Length L Ch R = 1 ,3878.3  ,379,361.3,344.1
XS GIS Cut Line= 4
      1762196.82      489064.552      1762228.07      489094.499
     1762289.268      489158.302     1762341.352      489212.989
#Sta/Elev= 25
       0   607.3     8.7  605.34    17.3  602.72      26  599.68    34.6  596.34
    43.3  592.82    53.1   588.5    62.9  583.93    72.8  580.48    82.6  578.43
    86.2  578.26    92.4  577.97   101.2  577.93   102.2  577.92     112  578.53
   121.9  582.09   131.7   589.2   141.1  595.05   150.6  600.39     160  606.99
   169.4  613.11   178.9  618.56   188.3     623   197.8  626.62   207.2  629.66
#Mann= 3 , 0 , 0
       0      .1       0    82.6    .045       0   102.2      .1       0
Bank Sta=82.6,102.2
XS Rating Curve= 0 ,0
Exp/Cntr=0.3,0.1

Type RM Length L Ch R = 1 ,3517    ,339.7,317.4,295.2
XS GIS Cut Line= 2
     1761944.216      489410.906       1762246.3      489423.927
#Sta/Elev= 26
       0  639.15     9.8  634.74    19.5  631.04    29.3  627.56      39  623.65
    48.8  619.49    58.5  614.97    68.3  609.14      78  601.78    87.8  593.84
    97.5  586.16   107.3  580.12   112.9  578.56     117  577.42   126.8  577.02
  129.58  577.14   136.6  577.04   146.3  578.76   156.1     584   165.8  590.24
   175.6  593.41   185.3  593.98   234.1  594.98   263.4  595.82   282.9  596.03
   302.4  596.12
#Mann= 3 , 0 , 0
       0      .1       0   112.9    .045       0  129.58      .1       0
Bank Sta=112.9,129.58
XS Rating Curve= 0 ,0
Exp/Cntr=0.3,0.1

Type RM Length L Ch R = 1 ,3199.6  ,192.5,183.3,173.6
XS GIS Cut Line= 4
     1762229.372      489683.041     1762267.133      489643.979
       1762308.8      489584.083     1762328.331      489474.708
#Sta/Elev= 30
       0  622.77       9  617.76    18.1  612.13    27.2  606.09    36.2  599.63
    45.3  592.36    54.3   584.8    63.4  578.32    68.7  576.97    72.6  575.97
    81.7  575.65    83.7  575.79   86.36  576.12    90.8  576.27    99.9  577.26
     109  580.84   118.2  585.71   127.3  589.82   136.6  591.49   145.8  591.29
   155.1  591.08   164.3  590.86   173.6  591.61   182.8  593.45   192.1  595.58
   201.4  597.61   210.6  599.06   219.9  599.82   229.1  600.22   238.4  600.61
#Mann= 3 , 0 , 0
       0      .1       0    68.7    .045       0   86.36      .1       0
Bank Sta=68.7,86.36
XS Rating Curve= 0 ,0
Exp/Cntr=0.3,0.1

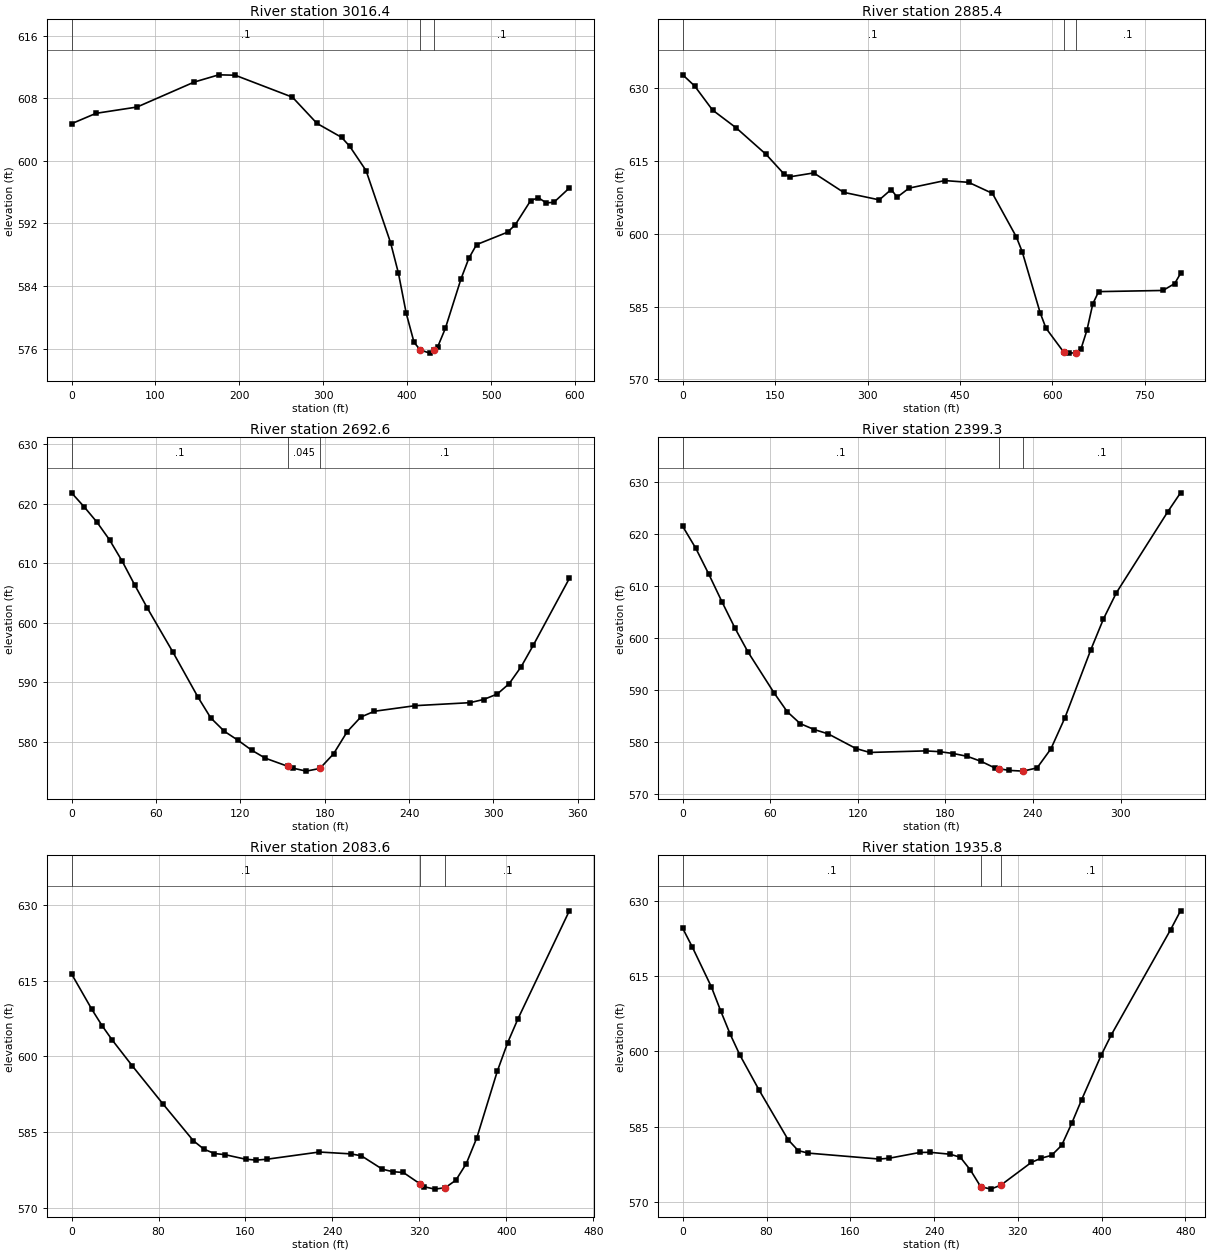
Type RM Length L Ch R = 1 ,3016.4  ,135.9,131,126.3
XS GIS Cut Line= 4
     1762109.581       489857.52     1762452.029      489692.156
      1762471.56       489601.01     1762474.164      489481.218
#Sta/Elev= 30
       0  604.74    29.2  606.07      78  606.87   146.3  610.07   175.5  610.99
     195  610.94   263.3  608.13   292.5  604.78   321.8     603   331.5  601.86
     351  598.75   380.3  589.51   389.6  585.63   398.9   580.5   408.2  576.79
   415.6  575.82   426.9  575.41  432.03  575.82   436.2  576.16   445.5  578.57
   464.2  584.91   473.5  587.53   482.7  589.28   519.6  590.87   528.8  591.81
   547.2  594.91   556.4  595.28   565.7  594.62   574.9  594.69   593.3  596.52
#Mann= 3 , 0 , 0
       0      .1       0   415.6    .045       0  432.03      .1       0
Bank Sta=415.6,432.03
XS Rating Curve= 0 ,0
Exp/Cntr=0.3,0.1

Type RM Length L Ch R = 1 ,2885.4  ,198.1,192.7,187.3
XS GIS Cut Line= 4
     1762164.268      490002.052     1762617.393      489784.604
     1762591.352      489711.687     1762591.352      489483.822
#Sta/Elev= 30
       0  632.82    19.3  630.52    48.3  625.56      87  621.85   135.3   616.4
   164.3  612.37     174  611.78   212.6  612.58     261  608.58     319  607.02
   338.3  609.16     348  607.58   367.3  609.44   425.3     611   463.9  610.64
   502.6  608.36   541.3  599.41     551   596.3     580  583.76   589.5  580.55
     618  575.66   627.5   575.4   637.6  575.47   646.5  576.32     656  580.13
   665.5  585.56     675  588.09   779.4  588.33   798.4  589.75   807.9  591.83
#Mann= 3 , 0 , 0
       0      .1       0     618    .045       0   637.6      .1       0
Bank Sta=618,637.6
XS Rating Curve= 0 ,0
Exp/Cntr=0.3,0.1

Type RM Length L Ch R = 1 ,2692.6  ,283.2,293.4,303.2
XS GIS Cut Line= 4
     1762798.383      489797.624     1762797.081      489698.666
     1762748.904      489500.749     1762756.716      489449.968
#Sta/Elev= 30
       0  621.79       9  619.43      18  616.89      27  613.91      36  610.33
      45   606.3      54  602.42      72  595.11      90  587.49      99  584.04
   108.7  581.79   118.4  580.29   128.1  578.63   137.8  577.29   154.1   575.9
   157.2  575.63   166.9  575.12   176.6  575.57   186.3  578.01     196  581.73
   205.7  584.19   215.4  585.16   244.5   586.1   283.3   586.6     293  587.13
   302.7  588.04   311.2  589.78   319.8  592.65   328.4  596.25     354  607.43
#Mann= 3 , 0 , 0
       0      .1       0   154.1    .045       0   176.6      .1       0
Bank Sta=154.1,176.6
XS Rating Curve= 0 ,0
Exp/Cntr=0.3,0.1

Type RM Length L Ch R = 1 ,2399.3  ,315.1,315.7,316.2
XS GIS Cut Line= 4
       1762996.3      489792.416      1763027.55      489718.197
     1763060.102      489539.812      1763040.57      489462.989
#Sta/Elev= 30
       0   621.5       9  617.27    17.9   612.3    26.8  607.06    35.8  601.95
    44.7  597.37    62.6   589.5    71.6  585.89    80.5   583.6    90.1  582.46
    99.6  581.64   118.7  578.81   128.2  578.06   166.4  578.36     176  578.21
   185.5  577.85     195  577.31   204.6  576.33   214.1  575.05     217  574.92
   223.7  574.61   233.2  574.47   242.8  575.09   252.3  578.76   261.9  584.74
   279.5  597.71   288.3  603.73   297.1  608.73   332.3   624.3   341.1  627.96
#Mann= 3 , 0 , 0
       0      .1       0     217    .045       0   233.2      .1       0
Bank Sta=217,233.2
XS Rating Curve= 0 ,0
Exp/Cntr=0.3,0.1

Type RM Length L Ch R = 1 ,2083.6  ,163.2,147.7,132.2
XS GIS Cut Line= 4
     1763251.508       489882.26      1763321.82       489795.02
     1763375.206      489539.812     1763366.091      489455.177
#Sta/Elev= 30
       0  616.31    18.7  609.29      28   606.1    37.4  603.24      56  598.09
      84  590.62     112  583.33   121.7  581.66   131.4  580.79     141  580.57
   160.3  579.66     170  579.49   179.6  579.66   227.9  581.09   256.9  580.72
   266.6  580.34   285.9  577.69   295.5   577.2   305.2  577.04   320.8  574.76
   324.5  574.21   334.2  573.75   343.8  574.04   353.5  575.51   363.1  578.79
   372.8   583.9   391.7  597.11   401.2  602.73   410.6  607.41   457.9  628.79
#Mann= 3 , 0 , 0
       0      .1       0   320.8    .045       0   343.8      .1       0
Bank Sta=320.8,343.8
XS Rating Curve= 0 ,0
Exp/Cntr=0.3,0.1

Type RM Length L Ch R = 1 ,1935.8  ,188.7,182.1,175.6
XS GIS Cut Line= 4
     1763672.081      489836.687     1763600.466      489780.697
      1763478.07      489528.093     1763436.404      489433.041
#Sta/Elev= 30
       0  624.47     9.1  620.78    27.3  612.86    36.4  607.98    45.4  603.39
    54.5  599.31    72.7   592.4   100.6  582.46   110.3  580.28   119.9  579.79
   187.7  578.61   197.4  578.78   226.4  579.92   236.1  579.95   255.4  579.57
   265.1  578.96   274.8   576.4   284.5  573.13   294.2  572.63   303.8  573.42
   332.9  577.94   342.6   578.8   352.2  579.34   361.9  581.34   371.6  585.77
     381  590.43   399.9  599.37   409.3  603.31     466  624.24   475.4  627.96
#Mann= 3 , 0 , 0
       0      .1       0   284.5    .045       0   303.8      .1       0
Bank Sta=284.5,303.8
XS Rating Curve= 0 ,0
Exp/Cntr=0.3,0.1

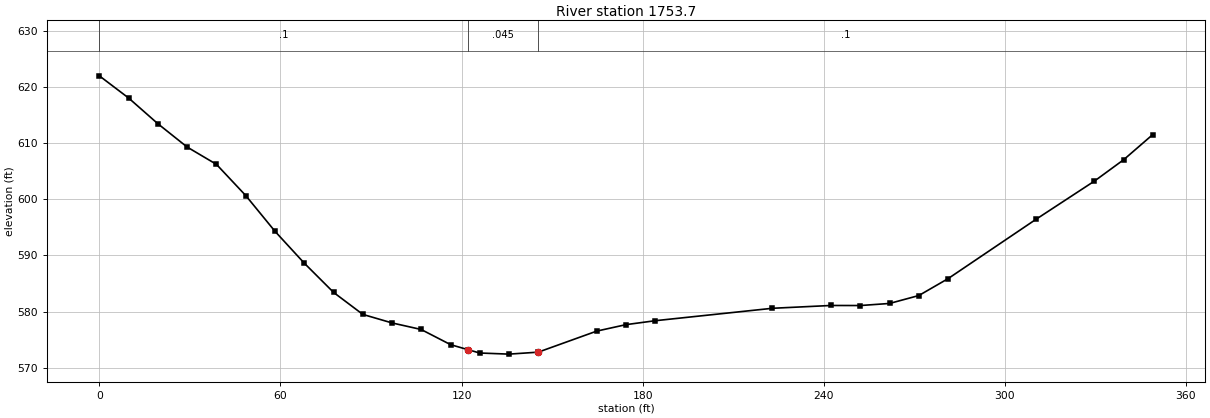
Type RM Length L Ch R = 1 ,1753.7  ,92,100.2,108.9
XS GIS Cut Line= 2
     1763768.435      489623.145      1763527.55      489370.541
#Sta/Elev= 30
       0  621.97     9.7  618.02    19.4  613.44    29.1  609.29    38.8  606.21
    48.5  600.66    58.2  594.29    67.9  588.62    77.6  583.42    87.3   579.5
      97  577.98   106.6  576.82   116.4  574.11   122.1  573.23     126  572.63
   135.7  572.43   145.4  572.78   164.8  576.53   174.5  577.68   184.2  578.38
     223  580.59   242.4  581.09   252.1  581.08   261.8  581.45   271.5  582.86
   281.2  585.87   310.3  596.42   329.7  603.24   339.4  607.05     349  611.51
#Mann= 3 , 0 , 0
       0      .1       0   122.1    .045       0   145.4      .1       0
Bank Sta=122.1,145.4
XS Rating Curve= 0 ,0
Exp/Cntr=0.3,0.1