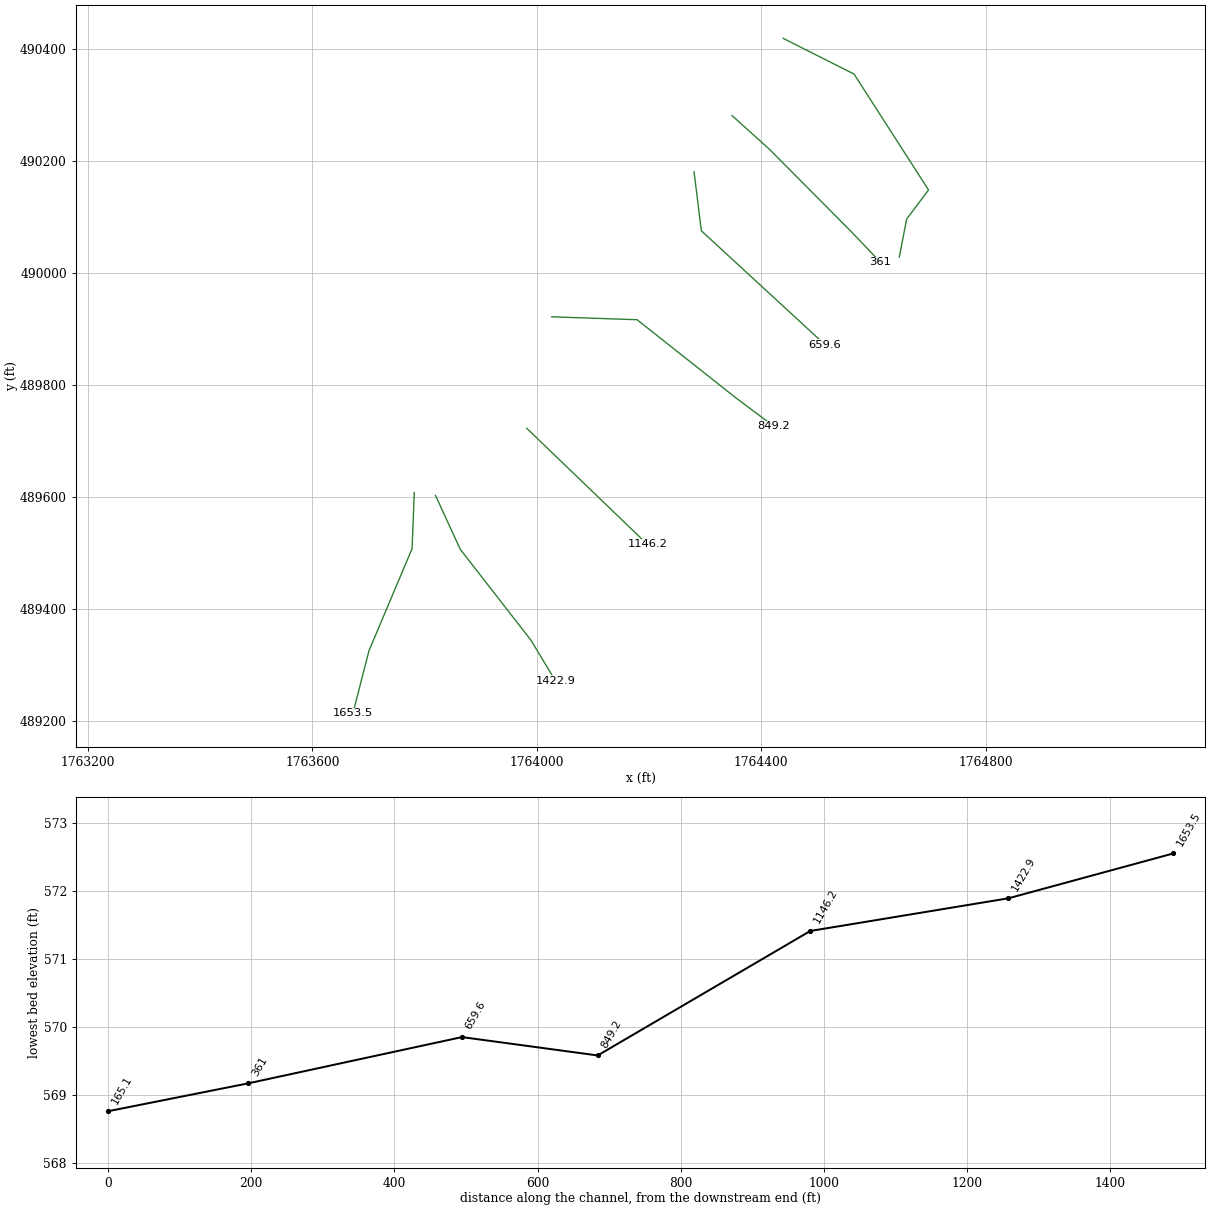
HEC-RAS study TRACEFORK.prj: TRACEFORK

--- TRACEFORK.g01 (geometry) --- (continued)

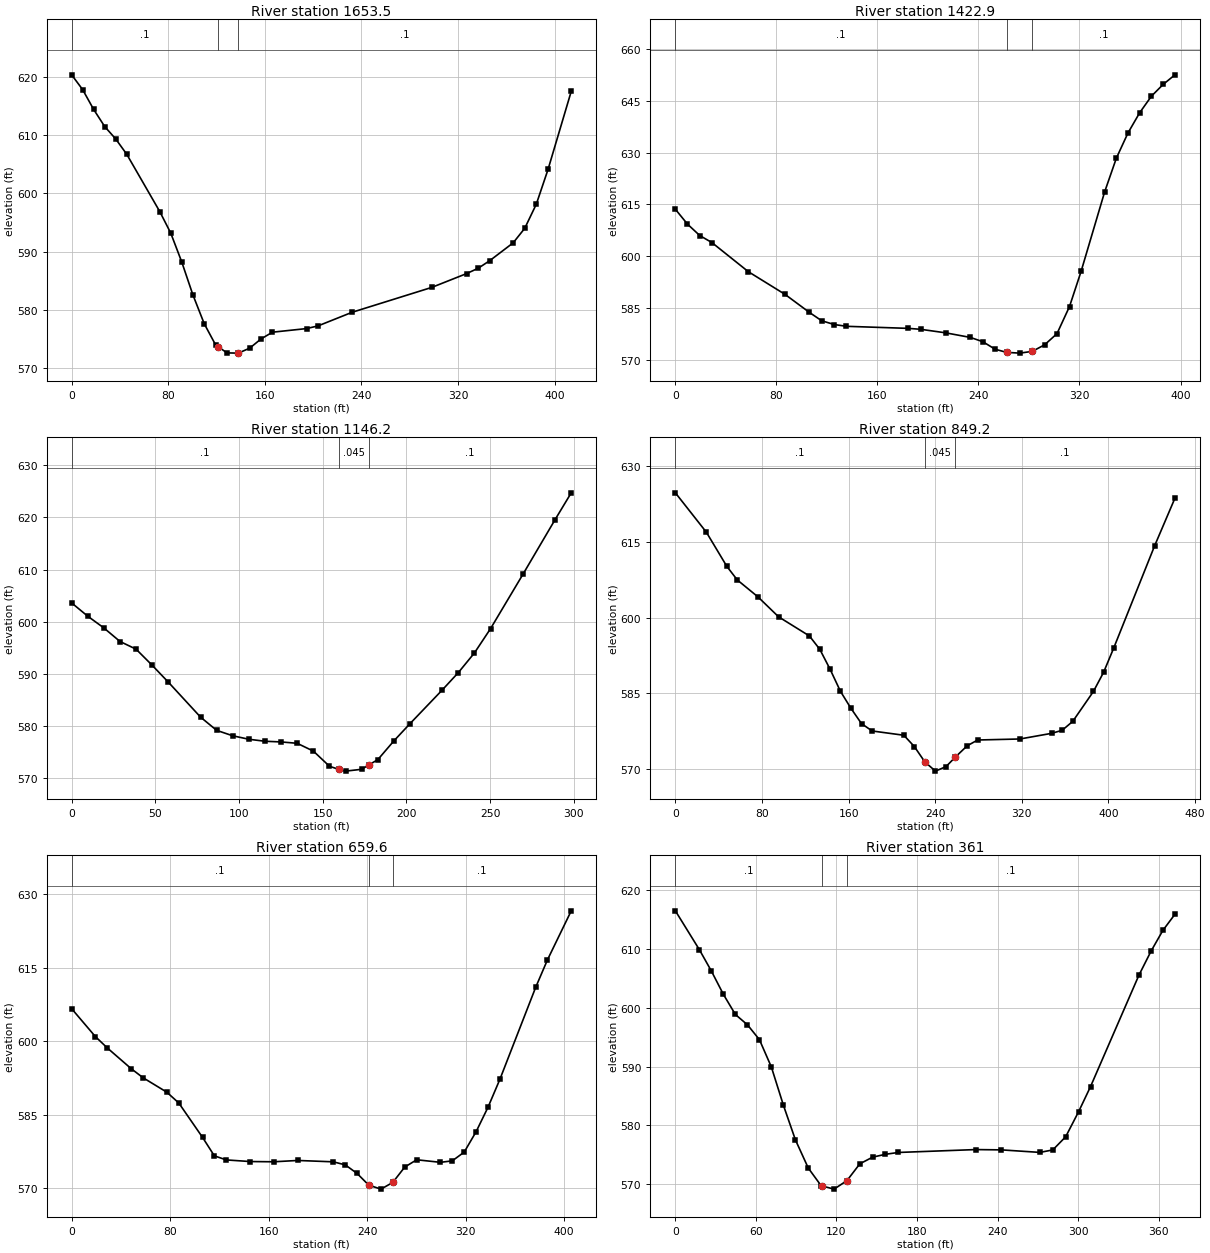
Type RM Length L Ch R = 1 ,1653.5  ,201.6,230.6,255.9
XS GIS Cut Line= 4
     1763781.456       489607.52      1763777.55       489507.26
     1763700.727      489324.968     1763672.081      489212.989
#Sta/Elev= 30
       0   620.4     9.1  617.86    18.2  614.46    27.4   611.5    36.5  609.37
    45.6  606.75      73  596.88    82.1  593.17    91.2  588.21   100.3  582.63
   109.8   577.6   119.2  573.97   121.4  573.65   128.6  572.59     138  572.55
   147.4   573.4   156.9     575   166.3  576.15   194.5  576.77     204  577.23
   232.2  579.57   298.2  583.85     327  586.22   336.7  587.15   346.3  588.46
   365.6  591.51   375.2  594.01   384.8  598.17   394.5  604.14   413.7  617.56
#Mann= 3 , 0 , 0
       0      .1       0   121.4    .045       0     138      .1       0
Bank Sta=121.4,138
XS Rating Curve= 0 ,0
Exp/Cntr=0.3,0.1

Type RM Length L Ch R = 1 ,1422.9  ,277.6,276.7,278
XS GIS Cut Line= 4
     1763819.216      489602.312     1763863.487      489505.958
     1763989.789      489343.197     1764032.758      489271.583
#Sta/Elev= 30
       0  613.57     9.6  609.26    19.3  605.96    28.9  603.93    57.8  595.48
    86.8  588.92     106  583.72   115.8  581.28   125.7  580.18   135.5  579.66
   184.5  579.06   194.3  578.79     214  577.77   233.6  576.44   243.4  575.21
   253.2  573.02   262.3  572.11   272.8  571.89   282.6   572.4   292.4   574.3
   302.2  577.54   312.1  585.39   321.3  595.61   339.9  618.58   349.2  628.38
   358.4  635.68   367.7  641.56     377  646.35   386.3  649.76   395.6  652.52
#Mann= 3 , 0 , 0
       0      .1       0   262.3    .045       0   282.6      .1       0
Bank Sta=262.3,282.6
XS Rating Curve= 0 ,0
Exp/Cntr=0.3,0.1

Type RM Length L Ch R = 1 ,1146.2  ,294.5,297,299.9
XS GIS Cut Line= 2
     1763981.977      489722.104      1764196.82      489515.072
#Sta/Elev= 30
       0  603.62     9.6  601.08    19.2  598.84    28.9  596.23    38.5  594.76
    48.1  591.68    57.8  588.43      77  581.75    86.6  579.22    96.2  578.18
   105.9  577.51   115.5  577.13   125.1     577   134.7  576.74   144.4  575.24
     154  572.34  159.43  571.76   163.6  571.41   173.2  571.76   177.4  572.57
   182.9  573.62   192.5  577.21   202.1   580.5   221.4  586.96     231  590.29
   240.6  594.05   250.2  598.69   269.5  609.07   288.7  619.54   298.4   624.7
#Mann= 3 , 0 , 0
       0      .1       0  159.43    .045       0   177.4      .1       0
Bank Sta=159.43,177.4
XS Rating Curve= 0 ,0
Exp/Cntr=0.3,0.1

Type RM Length L Ch R = 1 ,849.2   ,191.1,189.6,188.5
XS GIS Cut Line= 4
     1764026.247      489921.322     1764178.591      489916.114
     1764354.372      489776.791     1764422.081       489726.01
#Sta/Elev= 30
       0  624.74    28.6  616.94    47.6  610.14    57.2  607.47    76.2  604.13
    95.3  600.17   123.8  596.37   133.4  593.72   142.9  589.77   152.4  585.42
   162.2  582.01   171.9     579   181.7  577.54     211  576.69   220.7  574.45
   230.4  571.41   240.2  569.58     250  570.48   258.7  572.39   269.5   574.6
   279.2  575.75   318.2  575.95   347.5  577.07   357.2  577.67     367  579.44
   386.1  585.37   395.5  589.17   404.9  594.01   442.6  614.23   461.4  623.69
#Mann= 3 , 0 , 0
       0      .1       0   230.4    .045       0   258.7      .1       0
Bank Sta=230.4,258.7
XS Rating Curve= 0 ,0
Exp/Cntr=0.3,0.1

Type RM Length L Ch R = 1 ,659.6   ,298.3,298.6,297.2
XS GIS Cut Line= 3
     1764280.154      490180.437     1764293.175      490074.968
     1764513.227      489871.843
#Sta/Elev= 30
       0  606.67    19.3  600.97      29  598.65    48.3  594.44      58  592.58
    77.3  589.63      87  587.43   106.3  580.41   115.9  576.64   125.6  575.81
   144.9  575.48   164.2  575.43   183.6   575.7   212.5  575.42   222.2   574.8
   231.8  573.05   241.3  570.66   251.2  569.85   260.8  571.22   270.5  574.35
   280.2  575.84   299.5  575.32   309.1  575.62   318.8  577.41   328.5  581.59
   338.1  586.55   347.8  592.28   376.8  611.01   386.4  616.64   405.7  626.64
#Mann= 3 , 0 , 0
       0      .1       0   241.3    .045       0   260.8      .1       0
Bank Sta=241.3,260.8
XS Rating Curve= 0 ,0
Exp/Cntr=0.3,0.1

Type RM Length L Ch R = 1 ,361     ,200.6,195.9,191.2
XS GIS Cut Line= 4
     1764347.862      490280.697     1764414.268      490220.802
     1764562.706      490071.062     1764612.185      490018.979
#Sta/Elev= 30
       0  616.53    17.9  609.91    26.8  606.29    35.8   602.3    44.7  598.89
    53.7  597.13    62.6  594.61    71.5  589.95    80.5  583.42    89.4  577.56
      99  572.75   108.6  569.74   109.3   569.7   118.2  569.17   127.8  570.62
   137.4  573.48   146.9  574.61   156.5   575.1   166.1  575.41   223.6   575.9
   242.8  575.85   271.5  575.42   281.1  575.84   290.7  578.08   300.3  582.33
   309.2  586.61   345.2  605.55   354.2  609.63   363.1   613.2   372.1  615.95
#Mann= 3 , 0 , 0
       0      .1       0   109.3    .045       0   127.8      .1       0
Bank Sta=109.3,127.8
XS Rating Curve= 0 ,0
Exp/Cntr=0.3,0.1

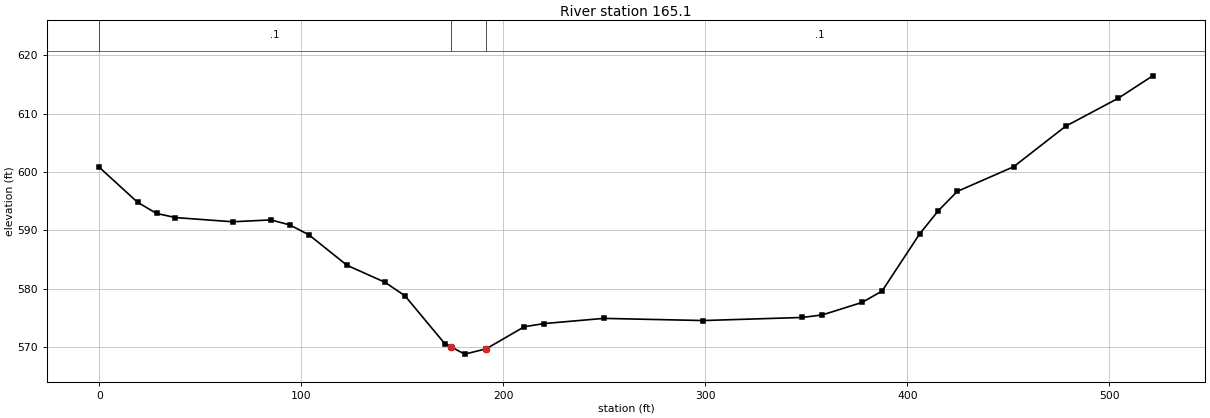
Type RM Length L Ch R = 1 ,165.1   ,166,165.1,163.8
XS GIS Cut Line= 5
     1764439.008      490418.718      1764565.31      490354.916
     1764698.122      490147.885      1764659.06      490095.802
     1764646.039      490028.093
#Sta/Elev= 30
       0  600.79    18.9  594.81    28.3  592.89    37.7  592.18      66  591.46
    84.9  591.78    94.3  590.92   103.8  589.21   122.6     584   141.5  581.07
   151.3  578.76     171  570.56  174.11     570   180.9  568.76   191.5  569.67
   210.4  573.46   220.2     574   249.7  574.89   298.9  574.52   348.1  575.05
     358  575.49   377.6  577.63   387.5  579.58   406.1  589.38   415.4  593.37
   424.7  596.66   452.6  600.89   478.4  607.85   504.3  612.62   521.5  616.49
#Mann= 3 , 0 , 0
       0      .1       0  174.11    .045       0   191.5      .1       0
Bank Sta=174.11,191.5
XS Rating Curve= 0 ,0
Exp/Cntr=0.3,0.1

Chan Stop Cuts=-1
Use User Specified Reach Order=0
Composite Channel Slope=5